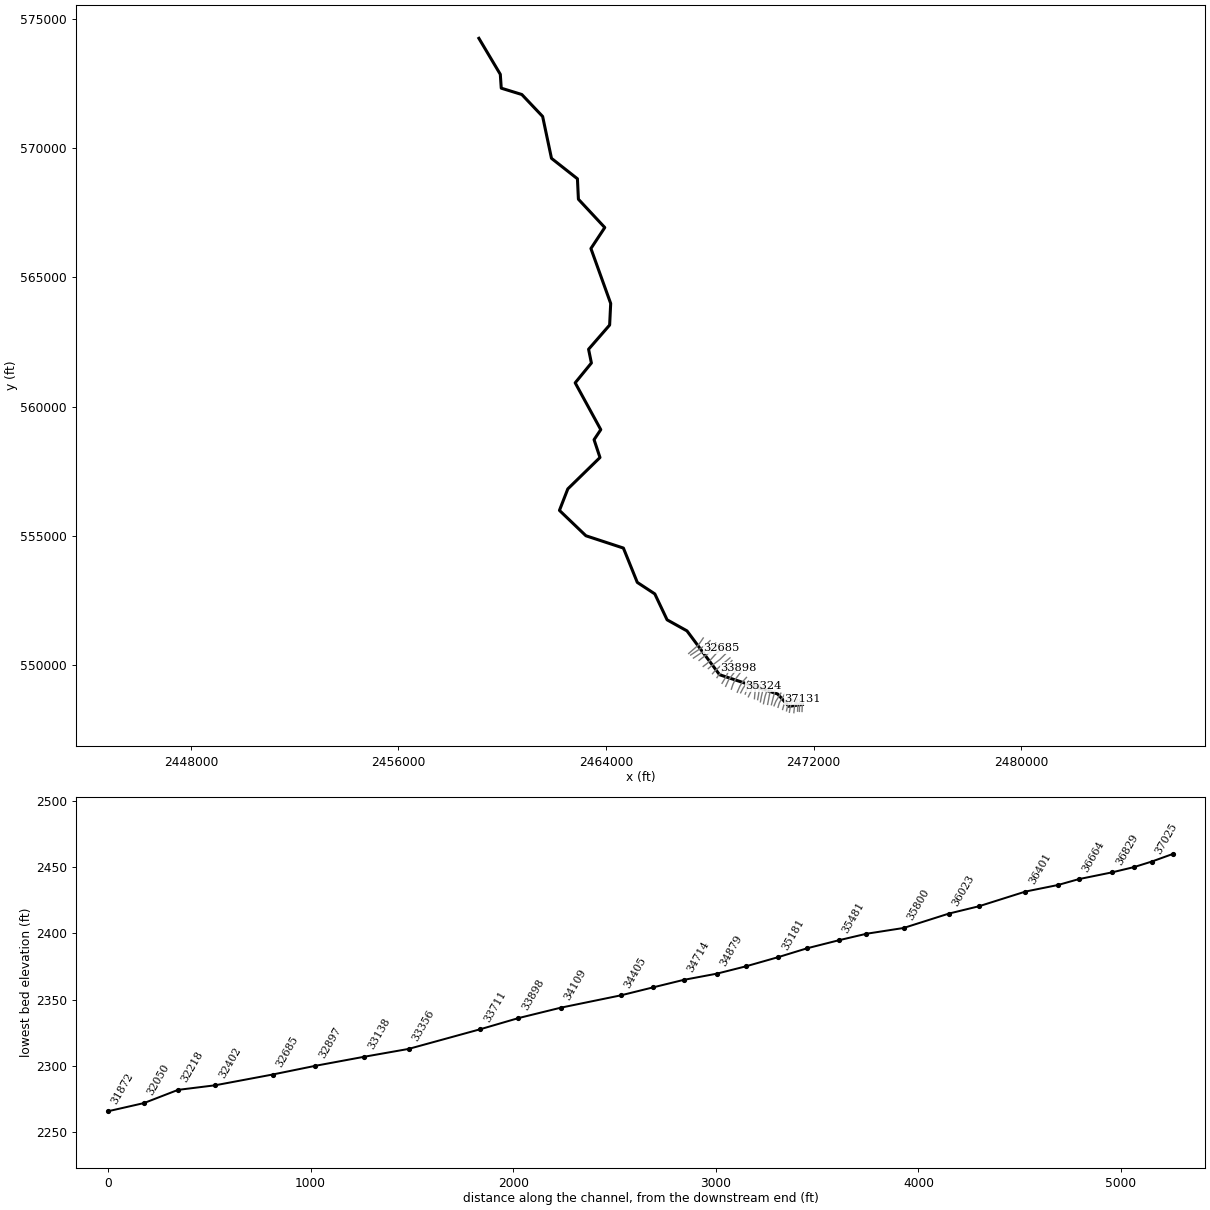
--- LITTLEFK.prj (project) ---

Proj Title=LITTLEFK
Current Plan=p01
Default Exp/Contr=0,0
English Units
Geom File=g01
Flow File=f01
Plan File=p01
Background Map Layer=Inundation Boundary (P100yr Value_0)
BEGIN DESCRIPTION:
Stream Name: Little Fork
Flood Zone: Zone A
Pendleton County, WV
WVDHSEM Flood Warning & Analysis Mapping
HEC-RAS Version: 5.0.7
Hydrology Method:
Regression was used
Model Notes:
Model ties in with South Fork South Branch South Potomac River
END DESCRIPTION:
DSS Export Rating Curves= 0
DSS Export Rating Curve Sorted= 0
DSS Export Volume Flow Curves= 0
DXF Filename=H:\CTP\WV\f03_Pendleton_RiskMAP\f05_Engineering\f02_Hydraulics\02_Final\Approximate\LITTLEFK\LITTLEFK.
DXF OffsetX= 0
DXF OffsetY= 0
DXF ScaleX= 0
DXF ScaleY= 0

--- LITTLEFK.p01 (plan) ---

Plan Title=Floodplain
Program Version=5.07
Short Identifier=Floodplain
Geom File=g01
Flow File=f01
Subcritical Flow
K Sum by GR= 0
Std Step Tol= 0.01
Critical Tol= 0.01
Num of Std Step Trials= 20
Max Error Tol= 0.3
Flow Tol Ratio= 0.001
Split Flow NTrial= 30
Split Flow Tol= 0.02
Split Flow Ratio= 0.02
Log Output Level= 0
Friction Slope Method= 1
Unsteady Friction Slope Method= 2
Unsteady Bridges Friction Slope Method= 1
Parabolic Critical Depth
Global Vel Dist= 0 , 0 , 0
Global Log Level= 0
CheckData=True
Encroach Param=-1 ,0,0, 0
Mapping Interval=1HOUR
Computation Time Step Use Courant=        0
Computation Time Step Use Time Series=    0
Computation Time Step Count To Double=0
Computation Time Step Max Doubling=0
Computation Time Step Max Halving=0
Computation Time Step Residence Courant=0
Run HTab= 0
Run UNet= 0
Run Sediment= 0
Run PostProcess= 0
Run WQNet= 0
Run RASMapper= 0
UNET Theta= 0
UNET Theta Warmup= 0
UNET ZTol= 0
UNET ZSATol= 0
UNET MxIter= 0
UNET Max Iter WO Improvement= 0
UNET MaxInSteps= 0
UNET DtIC= 0
UNET DtMin= 0
UNET MaxCRTS= 0
UNET WFStab= 0
UNET SFStab= 0
UNET WFX= 1
UNET SFX= 1
UNET 1D Methodology=Finite Difference
UNET DSS MLevel= 1
UNET Pardiso=0
UNET DZMax Abort= 0
UNET Use Existing IB Tables= 0
UNET Froude Reduction=False
UNET Froude Limit= 0
UNET Froude Power= 0
UNET D1 Cores= 0
UNET D2 Coriolis=0
UNET D2 Cores= 0
UNET D2 Theta= 1
UNET D2 Theta Warmup= 1
UNET D2 Z Tol= 0.01
UNET D2 Volume Tol= 0.01
UNET D2 Max Iterations= 20
UNET D2 Equation= 0
UNET D2 RampUpFraction=0.1
UNET D2 TimeSlices= 1
UNET D2 BCVolumeCheck=0
UNET D1D2 MaxIter= 0
UNET D1D2 ZTol=0.01
UNET D1D2 QTol=0.1
UNET D1D2 MinQTol=1
Write IC File= 0
Write IC File at Fixed DateTime=0
Write IC File at Sim End=0
Echo Input=False
Echo Parameters=False
Echo Output=False
Write Detailed= 0
HDF Write Warmup=0
HDF Write Time Slices=0
HDF Flush=0
HDF Face Node Velocities=0
HDF Compression= 1
HDF Chunk Size= 1
HDF Spatial Parts= 1
HDF Use Max Rows=0
HDF Fixed Rows= 1
Calibration Method= 0
Calibration Iterations= 20
Calibration Max Change=0.05
Calibration Tolerance=0.2
Calibration Maximum=1.5
Calibration Minimum=0.5
Calibration Optimization Method= 1
WQ AD Non Conservative
WQ ULTIMATE=-1
WQ Max Comp Step=1HOUR
WQ Output Interval=15MIN
WQ Output Selected Increments= 0
WQ Output face flow=0
WQ Output face velocity=0
WQ Output face area=0
WQ Output face dispersion=0
WQ Output cell volume=0
WQ Output cell surface area=0
WQ Output cell continuity=0
WQ Output cumulative cell continuity=0
WQ Output face conc=0
WQ Output face dconc_dx=0
WQ Output face courant=0
WQ Output face peclet=0
WQ Output face adv mass=0
WQ Output face disp mass=0
WQ Output cell mass=0
WQ Output cell source sink temp=0
WQ Output nsm pathways=0
WQ Output nsm derived pathways=0
WQ Output MaxMinRange=-1
WQ Daily Max Min Mean=-1
WQ Daily Range=0
WQ Daily Time=0
WQ Create Restart=0
WQ Fixed Restart=0
WQ System Summary=0
WQ Write To DSS=0
WQ Use Fixed Temperature=0
Sorting and Armoring Iterations= 10
XS Update Threshold= 0.02
Bed Roughness Predictor= 0
Hydraulics Update Threshold= 0.02
Energy Slope Method= 1
Volume Change Method= 1
Sediment Retention Method= 0
XS Weighting Method= 0
Number of US Weighted Cross Sections= 1
Number of DS Weighted Cross Sections= 1
Upstream XS Weight=0
Main XS Weight=1
Downstream XS Weight=0
Number of DS XS's Weighted with US Boundary= 1
Upstream Boundary Weight= 1
Weight of XSs Associated with US Boundary= 0
Number of US XS's Weighted with DS Boundary= 1
Downstream Boundary Weight= 0.5
Weight of XSs Associated with DS Boundary= 0.5
Percentile Method= 0
Sediment Output Level= 3
Mass or Volume Output= 0
Output Increment Type= 1
Profile and TS Output Increment= 1
XS Output Flag= 0
XS Output Increment= 10
Write Gradation File= 0
Read Gradation Hotstart= 0
Write HDF5 File= 1
Write Binary Output= 1
Write DSS Sediment File= 0
SV Curve= 0
Specific Gage Flag= 0

--- LITTLEFK.f01 (steady flow) ---

Flow Title=Flows
Program Version=5.07
Number of Profiles= 6
Profile Names=P100yr,P10yr,P25yr,P50yr,P500yr,P101yr
River Rch & RM=LITTLEFK,Main            ,37131
     489     229     324     404     716     595
River Rch & RM=LITTLEFK,Main            ,36562
     706     329     466     582    1037     859
River Rch & RM=LITTLEFK,Main            ,34405
     864     401     569     712    1272    1052
River Rch & RM=LITTLEFK,Main            ,31121
     962     446     633     792    1418    1171
River Rch & RM=LITTLEFK,Main            ,22624
    1367     631     897    1125    2022    1664
River Rch & RM=LITTLEFK,Main            ,19260
    2189    1003    1431    1799    3254    2664
River Rch & RM=LITTLEFK,Main            ,11198
    2760    1260    1801    2266    4113    3359
River Rch & RM=LITTLEFK,Main            ,5149
    3610    1642    2351    2961    5395    4394
Boundary for River Rch & Prof#=LITTLEFK,Main            , 1
Up Type= 0
Dn Type= 3
Dn Slope=0.007824
Boundary for River Rch & Prof#=LITTLEFK,Main            , 2
Up Type= 0
Dn Type= 3
Dn Slope=0.007824
Boundary for River Rch & Prof#=LITTLEFK,Main            , 3
Up Type= 0
Dn Type= 3
Dn Slope=0.007824
Boundary for River Rch & Prof#=LITTLEFK,Main            , 4
Up Type= 0
Dn Type= 3
Dn Slope=0.007824
Boundary for River Rch & Prof#=LITTLEFK,Main            , 5
Up Type= 0
Dn Type= 3
Dn Slope=0.007824
Boundary for River Rch & Prof#=LITTLEFK,Main            , 6
Up Type= 0
Dn Type= 3
Dn Slope=0.007824
DSS Import GetInterval= 0
DSS Import GetPeak= 0
DSS Import FillOption= 0

--- LITTLEFK.g01 (geometry) ---

Geom Title=Geometry
Program Version=5.07

River Reach=LITTLEFK        ,Main
Reach XY= 30
     2471569.379      548490.574     2471049.548      548418.985
     2470615.032      548895.743      2468376.33      549641.495
     2467120.821      551336.122      2466353.94      551764.233
     2465880.416      552766.292     2465205.585      553210.862
     2464669.929      554538.415     2463225.249      555014.285
     2462205.715       555994.96     2462527.462      556825.519
     2463767.649      558039.915     2463539.504      558728.655
     2463798.031       559117.22     2462811.853      560927.109
     2463436.414      561693.426     2463328.022      562225.508
     2464139.637      563161.674     2464180.465      563995.579
     2463418.281      566120.014     2463952.404      566932.084
     2462936.207      568026.231      2462898.48      568816.914
     2461898.595      569607.025     2461557.625      571225.641
     2460755.748      572075.148     2459962.639      572320.238
2459926.07747118572855.929949521     2459100.461      574248.393

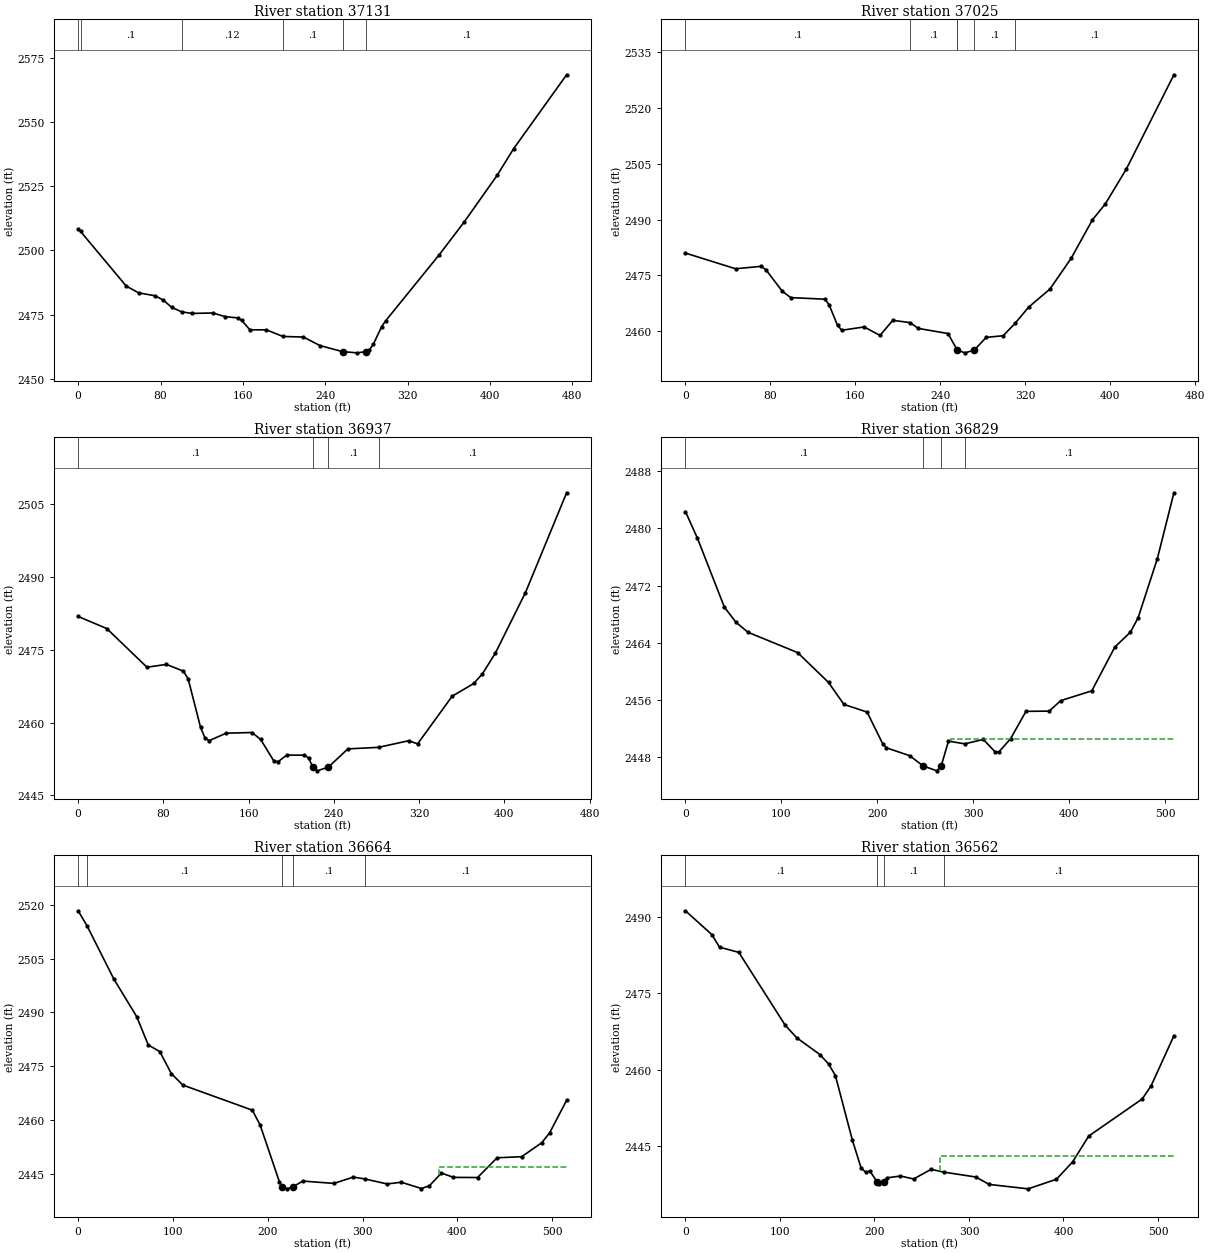
Type RM Length L Ch R = 1 ,37131   ,106.3,106.3,106.4
XS GIS Cut Line= 4
2471554.91264674548220.1793276082471561.93465944548416.795683261
2471561.93465944548592.3460008092471570.71217531548694.165184986
#Sta/Elev= 30
       02508.281    2.332507.35346.741332486.08958.748982483.47674.759182482.326
82.764282480.63590.769382477.854  100.542476.071110.78212475.468130.79492475.645
142.80252474.227154.81022473.725158.81272472.784166.81782469.087 182.8282469.096
  198.772466.516218.83692466.281234.83692462.976  256.862460.606270.83692460.137
  280.072460.607282.83692461.212286.83692463.567294.83692470.365298.83692472.659
350.83692498.341374.84632510.954 406.9652529.176423.02442539.544474.48892568.299
#Mann= 6 ,-1 , 0
       0     .12       0    2.33      .1       0  100.54     .12       0
  198.77      .1       0  256.86    .045       0  280.07      .1       0
Bank Sta=256.86,280.07
XS Rating Curve= 0 ,0
Exp/Cntr(USF)=0,0
Exp/Cntr=0.3,0.1

Type RM Length L Ch R = 1 ,37025   ,86.5,87.9,91.7
XS GIS Cut Line= 4
2471453.09346256548223.6903339582471456.60446891548441.372727718
2471454.84896573548571.2799627032471454.84896573548683.632165933
#Sta/Elev= 30
       02480.99947.206682476.795 71.20982477.44175.642082476.582 91.21242470.766
99.21344 2469.06131.21762468.648135.21812467.195143.21922461.617147.21972460.309
168.28482461.202183.22442458.927195.22592462.965  211.532462.367 219.2292460.811
247.2316 2459.43  256.012454.991  256.152454.965 263.2332454.258  271.842454.964
283.23482458.399299.23632458.848  310.42 2462.17323.23852466.521343.24032471.353
363.24072479.608383.24072489.901395.24072494.114415.24072503.557 459.9822528.798
#Mann= 6 ,-1 , 0
       0      .1       0  211.53      .1       0  256.01      .1       0
  256.15    .045       0  271.84      .1       0  310.42      .1       0
Bank Sta=256.15,271.84
XS Rating Curve= 0 ,0
Exp/Cntr(USF)=0,0
Exp/Cntr=0.3,0.1

Type RM Length L Ch R = 1 ,36937   ,112.4,108,102
XS GIS Cut Line= 4
2471382.83366117 548232.077425932471387.95270843548384.369081905
2471350.83961579548555.8571651052471370.03604302548685.113108412
#Sta/Elev= 30
       02481.87826.828592479.39164.591372471.41982.860222471.99798.869262470.601
103.31242468.968114.87832459.034118.88062456.909122.88282456.264138.89182457.823
 163.1432457.962171.32822456.528 183.6062452.115187.69872451.956195.90842453.314
212.25432453.287216.3469 2452.71  220.212450.848224.53212450.062  234.962450.848
253.18032454.588  281.93  2454.9310.2802 2456.27318.66192455.625351.12212465.454
371.34152468.065379.4292 2470.04391.56092474.296 419.8682486.798458.50942507.366
#Mann= 4 ,-1 , 0
       0      .1       0  220.21    .045       0  234.96      .1       0
  281.93      .1       0
Bank Sta=220.21,234.96
XS Rating Curve= 0 ,0
Exp/Cntr(USF)=0,0
Exp/Cntr=0.3,0.1

Type RM Length L Ch R = 1 ,36829   ,164.2,165.4,164.9
XS GIS Cut Line= 4
 2471239.5003379548174.4881442582471258.69676512548362.613131052
2471281.73247779548521.3035961022471300.92890501548679.994061153
#Sta/Elev= 30
       0 2482.3512.467132478.63240.612532468.98252.67484 2466.8665.35101 2465.46
117.00722462.622149.17332458.454165.25642455.376189.3895 2454.31205.5502 2449.91
209.59212449.309233.84372448.205  247.812446.781262.1371 2446.09  266.68 2446.78
274.26292450.249  291.182449.866310.6402 2450.48 322.7662448.757326.80792448.731
338.93372450.568355.08362454.411379.25852454.441 391.3462455.909423.67892457.278
447.75422463.407463.87092465.472471.92922467.474 492.0752475.776509.30292484.974
#Mann= 4 ,-1 , 0
       0      .1       0  247.81    .045       0  266.68      .1       0
  291.18      .1       0
#XS Ineff= 2 , 0
                          276.54         2450.61
Permanent Ineff=
       F       F
Bank Sta=247.81,266.68
XS Rating Curve= 0 ,0
Exp/Cntr(USF)=0,0
Exp/Cntr=0.3,0.1

Type RM Length L Ch R = 1 ,36664   ,104.4,101.7,98.7
XS GIS Cut Line= 4
 2471068.0122547548189.8452860372471092.32772918548343.416703828
2471123.04201274548480.3512180252471194.70867437548687.672632042
#Sta/Elev= 30
       02518.273    9.472514.03737.507072499.35461.806042488.80273.955532480.945
86.105012479.106 98.25452472.993 110.4042469.799183.64132462.821191.84012458.754
 212.3372442.826  215.442441.496220.53582440.935   226.72441.527236.93332443.097
269.72842442.445290.22532444.199  302.472443.687325.89022442.294340.83092442.773
361.99212441.025370.45662441.795383.15342445.321395.85012444.124421.24362444.078
441.8317 2449.57467.79822449.882488.95952453.754 497.4242456.579515.18012465.564
#Mann= 5 ,-1 , 0
       0      .1       0    9.47      .1       0  215.44    .045       0
   226.7      .1       0  302.47      .1       0
#XS Ineff= 2 , 0
                          381.07         2447.08
Permanent Ineff=
       F       F
Bank Sta=215.44,226.7
XS Rating Curve= 0 ,0
Exp/Cntr(USF)=0,0
Exp/Cntr=0.3,0.1

Type RM Length L Ch R = 1 ,36562   ,160.8,161.1,164.5
XS GIS Cut Line= 4
 2470956.6729768548243.5952822642470989.94678399548402.285747314
2471041.13725658548490.5893125442471129.44082181548727.345248305
#Sta/Elev= 30
       02491.25327.88916 2486.5836.063132484.09356.498042483.065105.54182468.738
117.80282466.258142.3247 2462.96151.54912461.097158.67262458.826176.71142446.082
185.95842440.614 190.5822439.847195.3632 2439.99  202.87 2437.88204.45252437.441
209.9973  2437.9213.69962438.712227.57022439.063241.44082438.481259.93492440.373
   273.42439.828307.22332438.868321.66382437.398362.72242436.538392.60662438.428
409.68322441.827426.75992446.925483.35412454.225492.68242456.778516.89722466.655
#Mann= 4 ,-1 , 0
       0      .1       0  202.87    .045       0209.9973      .1       0
   273.4      .1       0
#XS Ineff= 2 , 0
                          269.14         2442.92
Permanent Ineff=
       F       F
Bank Sta=202.87,209.9973
XS Rating Curve= 0 ,0
Exp/Cntr(USF)=0,0
Exp/Cntr=0.3,0.1

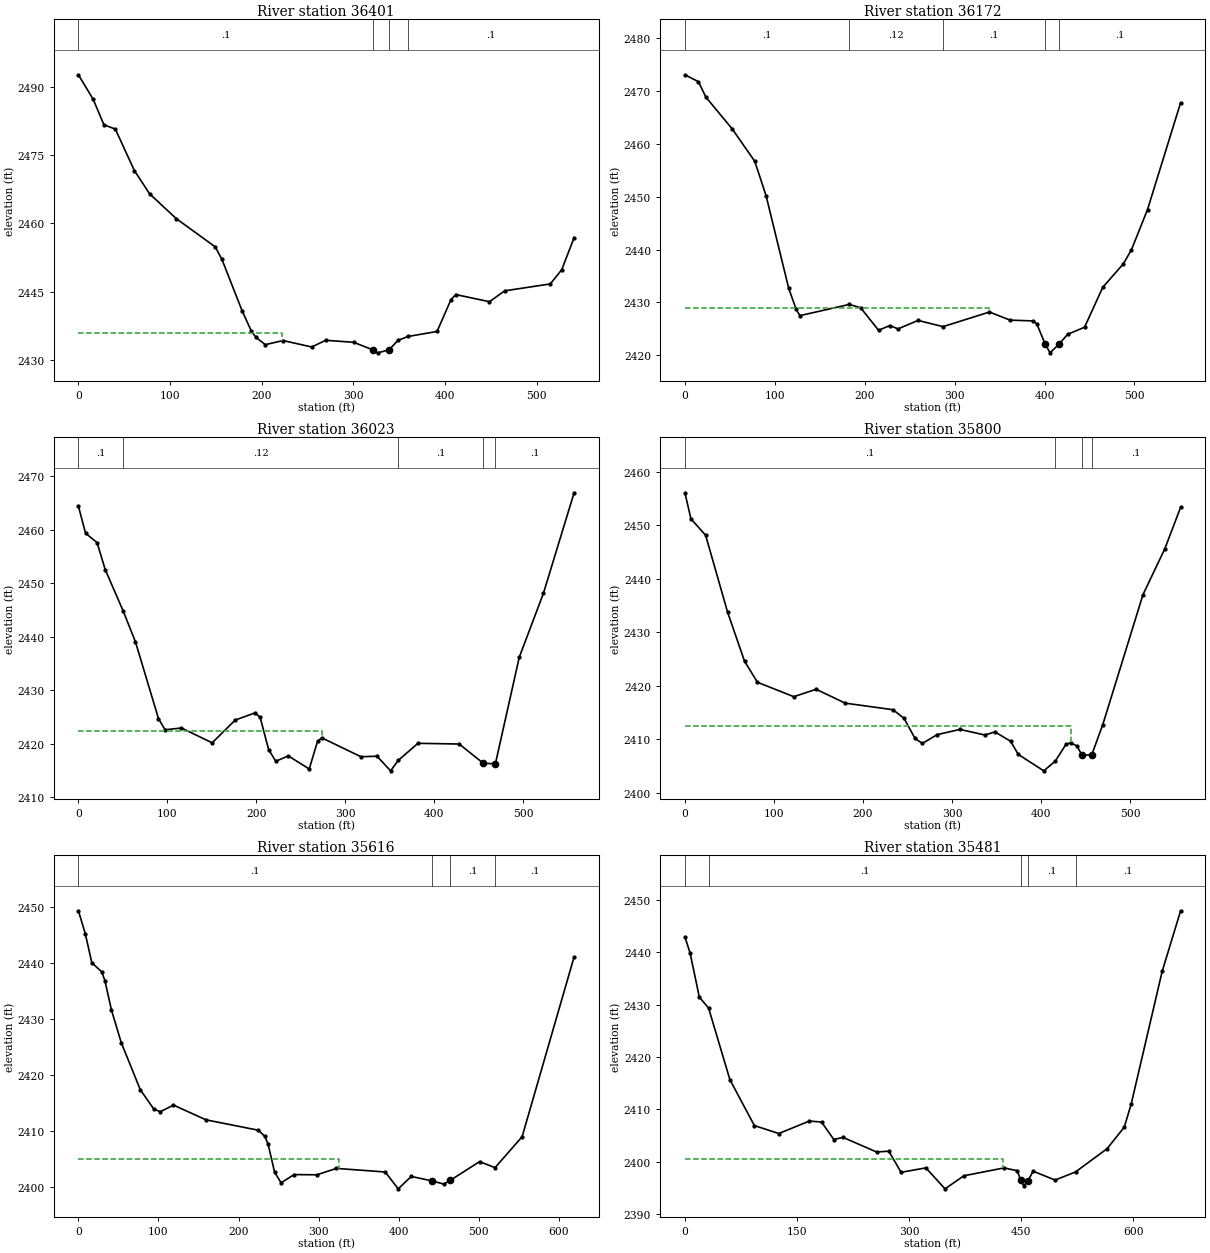
Type RM Length L Ch R = 1 ,36401   ,227.5,229,228
XS GIS Cut Line= 4
2470805.66108264548296.0655166762470851.73250797548461.154790801
2470997.62535488548649.2797775942471032.17892388548775.976197272
#Sta/Elev= 30
       02492.57416.160222487.18427.850352481.59440.308872480.65461.073072471.557
77.684432466.448106.75432461.016149.27762454.813156.58842452.062178.65622440.763
188.77992436.283193.84182434.929203.96562433.353223.24792434.253254.58442432.842
269.7701 2434.31300.32932433.869  321.232432.209326.43792431.556  338.922432.209
348.68952434.298  359.622435.147391.25522436.246406.44092443.217 411.6882444.348
448.44882442.772465.0331 2445.16514.78632446.677527.22452449.773540.78782456.815
#Mann= 4 ,-1 , 0
       0      .1       0  321.23    .045       0  338.92      .1       0
  359.62      .1       0
#XS Ineff= 2 , 0
          222.22 2435.81
Permanent Ineff=
       F       F
Bank Sta=321.23,338.92
XS Rating Curve= 0 ,0
Exp/Cntr(USF)=0,0
Exp/Cntr=0.3,0.1

Type RM Length L Ch R = 1 ,36172   ,147.6,149,148.7
XS GIS Cut Line= 5
2470629.05395218548380.5297964612470684.08371022548560.976212365
   2470768.54799548706.8690592662470835.09560438 548801.57143357
2470869.64917338548871.958333391
#Sta/Elev= 30
       02473.02115.014052471.71823.377792468.78252.650892462.78477.742132456.657
90.287742450.161 115.3792432.716123.74272428.694127.92462427.516  182.82 2429.63
195.4854    2429215.41792424.746227.83932425.635237.08332425.013259.32692426.612
   287.12425.438338.76732428.196361.69412426.668 387.5352426.512391.47862425.938
  400.43 2422.25406.14512420.486   416.52422.197425.70042423.979444.53762425.333
 464.8112432.876487.81392437.333496.72592439.979514.54992447.553 551.387 2467.75
#Mann= 5 ,-1 , 0
       0      .1       0  182.82     .12       0   287.1      .1       0
  400.43    .045       0   416.5      .1       0
#XS Ineff= 2 , 0
          338.27 2428.97
Permanent Ineff=
       F       F
Bank Sta=400.43,416.5
XS Rating Curve= 0 ,0
Exp/Cntr(USF)=0,0
Exp/Cntr=0.3,0.1

Type RM Length L Ch R = 1 ,36023   ,218.6,223.3,225.6
XS GIS Cut Line= 3
2470475.48253439548439.3988399472470547.14919602548617.285732221
2470739.11346826548928.267853248
#Sta/Elev= 30
       02464.4398.0771992459.36721.014462457.61430.138582452.579   50.162444.902
64.138662439.06390.013182424.71197.410282422.611115.88772422.939150.38712420.167
176.26162424.422198.62652425.766204.27962424.941213.85682418.899221.87132416.724
235.97342417.716 259.4772415.275268.8784 2420.47273.57912421.099317.63482417.567
 335.6992417.663350.92932414.926  359.622416.887381.69532420.076428.08342419.942
  455.25 2416.33 468.7752416.249 495.6172436.189522.71642448.114557.23962466.939
#Mann= 5 ,-1 , 0
       0      .1       0   50.16     .12       0  359.62      .1       0
  455.25    .045       0 468.775      .1       0
#XS Ineff= 2 , 0
          274.07  2422.4
Permanent Ineff=
       F       F
Bank Sta=455.25,468.775
XS Rating Curve= 0 ,0
Exp/Cntr(USF)=0,0
Exp/Cntr=0.3,0.1

Type RM Length L Ch R = 1 ,35800   ,181.9,183.3,181.6
XS GIS Cut Line= 4
2470374.38135101548480.3512180252470456.28610716548805.410719015
2470497.23848524548958.9821368062470508.75634157549020.410703922
#Sta/Elev= 30
       02456.1216.7440572451.24523.244152448.16847.994282433.72766.973242424.573
81.467412420.643122.24472417.946 147.3642419.332 179.9952416.737233.62032415.506
245.99542413.906258.37042410.143266.62052409.185283.12052410.837308.81062411.814
336.75132410.778348.24262411.349365.72982409.596374.38862407.128402.98782404.063
   415.92405.879427.82652409.005433.21712409.308440.24582408.723   445.8 2407.01
456.80492407.043469.22432412.707514.41312437.067538.83132445.605556.65642453.406
#Mann= 4 ,-1 , 0
       0      .1       0   415.9      .1       0   445.8    .045       0
456.8049      .1       0
#XS Ineff= 2 , 0
          433.22 2412.51
Permanent Ineff=
       F       F
Bank Sta=445.8,456.8049
XS Rating Curve= 0 ,0
Exp/Cntr(USF)=0,0
Exp/Cntr=0.3,0.1

Type RM Length L Ch R = 1 ,35616   ,137.2,135.6,134.9
XS GIS Cut Line= 4
2470228.48850411548494.428597989  2470270.720644548708.148821081
 2470321.9111166548996.0952294392470344.94682927549102.315460077
#Sta/Elev= 30
       02449.291 8.62591  2445.216.780612440.00829.012652438.423   33.092436.856
41.244692431.60453.476732425.79577.21498  2417.494.250212413.907102.40492413.462
118.71432414.634159.4878    2412224.70072410.153232.82612409.063236.88882407.657
245.01432402.667253.13972400.774269.39062402.242297.8296  2402.2322.20592403.344
383.14672402.703399.39762399.698415.64842401.913441.00522401.131456.27562400.545
 464.4012401.213500.96552404.552  520.282403.476554.1046    2409619.00352441.061
#Mann= 4 ,-1 , 0
       0      .1       0441.0052    .045       0 464.401      .1       0
  520.28      .1       0
#XS Ineff= 2 , 0
          325.51 2404.94
Permanent Ineff=
       F       F
Bank Sta=441.0052,464.401
XS Rating Curve= 0 ,0
Exp/Cntr(USF)=0,0
Exp/Cntr=0.3,0.1

Type RM Length L Ch R = 1 ,35481   ,155.5,157.2,158.1
XS GIS Cut Line= 4
2470068.51827724548520.0238342872470129.94684436 548806.69048083
2470206.73255325549040.8868929612470268.16112037549148.386885414
#Sta/Elev= 30
       02442.9347.0229322439.77219.295352431.421   31.682429.32860.203412415.657
92.929862406.902125.6563 2405.38166.56442407.761182.84182407.573199.29082404.239
211.56322404.645256.56212401.853272.9253 2402.01289.28852397.974322.49692398.825
348.1089 2394.82 373.3662397.314427.11112398.816444.92762398.278449.30192396.467
453.34662395.441458.81232396.247465.9752 2398.19495.44172396.496  522.782398.045
564.98052402.481 588.0232406.596597.22962410.976638.69262436.314663.45062447.905
#Mann= 5 ,-1 , 0
       0     .12       0   31.68      .1       0449.3019    .045       0
458.8123      .1       0  522.78      .1       0
#XS Ineff= 2 , 0
          426.34 2400.52
Permanent Ineff=
       F       F
Bank Sta=449.3019,458.8123
XS Rating Curve= 0 ,0
Exp/Cntr(USF)=0,0
Exp/Cntr=0.3,0.1

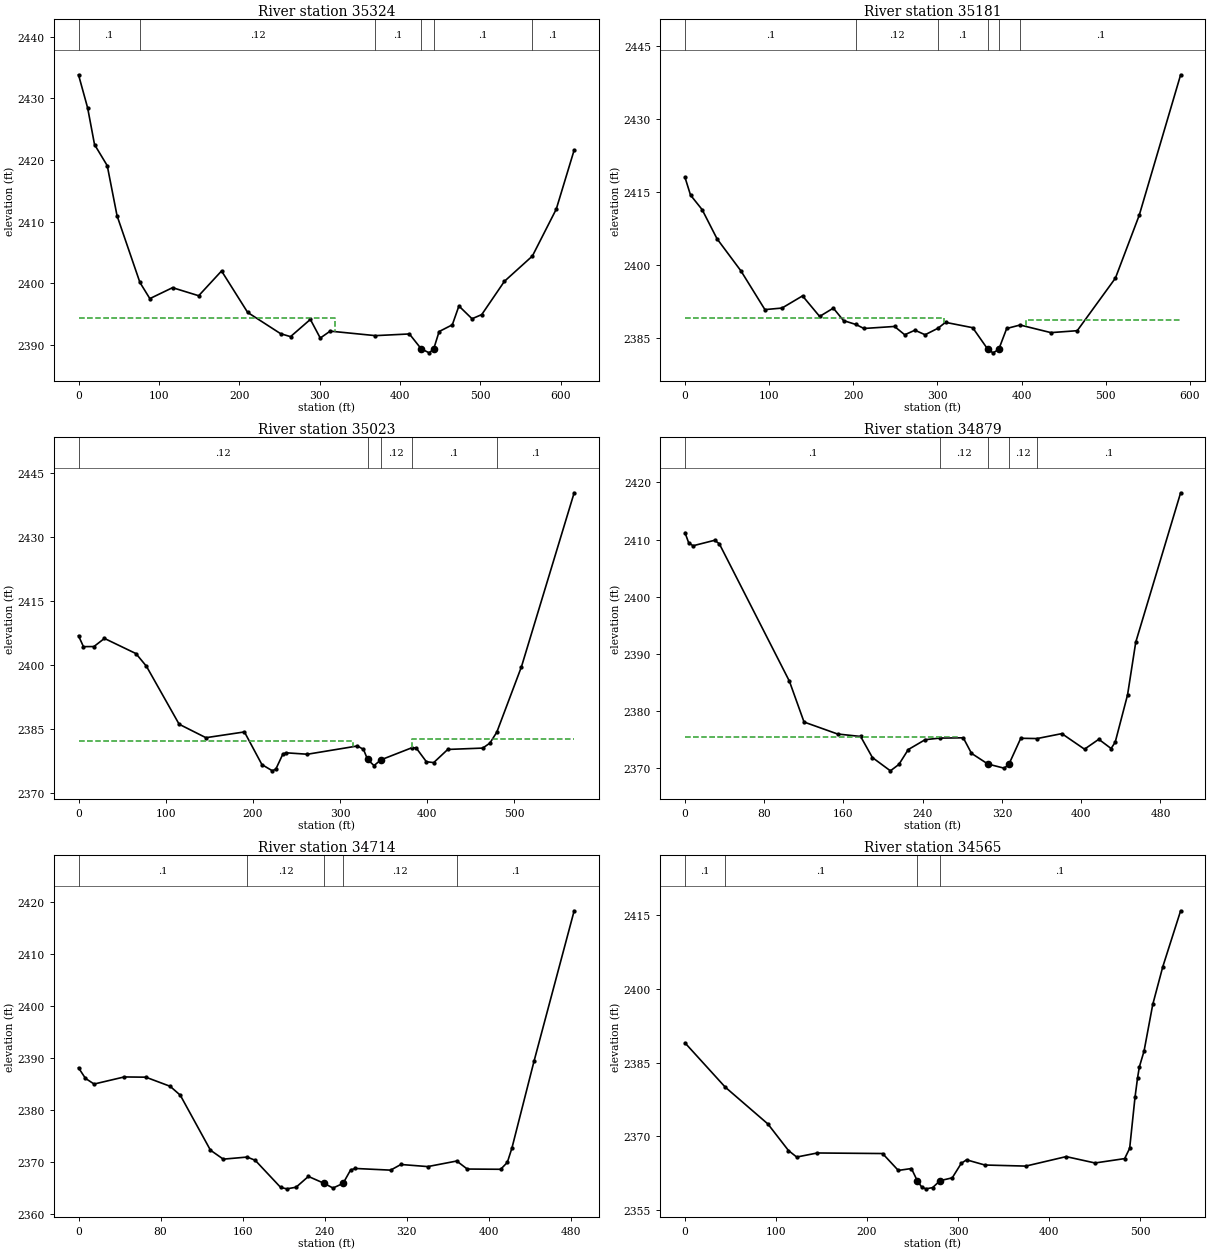
Type RM Length L Ch R = 1 ,35324   ,141.4,142.9,144
XS GIS Cut Line= 4
2469950.78019027548591.6904959232469989.17304472  548804.1309572
2470050.60161183549065.2023674452470067.23851543549197.017834382
#Sta/Elev= 30
       02433.81611.381812428.43419.937352422.503 35.77062419.08247.964982410.966
   76.43 2400.1588.790032397.531117.06652399.305149.58492397.998178.03852402.012
210.55692395.289 251.5912391.842263.91872391.366288.57412394.159300.90182391.137
313.22952392.258  369.512391.529411.85122391.802  426.542389.389436.5066 2388.74
  442.142389.389448.83432392.191465.27122393.284473.48972396.335489.81642394.264
501.91162394.943530.13372400.334  564.93 2404.43594.6415 2412.03 616.9442421.612
#Mann= 6 ,-1 , 0
       0      .1       0   76.43     .12       0  369.51      .1       0
  426.54    .045       0  442.14      .1       0  564.93      .1       0
#XS Ineff= 2 , 0
          319.75 2394.39
Permanent Ineff=
       F       F
Bank Sta=426.54,442.14
XS Rating Curve= 0 ,0
Exp/Cntr(USF)=0,0
Exp/Cntr=0.3,0.1

Type RM Length L Ch R = 1 ,35181   ,157.6,157.8,157.6
XS GIS Cut Line= 4
2469844.55995963548677.434537523  2469876.554005548855.321429797
 2469918.7861449549159.9047417492469931.58376304549259.726163313
#Sta/Elev= 30
       02418.0196.5804852414.37920.359052411.40438.057342405.42466.506612398.827
94.955882390.894115.27682391.212139.66192393.707159.98282389.492176.23952391.196
 188.3832388.638  203.082387.845212.61262387.023 248.9572387.438261.07182385.735
273.18662386.665285.30152385.737  300.622387.075 309.5312388.281341.83722387.183
  359.882382.735366.06682382.028  372.772382.736382.21982387.021  398.162387.735
434.71732386.174466.02392386.569511.41272397.358539.64182410.222588.8768 2439.05
#Mann= 6 ,-1 , 0
       0      .1       0  203.08     .12       0  300.62      .1       0
  359.88    .045       0  372.77      .1       0  398.16      .1       0
#XS Ineff= 2 , 0
          307.82 2389.08  404.94         2388.86
Permanent Ineff=
       F       F
Bank Sta=359.88,372.77
XS Rating Curve= 0 ,0
Exp/Cntr(USF)=0,0
Exp/Cntr=0.3,0.1

Type RM Length L Ch R = 1 ,35023   ,145.9,144.1,142.1
XS GIS Cut Line= 4
2469720.42306358548713.267868341 2469747.2980617549012.732133033
 2469765.2147271549161.1845035642469779.29210707549278.922590536
#Sta/Elev= 30
       02406.8885.6456042404.32417.693832404.34629.742062406.25565.886732402.697
77.934962399.722115.47852386.104146.20832382.943190.38512384.296210.46552376.625
222.5137 2375.16226.52982375.609234.56192379.125 238.5782379.391262.67442379.059
320.08662380.998327.01632380.194   331.72377.842339.10342376.394     3472377.742
   382.42380.571387.45182380.545399.17952377.299407.59692377.095 423.7132380.184
463.90382380.503472.05842381.675  479.98 2384.23508.31482399.623568.77412440.455
#Mann= 5 ,-1 , 0
       0     .12       0   331.7    .045       0     347     .12       0
   382.4      .1       0  479.98      .1       0
#XS Ineff= 2 , 0
          315.23 2382.25  382.72         2382.55
Permanent Ineff=
       F       F
Bank Sta=331.7,347
XS Rating Curve= 0 ,0
Exp/Cntr(USF)=0,0
Exp/Cntr=0.3,0.1

Type RM Length L Ch R = 1 ,34879   ,167.8,165.1,162.6
XS GIS Cut Line= 4
2469486.22665145548787.4940536062469597.56592935549024.249989367
2469625.72068928549127.9106963762469660.27425828549254.607116053
#Sta/Elev= 30
       02411.2253.7536852409.4428.1739192408.93430.000362409.89334.695322409.271
105.41912385.257120.19262378.119154.04162376.027177.31442375.597189.20512371.911
207.37852369.587215.92492370.704225.41692373.308242.44632375.031   257.22375.311
280.94532375.362289.23522372.645305.81482370.775322.39452370.043 327.1712370.796
338.97422375.279  355.482375.231380.42652376.092403.34312373.373417.74132375.104
430.17962373.489434.32572374.604 446.7642382.851455.05622392.077500.36912418.194
#Mann= 5 ,-1 , 0
       0      .1       0   257.2     .12       0305.8148    .045       0
 327.171     .12       0  355.48      .1       0
#XS Ineff= 2 , 0
          275.72  2375.5
Permanent Ineff=
       F       F
Bank Sta=305.8148,327.171
XS Rating Curve= 0 ,0
Exp/Cntr(USF)=0,0
Exp/Cntr=0.3,0.1

Type RM Length L Ch R = 1 ,34714   ,148.8,148.7,145.5
XS GIS Cut Line= 4
2469364.64927903 548892.434522432469408.16118074549026.809512997
2469474.70879512549166.3035508232469561.73259853549332.672586763
#Sta/Elev= 30
       02388.0966.7863982386.06315.195362384.97644.62671 2386.34 65.64912386.293
89.367652384.54599.284932382.833128.71632372.271141.24422370.549  164.512370.951
172.35742370.333197.25162365.111203.25252364.847212.24422365.156224.25572367.231
 239.2582365.935248.25942365.004   258.12365.892265.42662368.465269.85852368.762
304.50722368.438314.51852369.525340.71882369.121  368.98 2370.19379.2488 2368.65
411.85122368.604418.34442369.927422.8586  2372.7444.45352389.409483.55362418.256
#Mann= 5 ,-1 , 0
       0      .1       0  164.51     .12       0 239.258    .045       0
   258.1     .12       0  368.98      .1       0
Bank Sta=239.258,258.1
XS Rating Curve= 0 ,0
Exp/Cntr(USF)=0,0
Exp/Cntr=0.3,0.1

Type RM Length L Ch R = 1 ,34565   ,158.3,160.1,158.4
XS GIS Cut Line= 4
2469189.32191039548942.3452332122469284.02428469549121.511887301
2469356.97070814549230.291641569 2469490.0659369 549394.10115388
#Sta/Elev= 30
       02389.004   44.22 2379.9991.105192372.491113.72722367.079 122.776 2365.75
 145.3982366.579217.14182366.465234.43912363.026248.85362363.412  255.21 2360.96
260.38512359.565 264.9962359.275272.17792359.528  280.24 2360.93293.7237 2361.52
303.62842364.468309.39422365.185329.53492364.127374.50272363.906418.90542365.838
450.62162364.542  483.182365.433488.68112367.526 494.5542377.919497.39762381.924
499.32592384.099504.47972387.326 514.0542396.831525.09532404.517544.69332415.906
#Mann= 4 ,-1 , 0
       0      .1       0   44.22      .1       0  255.21    .045       0
  280.24      .1       0
Bank Sta=255.21,280.24
XS Rating Curve= 0 ,0
Exp/Cntr(USF)=0,0
Exp/Cntr=0.3,0.1

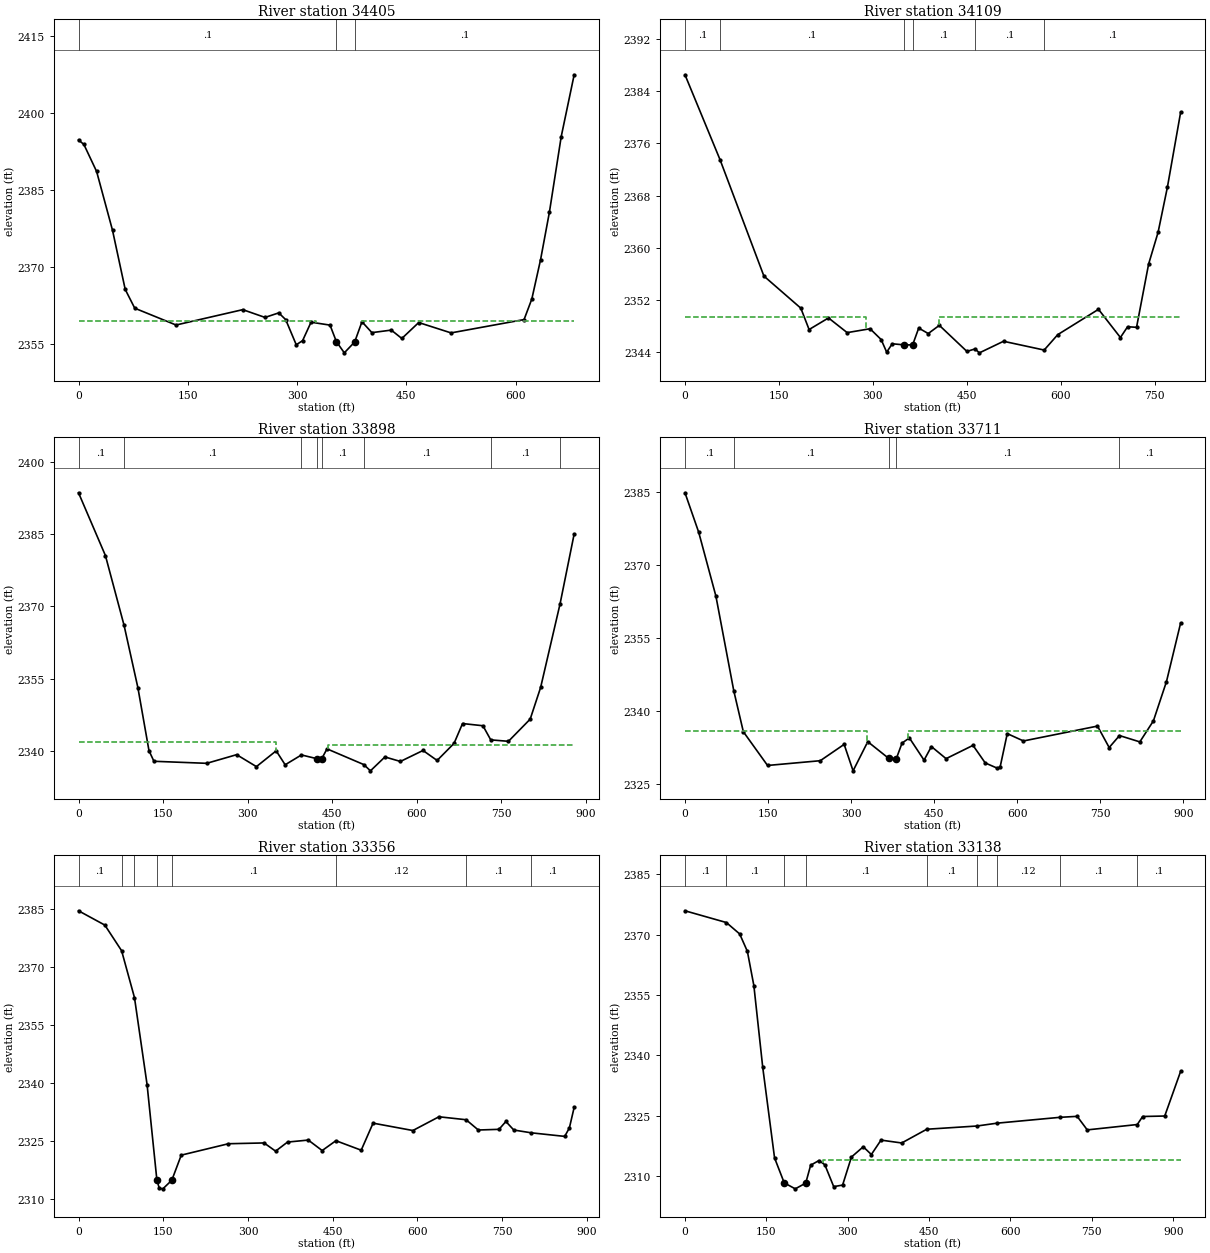
Type RM Length L Ch R = 1 ,34405   ,293,296.2,297.3
XS GIS Cut Line= 4
2469057.50644345548964.1011840652469159.88738865549199.577358011
2469275.06595199 549381.30353573  2469413.280228549537.434477151
#Sta/Elev= 30
       02394.7477.4036762393.85724.850542388.59346.659132377.124  64.1062365.581
77.191152361.914133.89352358.633225.4895 2361.63256.02152360.115274.9003    2361
284.43092359.682298.92392354.776307.61972355.583319.2141 2359.18345.30152358.613
353.99732355.396364.87952353.204379.08682355.315389.1314 2359.27402.76552357.145
429.36112357.642443.85412356.007467.04292359.116511.43742357.094 611.6692359.696
622.30452363.704634.30682371.373646.4431 2380.64662.67492395.404680.44112407.458
#Mann= 3 ,-1 , 0
       0      .1       0353.9973    .045       0379.0868      .1       0
#XS Ineff= 2 , 0
          325.51 2359.41  389.85         2359.41
Permanent Ineff=
       F       F
Bank Sta=353.9973,379.0868
XS Rating Curve= 0 ,0
Exp/Cntr(USF)=0,0
Exp/Cntr=0.3,0.1

Type RM Length L Ch R = 1 ,34109   ,213.8,210.4,208.1
XS GIS Cut Line= 4
2468830.98860221549083.1190328542468888.57788388549259.726163313
2468985.83978182549465.7678155152469212.35762306549767.791603837
#Sta/Elev= 30
       02386.534   55.932373.521125.9788 2355.67 184.881 2350.75198.10572347.472
229.06852349.252258.87612346.999295.41752347.593313.11062345.938321.95722343.999
330.80372345.289  350.01 2345.12  363.38 2345.12373.05982347.695388.30622346.858
405.99922348.115450.00772344.118  462.822344.496470.0077  2343.9 508.4462345.672
  573.322344.327595.00772346.691660.00772350.571695.0077 2346.25706.48132347.902
 720.7672347.814740.00772357.505755.11262362.366770.00772369.296791.13362380.782
#Mann= 6 ,-1 , 0
       0      .1       0   55.93      .1       0  350.01    .045       0
  363.38      .1       0  462.82      .1       0  573.32      .1       0
#XS Ineff= 2 , 0
          288.61 2349.41  406.04         2349.41
Permanent Ineff=
       F       F
Bank Sta=350.01,363.38
XS Rating Curve= 0 ,0
Exp/Cntr(USF)=0,0
Exp/Cntr=0.3,0.1

Type RM Length L Ch R = 1 ,33898   ,184.5,187,188.3
XS GIS Cut Line= 4
2468610.86957004549193.1785489372468722.20884794549436.333293772
2468978.16121093549775.4701747272469113.81596331549904.726118034
#Sta/Elev= 30
       02393.52847.740262380.542    80.82366.122105.38752353.195125.06642340.159
133.86522337.963227.5205 2337.54280.6604 2339.33315.73982336.857350.81922340.128
366.74392337.238  395.652339.274423.8624 2338.48  431.66 2338.49441.02342340.531
  506.32 2337.28 518.1082335.985543.81132338.857571.31832337.928611.40912340.198
636.46582338.132666.53382341.672681.56792345.772717.78282345.317  731.632342.394
763.05082342.096801.64932346.689820.19892353.255  854.652370.533879.69112385.007
#Mann= 8 ,-1 , 0
       0      .1       0    80.8      .1       0  395.65      .1       0
423.8624    .045       0  431.66      .1       0  506.32      .1       0
  731.63      .1       0  854.65      .1       0
#XS Ineff= 2 , 0
          351.17 2341.88  443.07         2341.37
Permanent Ineff=
       F       F
Bank Sta=423.8624,431.66
XS Rating Curve= 0 ,0
Exp/Cntr(USF)=0,0
Exp/Cntr=0.3,0.1

Type RM Length L Ch R = 1 ,33711   ,357.1,354.9,341.5
XS GIS Cut Line= 4
2468471.37553222549309.6368740952468614.70885549 549547.67257167
2468760.60170239549858.6546926972468961.52430733 550044.22015586
#Sta/Elev= 30
       02384.76824.809762376.64555.826522363.537   88.162344.039105.37012335.659
 149.085 2328.73244.26182329.707287.36182333.063 303.5052327.625330.01492333.616
367.52072330.214381.54152330.122391.87112333.323 405.126 2334.39431.6359 2329.82
444.89082332.614471.40062330.129 520.0022332.862542.09352329.247 564.1852328.152
569.01762328.433581.85822335.275611.12152333.764744.76432336.821765.84872332.416
  784.482334.875821.19212333.574845.74222337.901869.32452345.975894.8661 2358.01
#Mann= 5 ,-1 , 0
       0      .1       0   88.16      .1       0367.5207    .045       0
381.5415      .1       0  784.48      .1       0
#XS Ineff= 2 , 0
          327.85 2335.89  401.92         2335.89
Permanent Ineff=
       F       F
Bank Sta=367.5207,381.5415
XS Rating Curve= 0 ,0
Exp/Cntr(USF)=0,0
Exp/Cntr=0.3,0.1

Type RM Length L Ch R = 1 ,33356   ,218.5,218.2,218.5
XS GIS Cut Line= 4
2468275.57197453549529.7559062612468320.36363806549600.142806082
2468548.16124111549835.6189800282468854.02431488550187.553479132
#Sta/Elev= 30
       02384.448 46.58192380.758   76.272374.145   99.062362.047121.3732  2339.6
138.63222315.115142.9077 2312.86149.29182312.719165.16922314.944181.86542321.413
265.34622324.354328.48072324.558 348.827 2322.44369.93942324.781 406.7142325.299
431.29282322.595  455.612325.134500.36732322.687521.38492329.664591.83422327.763
637.97482331.308  686.032330.547707.69232327.894744.2791 2328.07756.47472330.092
770.46322327.893  801.242327.173860.55542326.249 868.867 2328.43877.33182333.744
#Mann= 8 ,-1 , 0
       0      .1       0   76.27      .1       0   99.06      .1       0
138.6322    .045       0165.1692      .1       0  455.61     .12       0
  686.03      .1       0  801.24      .1       0
Bank Sta=138.6322,165.1692
XS Rating Curve= 0 ,0
Exp/Cntr(USF)=0,0
Exp/Cntr=0.3,0.1

Type RM Length L Ch R = 1 ,33138   ,245.5,241,236
XS GIS Cut Line= 4
2468104.08389133549679.4880386072468180.86960023549770.351127467
2468421.46482144549993.029683263 2468778.5183678 550293.77370977
#Sta/Elev= 30
       02375.939   76.22 2373.02100.80792370.181114.9998 2365.86126.96852357.352
143.31942337.027165.12062314.511182.94382308.306203.27272306.821222.57142308.244
231.64512312.692246.87512313.851257.77572312.813274.12662307.373290.53342307.752
306.82832314.727328.62952317.276343.53292315.355361.33132318.935399.48342318.219
  445.682321.636  538.182322.438  574.992323.141  690.54 2324.59722.87932324.842
741.50652321.474   833.72322.807843.61042324.802884.3148 2324.92 913.6262336.023
#Mann= 9 ,-1 , 0
       0      .1       0   76.22      .1       0182.9438    .045       0
222.5714      .1       0  445.68      .1       0  538.18      .1       0
  574.99     .12       0  690.54      .1       0   833.7      .1       0
#XS Ineff= 2 , 0
                          253.77         2314.02
Permanent Ineff=
       F       F
Bank Sta=182.9438,222.5714
XS Rating Curve= 0 ,0
Exp/Cntr(USF)=0,0
Exp/Cntr=0.3,0.1

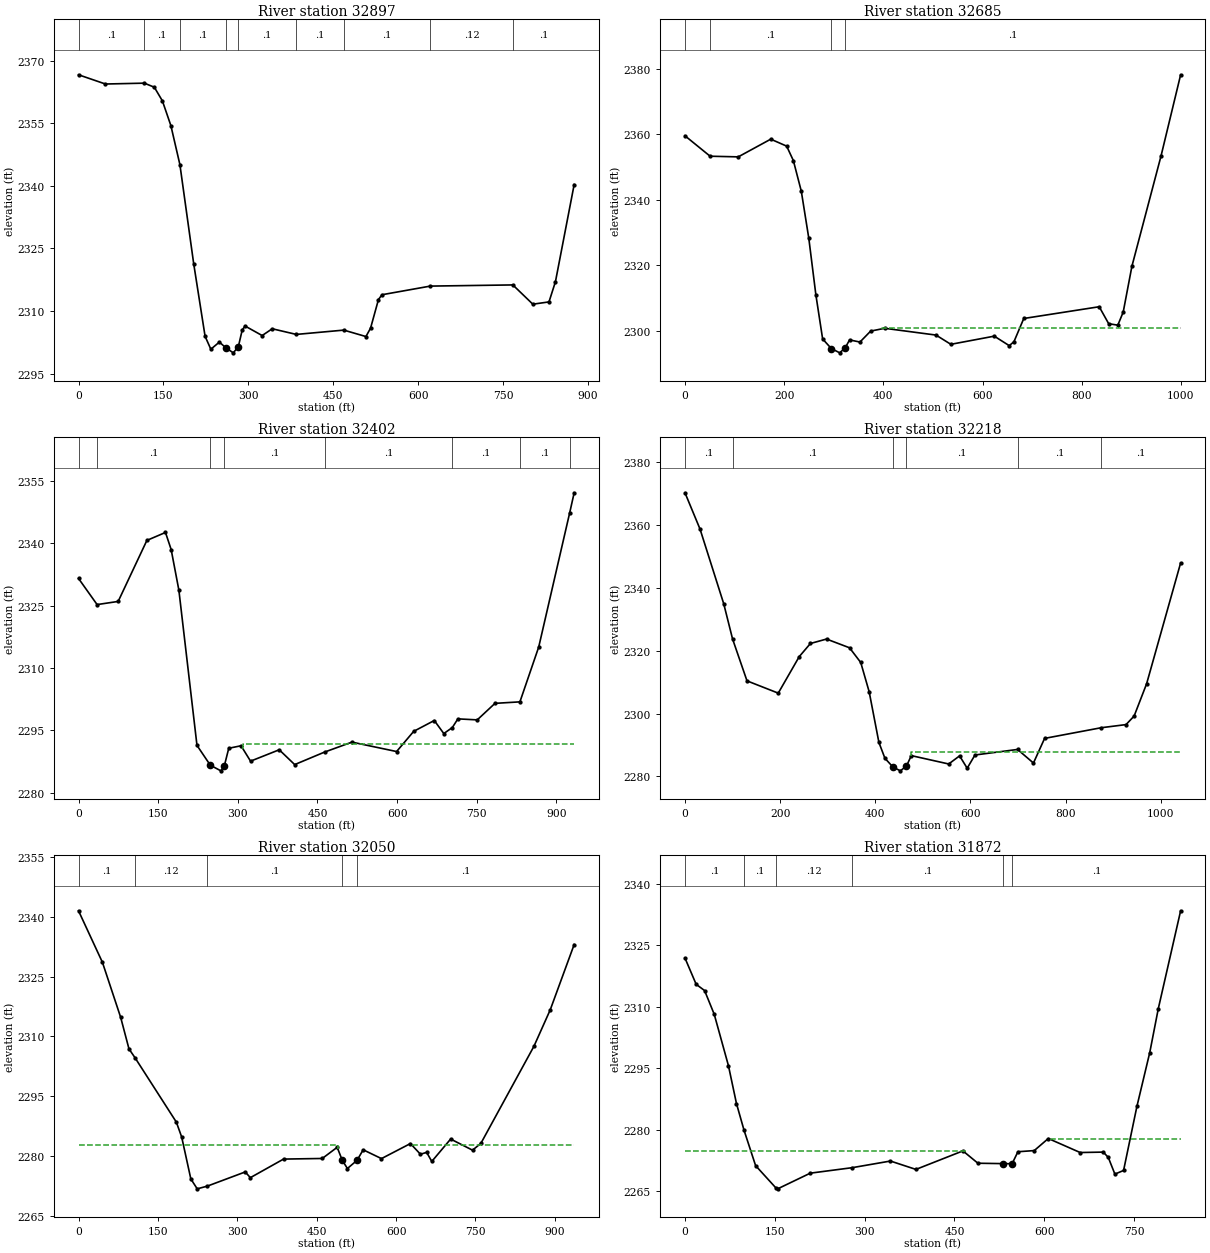
Type RM Length L Ch R = 1 ,32897   ,208.3,211.9,213.1
XS GIS Cut Line= 4
2467942.83390265 549877.851119922468050.33389511 549971.27373241
 2468384.3517288550227.226095394 2468607.0302846550446.065365746
#Sta/Elev= 30
       02366.59347.577092364.381  116.312364.587 133.9362363.605148.14842360.341
163.0974 2354.44   179.12345.058203.41222321.362223.56962303.943233.74082300.851
248.76632302.564260.16692301.211273.31962299.988282.24322301.436289.08112305.427
294.12052306.417324.35662304.131342.15792305.754  384.672304.401  468.592305.432
507.63662303.891515.85192305.906529.79732312.764536.00932313.906  621.312315.975
  767.092316.256 802.433 2311.64830.96642312.187842.37982317.029875.44232340.303
#Mann= 9 ,-1 , 0
       0      .1       0  116.31      .1       0   179.1      .1       0
260.1669    .045       0282.2432      .1       0  384.67      .1       0
  468.59      .1       0  621.31     .12       0  767.09      .1       0
#XS Ineff= 2 , 0
                          294.92         2306.24
Permanent Ineff=
       F       F
Bank Sta=260.1669,282.2432
XS Rating Curve= 0 ,0
Exp/Cntr(USF)=0,0
Exp/Cntr=0.3,0.1

Type RM Length L Ch R = 1 ,32685   ,285,282.9,279.8
XS GIS Cut Line= 4
  2467745.941933549961.0215938652467919.73674737550096.195338377
2468242.74933166 550456.073489352468458.67622225 550657.95635453
#Sta/Elev= 30
       0 2359.51   50.692353.284107.43382353.089172.93072358.481205.01872356.357
218.53772351.951234.54592342.622 249.7062328.224263.86872311.101277.54532297.608
295.02672294.698 312.022 2293.38323.35222294.984331.84982297.321352.79432296.668
374.38692300.007402.66342300.858506.13112298.792536.07292295.975 623.6022298.464
653.7903 2295.57663.25762296.756683.08542303.845835.17142307.425854.30212302.252
872.71552301.811883.5867 2305.81901.15742319.777959.72662353.298999.35682378.098
#Mann= 4 ,-1 , 0
       0      .1       0   50.69      .1       0295.0267    .045       0
323.3522      .1       0
#XS Ineff= 2 , 0
                          397.81         2301.03
Permanent Ineff=
       F       F
Bank Sta=295.0267,323.3522
XS Rating Curve= 0 ,0
Exp/Cntr(USF)=0,0
Exp/Cntr=0.3,0.1

Type RM Length L Ch R = 1 ,32402   ,186.4,183.6,182.7
XS GIS Cut Line= 4
2467586.19114403550194.5035162042467698.54334726550284.034178153
 2468004.0008998550508.7385846142468312.96945868550779.086073637
#Sta/Elev= 30
       02331.558   34.99 2325.2774.677292326.027128.75972340.709163.77532342.622
  174.462338.517188.98462328.756223.0979 2291.39248.19272286.632268.05562285.272
274.59672286.467282.95282290.702306.06832291.305323.9904  2287.6377.99272290.339
 407.0962286.774  463.312289.782514.92492292.179599.02782289.915 631.2212294.774
670.02022297.381687.9151 2294.24  703.962295.688714.44082297.775 750.8872297.531
784.29512301.508  831.252301.868866.6779 2315.07  924.842347.269933.41452352.167
#Mann= 8 ,-1 , 0
       0      .1       0   34.99      .1       0248.1927    .045       0
274.5967      .1       0  463.31      .1       0  703.96      .1       0
  831.25      .1       0  924.84      .1       0
#XS Ineff= 2 , 0
                          310.01         2291.81
Permanent Ineff=
       F       F
Bank Sta=248.1927,274.5967
XS Rating Curve= 0 ,0
Exp/Cntr(USF)=0,0
Exp/Cntr=0.3,0.1

Type RM Length L Ch R = 1 ,32218   ,167,168,169.4
XS GIS Cut Line= 4
2467368.50875027550284.0341781532467663.43328375550484.161540157
2468039.11096331550701.8439339162468228.70530626550866.861232411
#Sta/Elev= 30
       02370.33231.706412358.74581.421782335.014  100.032323.783130.37872310.442
196.06172306.533240.17162318.156263.73742322.346297.57522323.756 345.9152320.974
369.48822316.292 387.1782306.985407.66692290.842420.34112285.784436.93672283.057
 452.7022281.793465.57752283.318475.8169 2286.64554.40772283.977577.27482286.559
593.23162282.625609.62852286.838  699.142288.604732.56162284.276755.97742292.125
  874.832295.516927.17572296.519 944.1872299.234970.41622309.5091041.9532347.989
#Mann= 6 ,-1 , 0
       0      .1       0  100.03      .1       0436.9367    .045       0
465.5775      .1       0  699.14      .1       0  874.83      .1       0
#XS Ineff= 2 , 0
                          475.82         2287.75
Permanent Ineff=
       F       F
Bank Sta=436.9367,465.5775
XS Rating Curve= 0 ,0
Exp/Cntr(USF)=0,0
Exp/Cntr=0.3,0.1

Type RM Length L Ch R = 1 ,32050   ,172.5,178,180.2
XS GIS Cut Line= 4
2467261.42305657 550401.652890912467621.30120754550643.912329126
2467844.25011083550794.885602217 2468011.0229125550958.147397536
#Sta/Elev= 30
       02341.45845.194542328.54379.655212314.76995.335122306.877  107.28 2304.55
184.82512288.542194.9305  2284.8212.22182274.309 224.2682271.829  243.432272.511
315.01592276.062324.65972274.627387.34412279.279460.53632279.433488.70522282.228
498.36692278.972508.02852276.919526.29782278.976537.81922281.607572.3834  2279.4
  627.112283.167646.01742280.492 657.7842280.961667.44572278.687703.07912284.297
744.44732281.509760.26672283.229860.41942307.516891.2922 2316.67 936.462 2333.01
#Mann= 5 ,-1 , 0
       0      .1       0  107.28     .12       0  243.43      .1       0
498.3669    .045       0526.2978      .1       0
#XS Ineff= 2 , 0
          489.71 2282.69  631.75         2282.69
Permanent Ineff=
       F       F
Bank Sta=498.3669,526.2978
XS Rating Curve= 0 ,0
Exp/Cntr(USF)=0,0
Exp/Cntr=0.3,0.1

Type RM Length L Ch R = 1 ,31872   ,218.4,219.6,219.3
XS GIS Cut Line= 4
2467185.93642002550461.3399988762467530.01504242550761.531041883
2467617.79020119550870.3722387622467747.69743618551061.722084889
#Sta/Elev= 30
       02321.87918.682172315.48132.781222313.95248.848342308.17472.546832295.667
86.006862286.405   98.67 2279.89117.9633 2271.28  151.672265.878154.76132265.626
209.22982269.446  279.112270.781343.08742272.402385.67842270.361 464.1582274.875
489.20212271.866530.31142271.774546.29252271.744556.00472274.669583.2725 2274.95
 606.7442277.895659.92582274.478698.60362274.581706.93682273.273717.94242269.215
732.44652270.108754.81852285.785776.18272298.858790.44792309.563827.72812333.404
#Mann= 6 ,-1 , 0
       0      .1       0   98.67      .1       0  151.67     .12       0
  279.11      .1       0530.3114    .045       0546.2925      .1       0
#XS Ineff= 2 , 0
          467.76 2274.91   611.8         2277.86
Permanent Ineff=
       F       F
Bank Sta=530.3114,546.2925
XS Rating Curve= 0 ,0
Exp/Cntr(USF)=0,0
Exp/Cntr=0.3,0.1