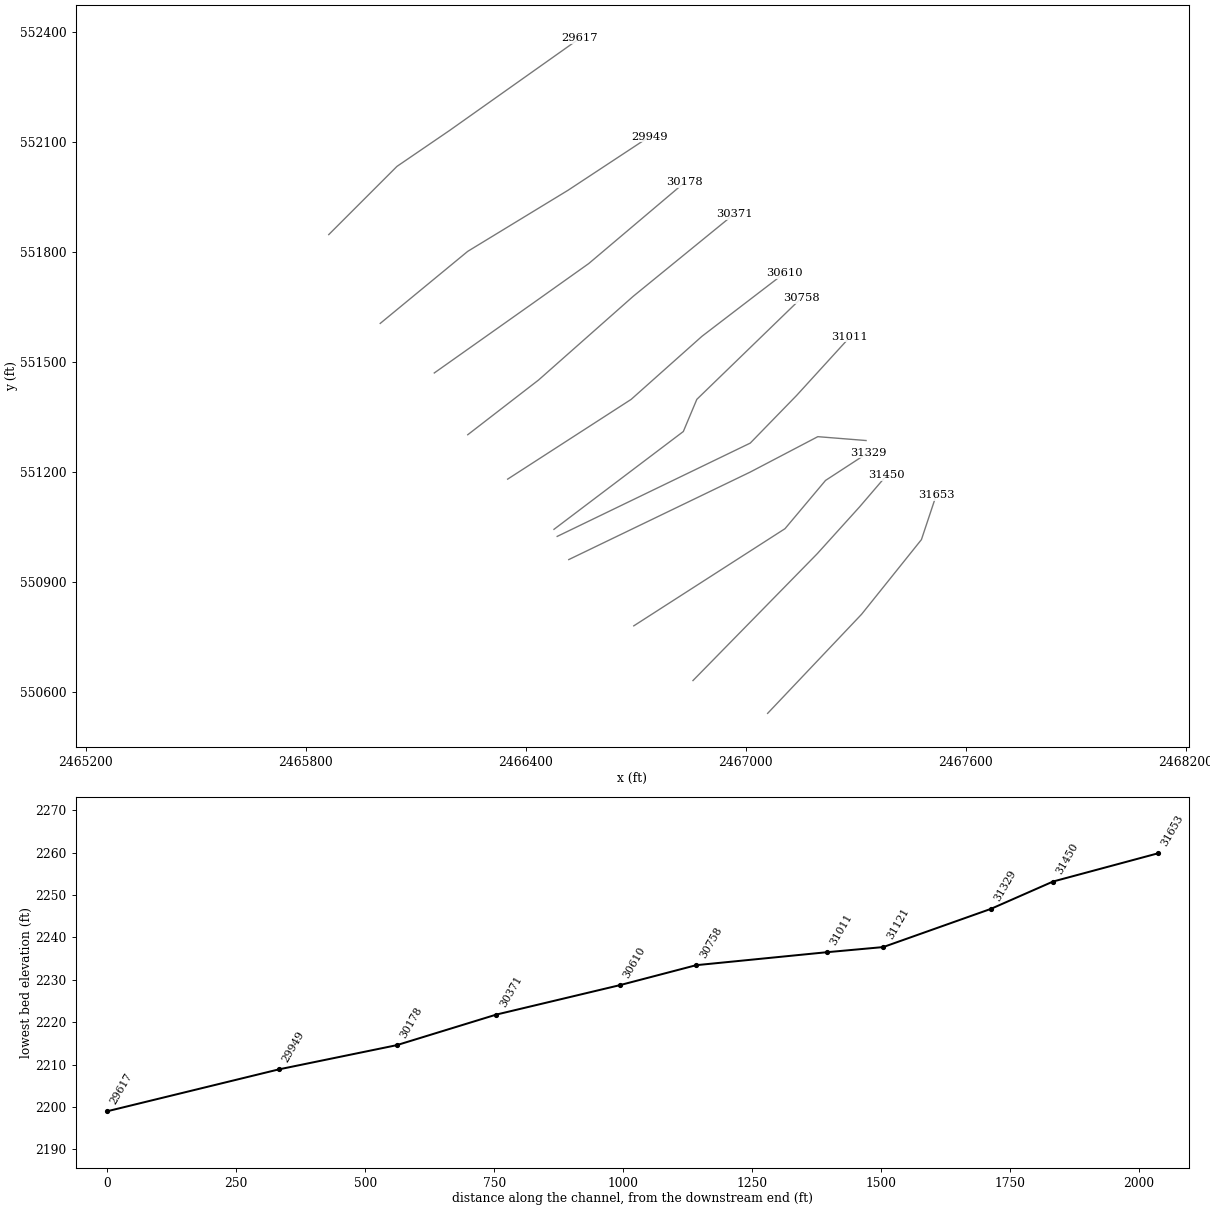
HEC-RAS study LITTLEFK.prj: LITTLEFK

--- LITTLEFK.g01 (geometry) --- (continued)

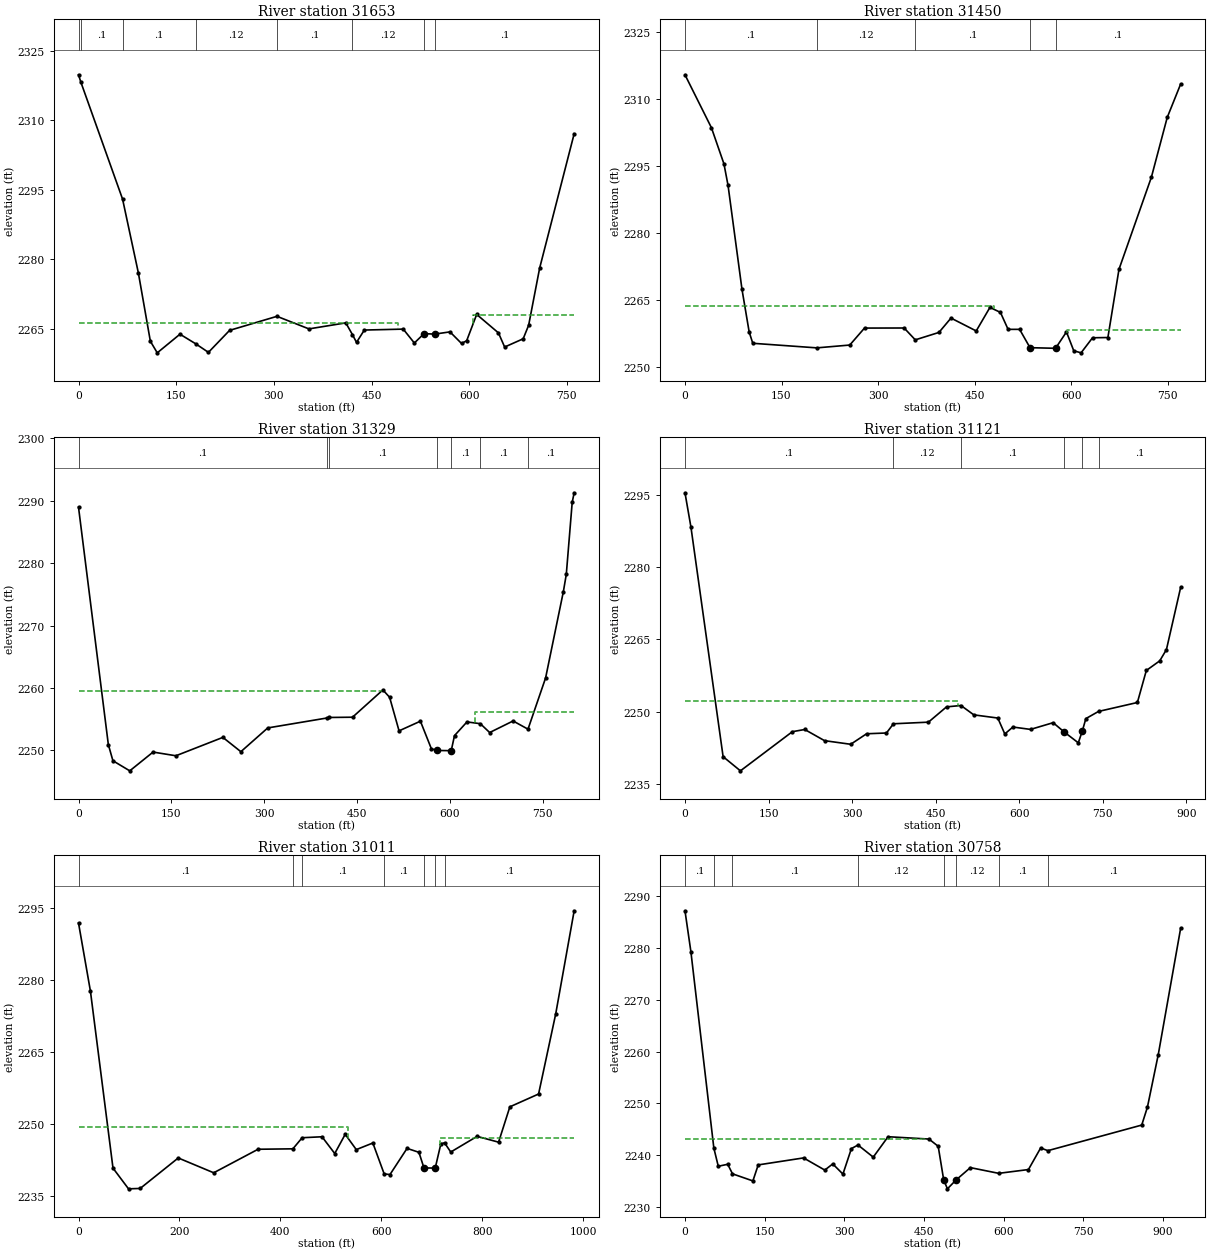
Type RM Length L Ch R = 1 ,31653   ,206.3,202.8,199.3
XS GIS Cut Line= 4
2467059.54019139550542.0931449482467315.84365501550812.440633971
2467479.10545033551016.0790023272467519.48202337551137.208721435
#Sta/Elev= 30
       02319.781    3.67 2318.17   67.672292.96891.866712277.097110.34972262.322
120.93622259.823155.81962263.842  180.082261.765 199.5272259.924232.01532264.668
  304.762267.696353.85972264.987410.48392266.284  420.712263.748426.93942262.076
438.93892264.737498.69452264.938515.76752261.945530.64282263.963 547.0682263.862
570.49012264.344588.19542261.849596.12412262.435611.50462268.108644.93142264.125
654.44642261.077682.90692262.851691.31152265.777708.17692278.085761.21662307.067
#Mann= 8 ,-1 , 0
       0      .1       0    3.67      .1       0   67.67      .1       0
  180.08     .12       0  304.76      .1       0  420.71     .12       0
530.6428    .045       0 547.068      .1       0
#XS Ineff= 2 , 0
          490.53 2266.27  605.76         2267.95
Permanent Ineff=
       F       F
Bank Sta=530.6428,547.068
XS Rating Curve= 0 ,0
Exp/Cntr(USF)=0,0
Exp/Cntr=0.3,0.1

Type RM Length L Ch R = 1 ,31450   ,121,120.7,119.2
XS GIS Cut Line= 4
2466855.90182304550631.623806897 2467194.7139359550977.457932466
2467310.57714548551105.6096642762467384.30827885551191.629319875
#Sta/Elev= 30
       02315.40941.092342303.56560.570852295.46966.936332290.64588.569442267.413
99.768882257.846105.36862255.329  204.852254.305256.06412254.936278.95992258.733
340.5568 2258.75  357.862256.097394.6643 2257.76413.3531 2260.97452.55122258.089
473.8644 2263.35490.15422262.248 502.0832258.446519.97612258.447536.15622254.346
575.80442254.208592.7964 2257.87604.12452253.657615.49432253.192633.29962256.563
657.16472256.617674.39912271.881724.77472292.495749.36022305.858770.20132313.324
#Mann= 5 ,-1 , 0
       0      .1       0  204.85     .12       0  357.86      .1       0
536.1562    .045       0575.8044      .1       0
#XS Ineff= 2 , 0
          479.56 2263.69  593.69         2258.39
Permanent Ineff=
       F       F
Bank Sta=536.1562,575.8044
XS Rating Curve= 0 ,0
Exp/Cntr(USF)=0,0
Exp/Cntr=0.3,0.1

Type RM Length L Ch R = 1 ,31329   ,195.9,208.6,200.6
XS GIS Cut Line= 4
2466694.39553089550780.8415768132467106.93877713 551045.92255631
2467217.53547718551177.5852944712467333.39868677551253.071931016
#Sta/Elev= 30
       02288.95948.187982250.93355.587492248.34982.785422246.734120.4156 2249.74
157.31652249.149233.17562252.092262.25222249.802305.67162253.608  400.872255.191
  405.152255.283 442.5912255.325491.63172259.695502.50382258.518517.75142253.139
552.25572254.687569.9908 2250.26 578.9292249.996602.00752249.964607.31992252.377
627.45422254.571  649.012254.286664.13442252.869701.95282254.722  726.042253.409
754.46732261.617783.11162275.419787.88572278.201797.43382289.755 800.6012291.274
#Mann= 7 ,-1 , 0
       0      .1       0  400.87     .12       0  405.15      .1       0
 578.929    .045       0602.0075      .1       0  649.01      .1       0
  726.04      .1       0
#XS Ineff= 2 , 0
          489.71 2259.59   640.6         2256.16
Permanent Ineff=
       F       F
Bank Sta=578.929,602.0075
XS Rating Curve= 0 ,0
Exp/Cntr(USF)=0,0
Exp/Cntr=0.3,0.1

Type RM Length L Ch R = 1 ,31121   ,108.4,109.9,113.6
XS GIS Cut Line= 4
2466517.08971017550961.6584038872467012.14160565551200.406835752
2467196.46943908551296.9595104032467328.13217724 551286.42649135
#Sta/Elev= 30
       02295.39410.719522288.26568.450852240.67299.536962237.734192.79532245.855
214.99962246.307250.52662243.991297.50212243.242326.02142245.421361.68232245.581
  374.242247.492437.04322247.829469.53812250.999  495.422251.282518.50082249.343
561.58552248.681574.12772245.385588.67872246.818620.28742246.326660.92722247.718
680.80712245.786706.08252243.544713.40362246.031719.62922248.563  742.362250.052
 812.1492251.906828.20012258.545852.27682260.543864.31522262.884889.7834 2275.76
#Mann= 6 ,-1 , 0
       0      .1       0  374.24     .12       0  495.42      .1       0
680.8071    .045       0713.4036      .1       0  742.36      .1       0
#XS Ineff= 2 , 0
          489.71 2252.21
Permanent Ineff=
       F       F
Bank Sta=680.8071,713.4036
XS Rating Curve= 0 ,0
Exp/Cntr(USF)=0,0
Exp/Cntr=0.3,0.1

Type RM Length L Ch R = 1 ,31011   ,244.2,252.6,254.2
XS GIS Cut Line= 4
2466485.49065301551024.8565182042467012.14160565551279.404478648
2467138.53783429551409.3117136342467284.24459785551569.062502602
#Sta/Elev= 30
       02291.91823.606832277.72668.354582240.831 99.13312236.514122.26632236.597
197.70352242.949267.95652239.859355.88352244.763   424.92244.854   443.32247.165
482.65052247.366507.86352243.877528.60972247.876550.56462244.688583.38982246.066
  605.862239.617 617.3542239.494651.19562244.944674.71362244.127684.68122240.873
707.00492240.841718.16672245.882  725.482246.104737.80922244.185789.9849 2247.45
832.57892246.241854.95182253.607911.85852256.276945.83552272.975982.41112294.464
#Mann= 7 ,-1 , 0
       0      .1       0   424.9     .12       0   443.3      .1       0
  605.86      .1       0684.6812    .045       0707.0049      .1       0
  725.48      .1       0
#XS Ineff= 2 , 0
          534.98 2249.37  717.42         2247.18
Permanent Ineff=
       F       F
Bank Sta=684.6812,707.0049
XS Rating Curve= 0 ,0
Exp/Cntr(USF)=0,0
Exp/Cntr=0.3,0.1

Type RM Length L Ch R = 1 ,30758   ,155.4,148,141.8
XS GIS Cut Line= 4
2466476.71313713551044.167053134 2466829.5692754551311.003535807
2466866.43484209551398.7786945812467150.82635652551674.392693131
#Sta/Elev= 30
       02287.22711.147482279.316    54.42241.32762.72706 2237.83 80.49482238.214
   89.512236.366127.92162234.995137.95152238.093223.35972239.444263.32572237.093
278.37052238.283297.51642236.318313.47532241.248  325.912241.937354.62732239.595
382.51882243.541 459.622 2243.09476.97592241.688  487.29 2235.21494.32982233.465
510.41822235.163 537.5932237.566   590.92236.463646.95922237.195669.94982241.364
  683.612240.849860.37192245.795871.1171 2249.28891.48852259.418933.62532283.836
#Mann= 8 ,-1 , 0
       0      .1       0    54.4      .1       0   89.51      .1       0
  325.91     .12       0  487.29    .045       0510.4182     .12       0
   590.9      .1       0  683.61      .1       0
#XS Ineff= 2 , 0
          454.05 2243.17
Permanent Ineff=
       F       F
Bank Sta=487.29,510.4182
XS Rating Curve= 0 ,0
Exp/Cntr(USF)=0,0
Exp/Cntr=0.3,0.1

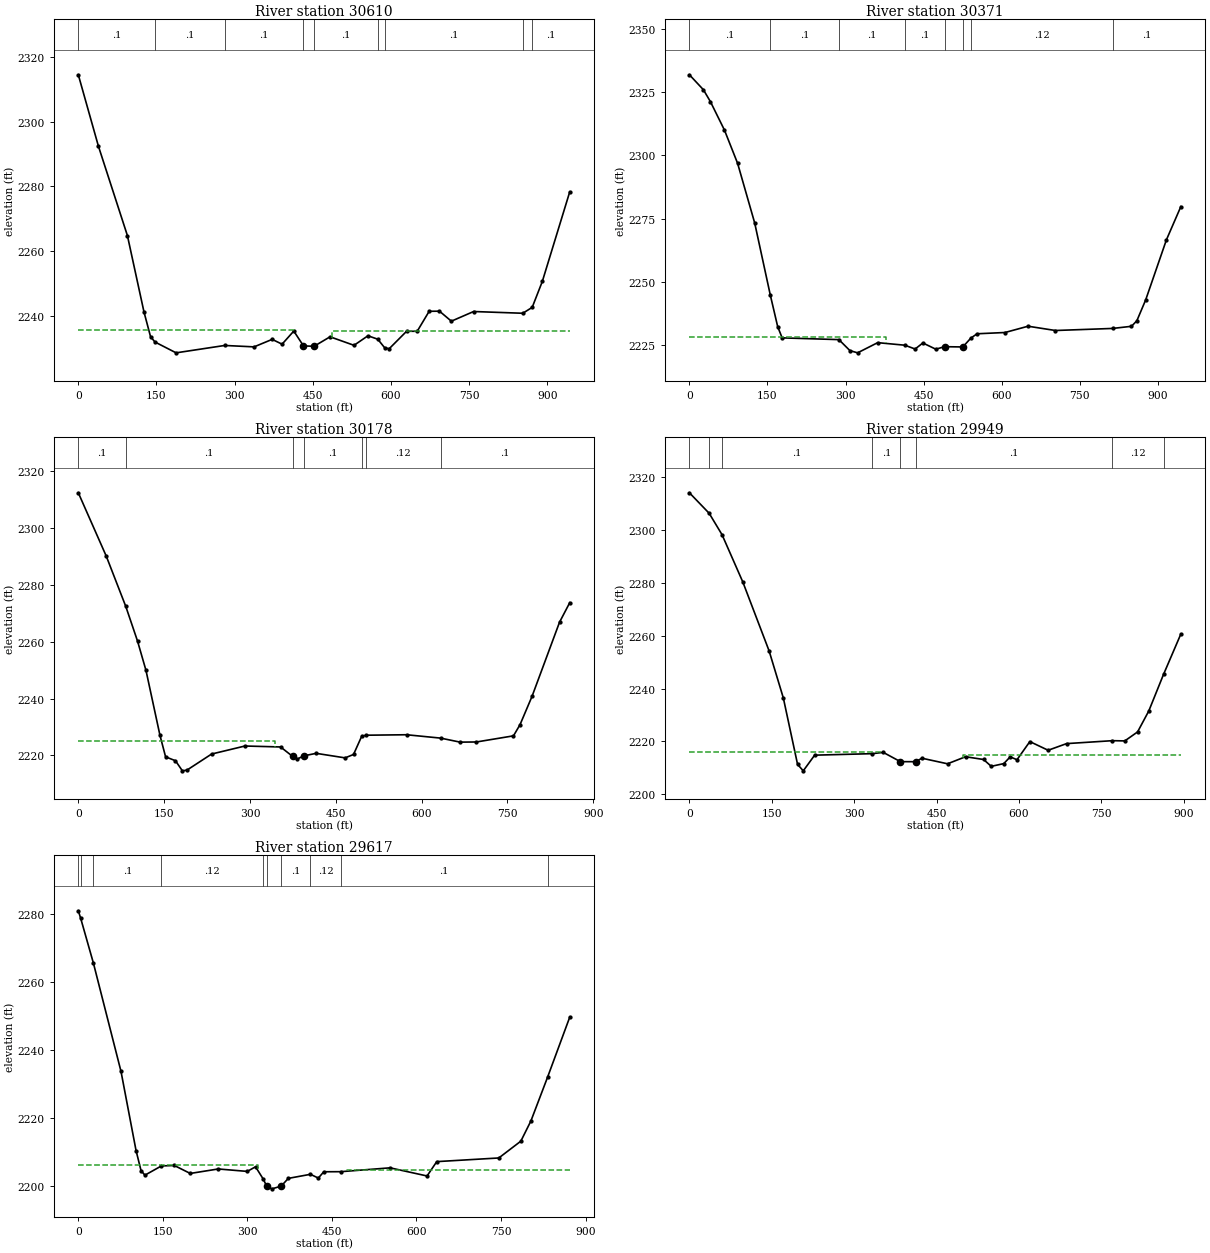
Type RM Length L Ch R = 1 ,30610   ,228,239.4,237
XS GIS Cut Line= 4
 2466350.3169085551181.0963008222466687.37351819551398.778694581
2466880.47886749551570.8180057772467105.18327395551742.857316974
#Sta/Elev= 30
       02314.39838.603112292.39794.189222264.879126.01412241.352138.59842233.744
   147.12232.091 187.6312228.756  280.882231.029337.21582230.594371.95412232.906
390.96752231.424413.4341 2235.46432.03782230.893   452.42230.777483.03412233.697
  528.972231.074555.7559 2234.01  574.552232.954  587.772230.322596.35942230.005
629.90832235.409650.18882235.393673.14432241.552692.94532241.589715.74462238.505
 758.4362241.482   852.82240.946  870.862242.765890.2816 2250.76942.86572278.341
#Mann= 9 ,-1 , 0
       0      .1       0   147.1      .1       0  280.88      .1       0
432.0378    .045       0   452.4      .1       0  574.55     .12       0
  587.77      .1       0   852.8     .12       0  870.86      .1       0
#XS Ineff= 2 , 0
          412.89 2235.87  486.97          2235.5
Permanent Ineff=
       F       F
Bank Sta=432.0378,452.4
XS Rating Curve= 0 ,0
Exp/Cntr(USF)=0,0
Exp/Cntr=0.3,0.1

Type RM Length L Ch R = 1 ,30371   ,182.2,193.3,188.2
XS GIS Cut Line= 4
2466241.47571162551302.2260199292466434.58106092551451.443789845
2466692.64002772551679.6592026572466968.25402627551904.363609118
#Sta/Elev= 30
       02331.97426.879482326.04840.338472321.33867.320032310.06792.595372296.891
125.38262273.298   155.42244.736169.62192232.172178.17672227.745  287.192227.053
308.33652222.708323.10962221.817361.73442225.851  413.922224.838433.6258 2223.33
448.49982225.726473.29832223.267490.30082224.251  525.26 2224.15  540.65 2227.64
552.64322229.369606.30972229.872 650.621 2232.36703.20642230.666  813.022231.485
849.29692232.329859.61882234.519876.63132242.814 916.4892266.624944.14042279.751
#Mann= 8 ,-1 , 0
       0      .1       0   155.4      .1       0  287.19      .1       0
  413.92      .1       0490.3008    .045       0  525.26      .1       0
  540.65     .12       0  813.02      .1       0
#XS Ineff= 2 , 0
          377.23 2228.19
Permanent Ineff=
       F       F
Bank Sta=490.3008,525.26
XS Rating Curve= 0 ,0
Exp/Cntr(USF)=0,0
Exp/Cntr=0.3,0.1

Type RM Length L Ch R = 1 ,30178   ,231,228.7,227.8
XS GIS Cut Line= 4
2466150.18954649551470.7543247752466425.80354504551665.615177253
2466571.51030861551769.1898646062466833.08028175551990.383264716
#Sta/Elev= 30
       02312.37648.738552290.158   83.022272.396 103.5542260.197118.25022249.943
 142.7442227.062152.54152219.528 169.8142218.147 181.9342214.597189.90262214.853
232.94942220.504291.24862223.329353.55062222.992  374.38  2219.7382.86462218.758
393.63312219.847415.6861 2220.75466.29422219.156481.01712220.356  495.22 2226.73
  503.112227.125573.73942227.289  633.252226.104 667.2232224.693695.78642224.745
760.53732226.905771.99262230.834792.94652240.776841.06852266.882858.86652273.725
#Mann= 7 ,-1 , 0
       0      .1       0   83.02      .1       0  374.38    .045       0
393.6331      .1       0  495.22      .1       0  503.11     .12       0
  633.25      .1       0
#XS Ineff= 2 , 0
          344.31 2225.24
Permanent Ineff=
       F       F
Bank Sta=374.38,393.6331
XS Rating Curve= 0 ,0
Exp/Cntr(USF)=0,0
Exp/Cntr=0.3,0.1

Type RM Length L Ch R = 1 ,29949   ,318.9,332.3,330.4
XS GIS Cut Line= 4
2466002.72727975551605.9280692872466241.47571162 551802.54442494
2466515.33420699551969.317226611 2466736.5276071552115.023990175
#Sta/Elev= 30
       0 2314.07   35.932306.323    59.42298.21897.312392280.293145.11382254.258
171.02292236.452 196.9322211.336207.29562208.884228.03392214.813  333.182215.383
352.92372215.868  384.16 2212.36412.3398 2212.34423.17372213.668 470.0072211.549
502.79032214.219535.57372213.175549.62372210.583572.4314 2211.62584.07442214.178
 596.4572213.085619.8737 2219.95 653.1742216.668 686.7032219.182  770.222220.292
792.76072220.205816.02942223.606836.38892231.509  863.25 2245.35894.80182260.635
#Mann= 8 ,-1 , 0
       0      .1       0   35.93      .1       0    59.4      .1       0
  333.18      .1       0  384.16    .045       0412.3398      .1       0
  770.22     .12       0  863.25      .1       0
#XS Ineff= 2 , 0
          352.54 2215.94  497.94         2215.06
Permanent Ineff=
       F       F
Bank Sta=384.16,412.3398
XS Rating Curve= 0 ,0
Exp/Cntr(USF)=0,0
Exp/Cntr=0.3,0.1

Type RM Length L Ch R = 1 ,29617   ,182.6,181.5,178
XS GIS Cut Line= 4
2465862.28702572551848.1875075032466048.37036232552034.270844103
2466192.32162271 552132.579021932466546.93326415552383.615976023
#Sta/Elev= 30
       02280.957    4.262278.721   26.712265.59175.774542233.616102.47112210.298
111.30342204.392118.20092203.048  147.532205.776170.3534  2205.9198.63762203.556
248.30862204.875299.85472204.156 314.4752205.525  328.312201.847  334.192199.816
343.5377 2199.02  359.992199.817372.60042202.102  411.862203.301 425.8822202.196
435.56952204.048  465.782204.076553.1677 2205.21 618.7842202.809636.0009 2207.04
746.08722208.117785.21442213.071803.11162219.041  832.572231.896871.95422249.608
#Mann= 10 ,-1 , 0
       0      .1       0    4.26      .1       0   26.71      .1       0
  147.53     .12       0  328.31      .1       0  334.19    .045       0
  359.99      .1       0  411.86     .12       0  465.78      .1       0
  832.57     .12       0
#XS Ineff= 2 , 0
          318.24 2206.13  475.99         2204.58
Permanent Ineff=
       F       F
Bank Sta=334.19,359.99
XS Rating Curve= 0 ,0
Exp/Cntr(USF)=0,0
Exp/Cntr=0.3,0.1