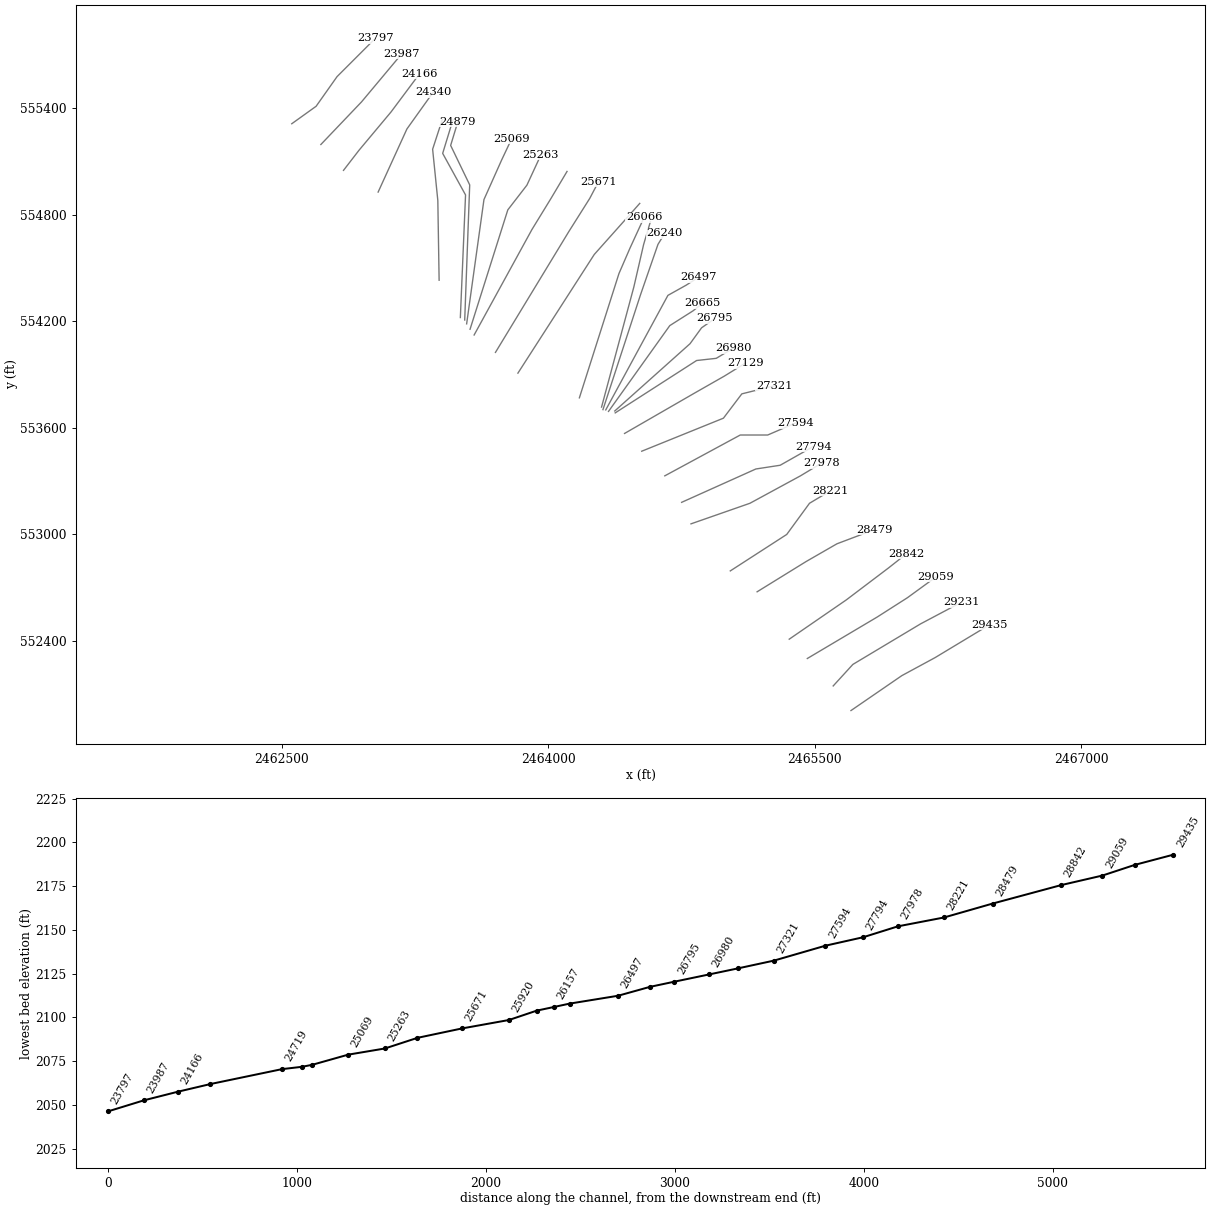
HEC-RAS study LITTLEFK.prj: LITTLEFK

--- LITTLEFK.g01 (geometry) --- (continued)

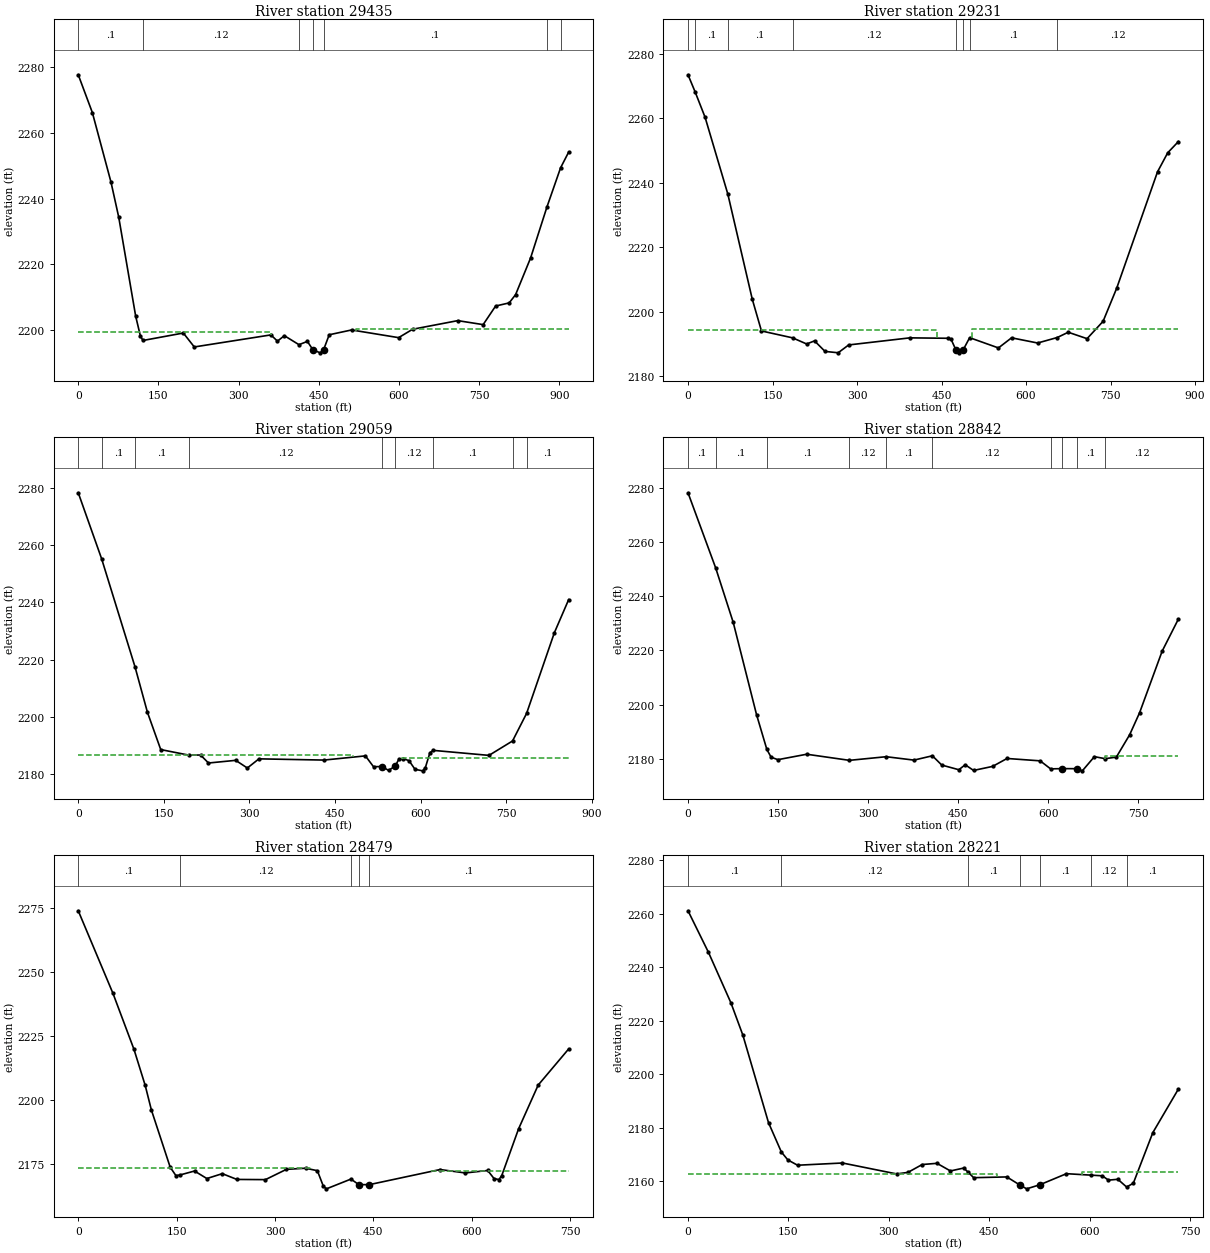
Type RM Length L Ch R = 1 ,29435   ,203.3,204.4,205
XS GIS Cut Line= 4
2465704.29173992552007.9382964712465990.43875753552204.554652125
 2466178.2775973552306.3738363022466483.73514983552490.701669727
#Sta/Elev= 30
       02277.74926.403322266.22761.215662245.07875.775422234.335107.44732204.215
116.07732198.283  120.982196.794196.62362199.069217.11022194.823360.48212198.495
372.73932196.591385.66322198.258  412.982195.519 428.7992196.515  439.182193.933
452.81282193.031  458.962193.932469.6002 2198.54511.41342200.001599.4404 2197.66
625.66312200.214710.15882202.843757.61052201.629780.96992207.291806.30892208.246
818.34492210.765846.37622221.923  877.08 2237.51   902.52249.395917.61072254.186
#Mann= 7 ,-1 , 0
       0      .1       0  120.98     .12       0  412.98      .1       0
  439.18    .045       0  458.96      .1       0  877.08     .12       0
   902.5      .1       0
#XS Ineff= 2 , 0
          360.77 2199.37  519.89          2200.3
Permanent Ineff=
       F       F
Bank Sta=439.18,458.96
XS Rating Curve= 0 ,0
Exp/Cntr(USF)=0,0
Exp/Cntr=0.3,0.1

Type RM Length L Ch R = 1 ,29231   ,170,171.3,171.1
XS GIS Cut Line= 4
2465604.22805892552146.6230473342465714.82475898552267.752766442
2466095.76894805552495.9681792542466327.49536722552618.853401537
#Sta/Elev= 30
       02273.552   12.86 2268.1430.284662260.368   70.622236.536 114.1092203.819
130.3585 2193.99   185.72191.844210.56022189.944224.54882190.906243.20032187.637
266.51462187.214285.16612189.646393.69982191.846460.76712191.718467.01792191.357
 475.3472188.156481.00642187.193  488.582188.179  499.872191.904550.94952188.719
574.26382191.858620.52142190.245  655.412191.954674.85312193.588 708.2522191.594
736.72412196.989760.87832207.273833.32062243.411851.43112249.332 870.3912252.811
#Mann= 8 ,-1 , 0
       0      .1       0   12.86      .1       0   70.62      .1       0
   185.7     .12       0 475.347    .045       0  488.58     .12       0
  499.87      .1       0  655.41     .12       0
#XS Ineff= 2 , 0
           441.7 2194.21  503.43         2194.58
Permanent Ineff=
       F       F
Bank Sta=475.347,488.58
XS Rating Curve= 0 ,0
Exp/Cntr(USF)=0,0
Exp/Cntr=0.3,0.1

Type RM Length L Ch R = 1 ,29059   ,217.6,217.5,220.8
XS GIS Cut Line= 4
2465458.52129536552301.1073267762465851.75400666552534.589249114
2466022.03781468552643.4304459942466183.54410683552761.049158751
#Sta/Elev= 30
       02278.344   40.972255.251   99.442217.471121.21092201.573 144.5212188.528
  194.212186.566214.24982186.628228.20572183.831275.83852184.762296.2706 2182.08
316.59272185.286430.53862184.857503.15072186.324517.30232182.535532.0837  2182.6
543.69672181.251555.28132182.755561.86552185.199569.29272185.379579.55652184.643
 590.035 2181.62 603.2932181.092608.04032182.134616.10032187.395  621.982188.248
719.65682186.499  760.892191.536  785.482201.156834.1948  2229.4 859.2172240.969
#Mann= 9 ,-1 , 0
       0      .1       0   40.97      .1       0   99.44      .1       0
  194.21     .12       0532.0837    .045       0555.2813     .12       0
  621.98      .1       0  760.89     .12       0  785.48      .1       0
#XS Ineff= 2 , 0
          481.48 2186.46  566.53         2185.72
Permanent Ineff=
       F       F
Bank Sta=532.0837,555.2813
XS Rating Curve= 0 ,0
Exp/Cntr(USF)=0,0
Exp/Cntr=0.3,0.1

Type RM Length L Ch R = 1 ,28842   ,366.3,363.3,367
XS GIS Cut Line= 4
2465356.70211118552409.9485236562465677.95919229552631.141923766
2465916.70762416 552811.958750842466016.77130516552890.956393736
#Sta/Elev= 30
       0 2278.07   46.12 2250.3875.327022230.338114.17862196.361  131.372183.528
138.46082180.674149.78332179.771197.7245 2181.77  268.882179.522  330.142180.859
376.42662179.608  407.152181.198422.75262177.782451.24012176.063461.80512177.892
475.75512175.805507.48932177.291531.52332180.211 586.7182179.336  604.132176.379
   623.82176.474647.39712176.449656.96582175.656677.03662180.879  695.032180.135
713.63182180.713735.7912 2188.94752.36382197.061789.90192219.719817.0226 2231.57
#Mann= 10 ,-1 , 0
       0      .1       0   46.12      .1       0  131.37      .1       0
  268.88     .12       0  330.14      .1       0  407.15     .12       0
  604.13      .1       0   623.8    .045       0647.3971      .1       0
  695.03     .12       0
#XS Ineff= 2 , 0
          530.86 2179.93  695.47         2181.03
Permanent Ineff=
       F       F
Bank Sta=623.8,647.3971
XS Rating Curve= 0 ,0
Exp/Cntr(USF)=0,0
Exp/Cntr=0.3,0.1

Type RM Length L Ch R = 1 ,28479   ,247.5,257.4,264
XS GIS Cut Line= 4
 2465175.8852841552676.7850063282465451.49928265552847.068814349
2465625.29409703552947.1324953512465834.19897491553026.130138248
#Sta/Elev= 30
       02274.08953.014432241.666 84.98342219.764102.10072205.637111.50442196.023
140.20252173.572148.92132170.268  155.432170.538177.33042172.066196.13792169.118
219.64722171.031241.92192168.765285.47332168.691317.48492172.726346.7253 2173.16
 364.6452172.197373.8763 2166.04378.4919 2165.08  415.872168.906 427.8342166.729
443.86722166.722551.72742172.648590.2153 2171.31624.42692172.271634.06162169.109
641.53272168.719645.80912170.254671.46782188.581701.40292205.761  747.862219.919
#Mann= 5 ,-1 , 0
       0      .1       0  155.43     .12       0  415.87      .1       0
 427.834    .045       0443.8672      .1       0
#XS Ineff= 2 , 0
          354.46 2173.06  537.72         2171.96
Permanent Ineff=
       F       F
Bank Sta=427.834,443.8672
XS Rating Curve= 0 ,0
Exp/Cntr(USF)=0,0
Exp/Cntr=0.3,0.1

Type RM Length L Ch R = 1 ,28221   ,252.1,243.7,240.3
XS GIS Cut Line= 4
2465024.91201101552794.4037190852465342.65808577552999.797590616
2465470.80981758553175.3479081632465588.42853034553245.568035183
#Sta/Elev= 30
       02261.16430.607242245.58664.100752226.73281.948622214.638120.28782181.876
  139.482170.899 149.2172167.926163.68162165.954230.80332166.787311.77322162.699
328.57812163.272349.87662166.213371.97192166.665392.08532163.813411.89492164.896
  419.012163.236426.75222161.295476.27632161.575 496.086 2158.51505.99082157.118
525.80042158.661565.41972162.789  602.812162.231618.91782161.995 628.2352160.371
642.21092160.693  655.312157.799665.32962159.212694.50052178.168732.68562194.465
#Mann= 7 ,-1 , 0
       0      .1       0  139.48     .12       0  419.01      .1       0
 496.086    .045       0525.8004      .1       0  602.81     .12       0
  655.31      .1       0
#XS Ineff= 2 , 0
             462 2162.73   588.2         2163.25
Permanent Ineff=
       F       F
Bank Sta=496.086,525.8004
XS Rating Curve= 0 ,0
Exp/Cntr(USF)=0,0
Exp/Cntr=0.3,0.1

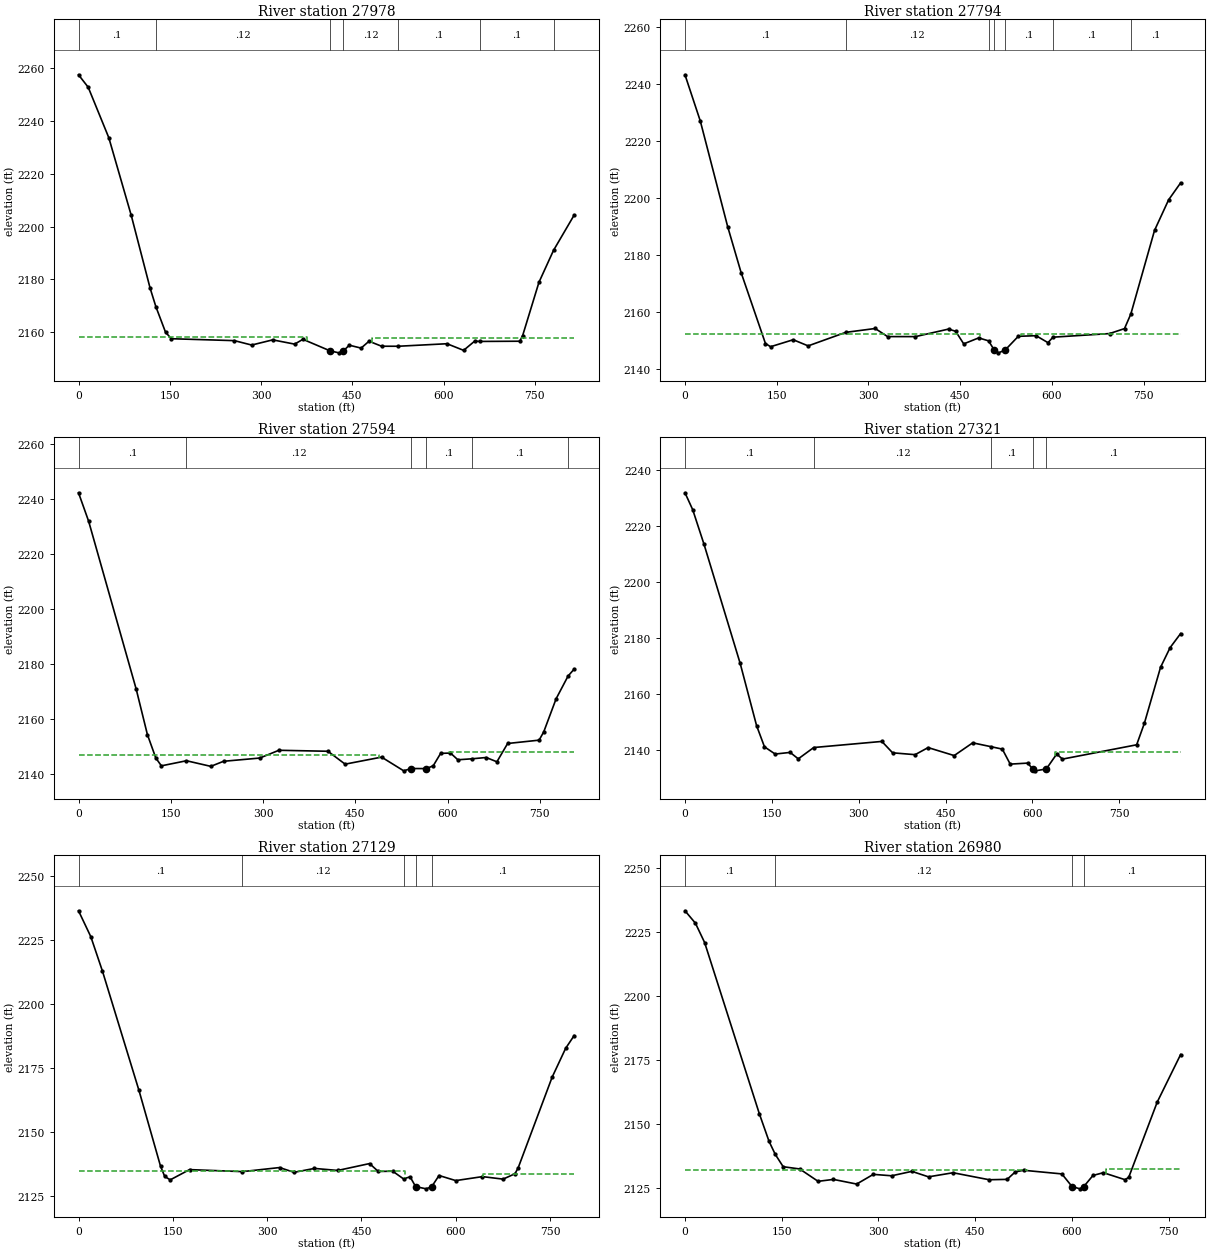
Type RM Length L Ch R = 1 ,27978   ,191.5,183.8,180.3
XS GIS Cut Line= 4
 2464803.7186109553059.4846985822465135.50871107553175.347908163
 2465419.9002255553329.8321876052465539.27444143  553401.8078178
#Sta/Elev= 30
       02257.59915.916282252.86749.811292233.69886.697142204.195117.60132176.658
  127.172169.554143.02262159.876152.64292157.421256.2719 2156.69284.53432155.019
319.07732156.988355.12142155.372368.77762157.199   413.52152.804427.95432152.063
  435.312152.806444.92972154.964464.37082153.861477.37682156.471498.02492154.571
  525.632154.565605.48462155.521632.79692153.008651.00522156.511   659.82156.392
725.11022156.474729.78112158.585756.59922178.832  780.522190.941814.47412204.353
#Mann= 7 ,-1 , 0
       0      .1       0  127.17     .12       0   413.5    .045       0
  435.31     .12       0  525.63      .1       0   659.8      .1       0
  780.52      .1       0
#XS Ineff= 2 , 0
          375.86 2158.16  482.85         2157.71
Permanent Ineff=
       F       F
Bank Sta=413.5,435.31
XS Rating Curve= 0 ,0
Exp/Cntr(USF)=0,0
Exp/Cntr=0.3,0.1

Type RM Length L Ch R = 1 ,27794   ,203.8,199.9,197
XS GIS Cut Line= 4
2464751.05351564 553180.61441769 2465168.8632714553368.453257466
2465305.79251909553389.5192955722465491.87585569  553494.8494861
#Sta/Elev= 30
       02243.31625.061722227.09969.832232190.064 91.76052173.983131.58352149.104
140.00272147.981176.96552150.431201.40182148.274  262.852153.015311.0432 2154.37
331.26422151.531376.82792151.524431.1046 2154.17442.61272153.381455.76972148.981
480.23142151.072  496.412150.042  505.732146.802512.60782145.836  523.462146.801
544.98432151.627574.11822151.847593.54912149.404  601.732151.325694.25012152.587
718.67332154.331  729.032159.447767.7916 2188.77790.77342199.461810.45812205.427
#Mann= 7 ,-1 , 0
       0      .1       0  262.85     .12       0  496.41      .1       0
  505.73    .045       0  523.46      .1       0  601.73      .1       0
  729.03      .1       0
#XS Ineff= 2 , 0
          482.85  2152.4  550.07          2152.4
Permanent Ineff=
       F       F
Bank Sta=505.73,523.46
XS Rating Curve= 0 ,0
Exp/Cntr(USF)=0,0
Exp/Cntr=0.3,0.1

Type RM Length L Ch R = 1 ,27594   ,252.1,272.5,284.7
XS GIS Cut Line= 4
2464656.25634416553329.8321876062465081.08811263553559.803103593
2465235.57239207553559.8031035932465390.05667151553626.512224261
#Sta/Elev= 30
       02242.12116.475312231.76793.799112170.692111.99292154.184125.63832145.672
134.7352 2142.81  175.53 2144.66215.0899 2142.62235.7469 2144.46294.76722145.645
325.77052148.469405.54372148.108433.4647 2143.42492.73942145.981528.7394 2140.99
540.73942141.839  565.472141.797576.73942142.842588.73942147.339604.73942147.464
616.73942145.013  639.032145.358662.8076 2145.84680.23552144.279697.66362150.937
748.83382152.151756.34452155.155776.52422167.221  795.942175.474805.83882177.995
#Mann= 6 ,-1 , 0
       0      .1       0  175.53     .12       0540.7394    .045       0
  565.47      .1       0  639.03      .1       0  795.94      .1       0
#XS Ineff= 2 , 0
          488.34 2146.86  602.19         2147.75
Permanent Ineff=
       F       F
Bank Sta=540.7394,565.47
XS Rating Curve= 0 ,0
Exp/Cntr(USF)=0,0
Exp/Cntr=0.3,0.1

Type RM Length L Ch R = 1 ,27321   ,199.9,192.5,186.8
XS GIS Cut Line= 4
2464526.34910918553468.5169384682464986.29094115553654.600275069
2465089.86562851553791.5295227562465272.43795876553837.172605318
#Sta/Elev= 30
       02231.82113.372022225.76532.848012213.44495.356442170.834 123.648 2148.63
137.29842141.036 155.7662138.464181.65582139.047195.66782136.749  222.352140.793
340.05512142.973358.56962138.905397.4043 2138.24419.92892140.771464.93772137.917
496.91152142.471  529.012141.073548.08942140.225561.72362134.862591.81622135.229
  600.552133.141605.19932132.463  624.072133.141641.97052138.462652.00132136.658
780.07872141.769793.38932149.435821.30982169.437837.80222176.469856.03962181.521
#Mann= 5 ,-1 , 0
       0      .1       0  222.35     .12       0  529.01      .1       0
  600.55    .045       0  624.07      .1       0
#XS Ineff= 2 , 0
          519.89 2141.25  639.23         2139.04
Permanent Ineff=
       F       F
Bank Sta=600.55,624.07
XS Rating Curve= 0 ,0
Exp/Cntr(USF)=0,0
Exp/Cntr=0.3,0.1

Type RM Length L Ch R = 1 ,27129   ,157.1,149.1,143.1
XS GIS Cut Line= 4
2464429.79643453 553568.580619472464828.29565536553798.551535458
2464991.55745068553891.5932037582465110.93166661553965.324337128
#Sta/Elev= 30
       02236.34119.568382226.23938.041532212.84896.093132166.381130.40732136.835
137.09012132.812145.87522131.475176.59012135.471  260.812134.684 319.757 2136.27
342.84842134.408375.17652135.931412.35552135.142462.91512137.824 476.7272134.753
499.74682134.836  516.882131.858527.37052132.659  536.162128.845553.05292127.975
  561.792128.844573.41022133.173599.97552131.187642.46952132.738675.26252131.758
694.06842133.842699.22252136.132753.23862171.468774.78792182.745788.31712187.712
#Mann= 5 ,-1 , 0
       0      .1       0  260.81     .12       0  516.88      .1       0
  536.16    .045       0  561.79      .1       0
#XS Ineff= 2 , 0
          519.07 2134.83  643.07         2133.95
Permanent Ineff=
       F       F
Bank Sta=536.16,561.79
XS Rating Curve= 0 ,0
Exp/Cntr(USF)=0,0
Exp/Cntr=0.3,0.1

Type RM Length L Ch R = 1 ,26980   ,171.7,185.1,190.2
XS GIS Cut Line= 4
2464377.13133926553684.4438290522464835.31766806553979.368362532
2464945.91436812 553991.656884762465042.46704277554049.588489551
#Sta/Elev= 30
       02233.23716.19013 2228.3930.461162220.837115.37652153.908130.35842143.175
  139.97 2138.09152.32822133.234177.92852132.363206.47052127.529230.25562128.278
266.30352126.461292.0967 2130.25320.63882129.695351.86782131.424377.72292129.281
 415.7792130.886471.7863 2128.15499.67492128.295512.3041 2131.21525.19022131.849
584.56932130.424  600.292125.498612.74162124.595  618.582125.499632.8646 2129.83
648.96312130.906 682.4632128.172688.29392129.113732.43372158.471768.77532177.076
#Mann= 4 ,-1 , 0
       0      .1       0  139.97     .12       0  600.29    .045       0
  618.58      .1       0
#XS Ineff= 2 , 0
          531.14 2131.96  652.95         2132.18
Permanent Ineff=
       F       F
Bank Sta=600.29,618.58
XS Rating Curve= 0 ,0
Exp/Cntr(USF)=0,0
Exp/Cntr=0.3,0.1

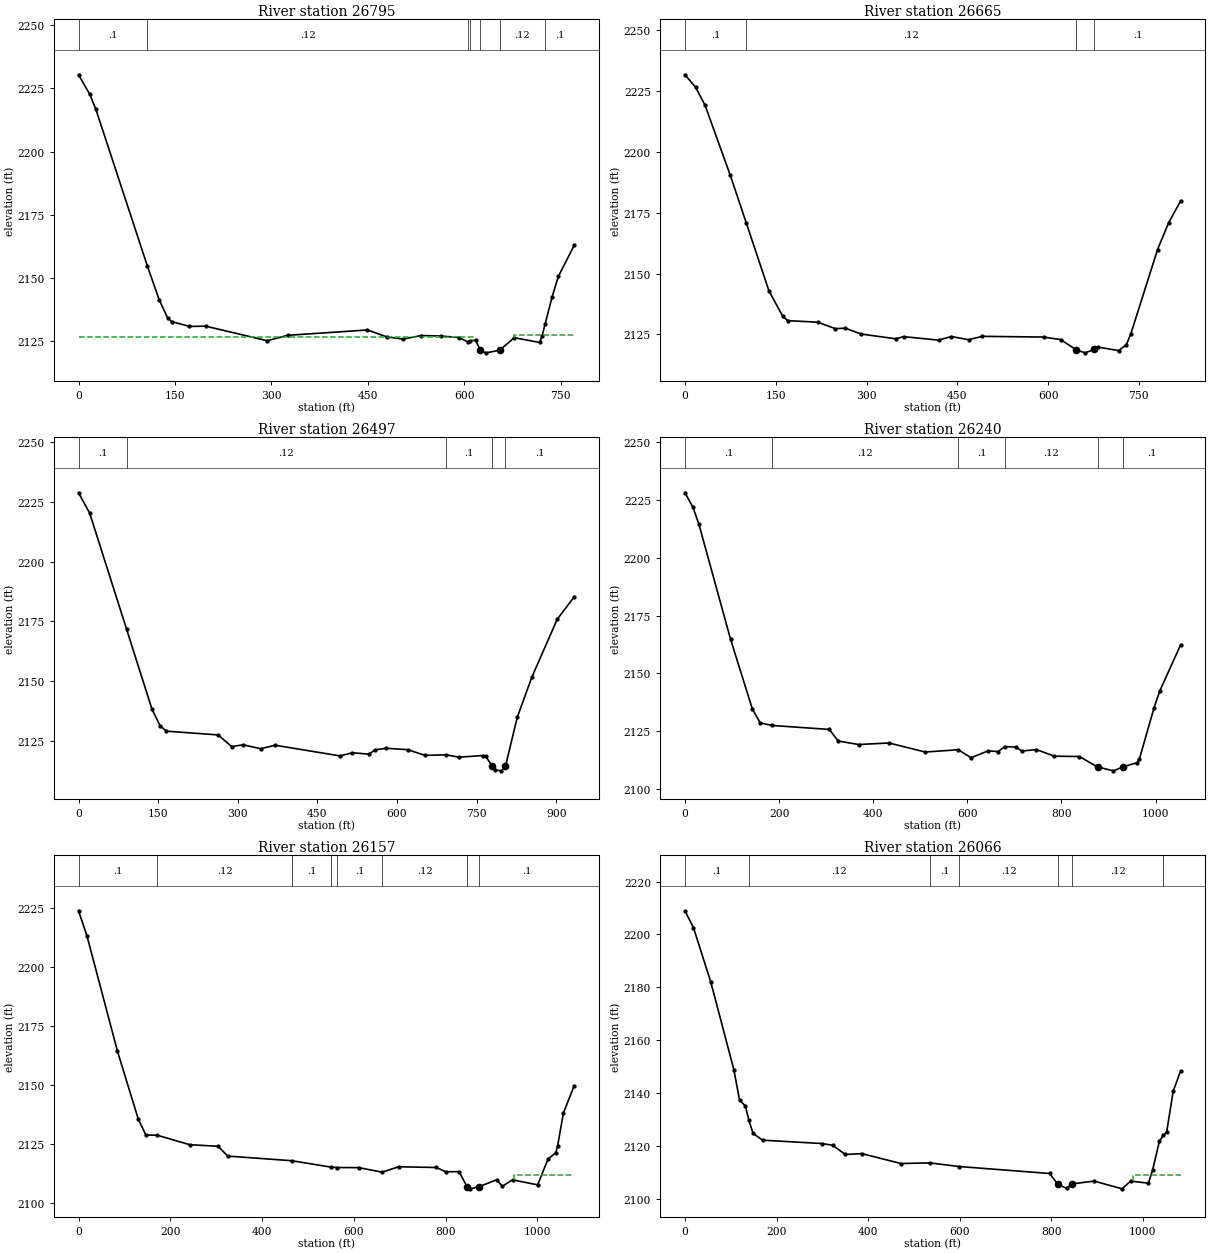
Type RM Length L Ch R = 1 ,26795   ,135.7,129.3,120.9
XS GIS Cut Line= 4
2464374.67363482553695.1523984222464798.45210138554074.165534008
2464863.40571887554163.6961959572464938.89235542554216.361291221
#Sta/Elev= 30
       02230.37217.608382222.605 26.92782216.763  106.992154.869125.6125 2141.35
138.67362134.201144.98862132.758172.66742130.875198.16282130.954293.61882125.212
325.63982127.353449.62482129.464479.62592126.734504.53742125.873533.62792127.257
563.56792127.067592.18232126.469  605.93 2124.73  609.552125.228617.95832125.355
  625.262121.419633.6807 2120.42  655.092121.419678.02682126.404717.36462124.521
721.19292126.988  725.972131.809736.8738 2142.56746.62842150.654771.19452162.905
#Mann= 7 ,-1 , 0
       0      .1       0  106.99     .12       0  605.93      .1       0
  609.55     .12       0  625.26    .045       0  655.09     .12       0
  725.97      .1       0
#XS Ineff= 2 , 0
          613.44 2126.86  678.19         2127.31
Permanent Ineff=
       F       F
Bank Sta=625.26,655.09
XS Rating Curve= 0 ,0
Exp/Cntr(USF)=0,0
Exp/Cntr=0.3,0.1

Type RM Length L Ch R = 1 ,26665   ,167.5,168.5,163.4
XS GIS Cut Line= 4
2464339.38802099553692.6946939772464684.34439497554175.984718185
2464814.25162996554258.4933674332464870.42773157 554302.38094682
#Sta/Elev= 30
       0  2231.617.441462226.52633.319112218.99774.630152190.487  101.362170.738
138.75862142.876161.69942132.385169.78812130.673219.21882130.044248.41862127.384
264.93332127.581290.74172125.193348.09382123.228  361.452124.103418.88882122.674
440.08062124.156468.5333 2122.85491.47422124.227592.42722123.938620.79982122.886
646.88172118.623661.37162117.458675.86162118.842681.90992119.829716.43342118.379
729.29592120.801736.71932125.292780.79782159.863799.05182170.815818.95312179.831
#Mann= 4 ,-1 , 0
       0      .1       0  101.36     .12       0646.8817    .045       0
675.8616      .1       0
Bank Sta=646.8817,675.8616
XS Rating Curve= 0 ,0
Exp/Cntr(USF)=0,0
Exp/Cntr=0.3,0.1

Type RM Length L Ch R = 1 ,26497   ,227.8,256.9,271.2
XS GIS Cut Line= 4
2464323.94717682553701.2546152352464673.81137592554346.268526207
2464777.38606327554404.2001309972464845.85068711554448.087710384
#Sta/Elev= 30
       02228.85220.972092220.348   90.582171.697138.37762138.222153.73432131.268
165.68082129.001262.89432127.435288.54542122.541310.09872123.294343.1518 2121.65
 370.4552123.105492.45492118.643516.07232119.956 547.9262119.358557.92142121.149
579.77982121.845620.73462121.227652.58842118.866  692.592119.081717.23612118.101
762.35892118.802766.94212118.476  779.52 2114.38785.2748 2112.73796.65682112.383
   804.3 2114.23826.52332134.792854.07952151.639901.92312175.895933.78882185.249
#Mann= 5 ,-1 , 0
       0      .1       0   90.58     .12       0  692.59      .1       0
  779.52    .045       0   804.3      .1       0
Bank Sta=779.52,804.3
XS Rating Curve= 0 ,0
Exp/Cntr(USF)=0,0
Exp/Cntr=0.5,0.3

Type RM Length L Ch R = 1 ,26240   ,68.7,83.4,85.4
XS GIS Cut Line= 4
2464308.14764824553702.834568093 2464519.8613312554350.615239845
2464617.81840839554633.4268014142464655.73727698554695.044962873
#Sta/Elev= 30
       02228.193 16.89212221.94929.516742214.62996.848192164.802143.13862134.666
159.97142128.619  185.282127.509306.58092125.793325.6107 2120.79368.88572119.263
433.44622119.934510.52042116.012  580.562117.013 607.8862113.548643.9162 2116.52
 665.0312116.189  679.38 2118.36702.84832118.158 715.6572116.449 746.8662117.077
784.59542114.228838.04552114.062876.51672109.565910.42622107.877931.54762109.656
960.66632111.402965.4128 2112.91996.60522135.1461008.7012142.3861053.147 2162.43
#Mann= 6 ,-1 , 0
       0      .1       0  185.28     .12       0  580.56      .1       0
  679.38     .12       0876.5167    .045       0931.5476      .1       0
#XS Ineff= 2 , 0
             850 2108.93     965         2108.93
Permanent Ineff=
       F       F
Bank Sta=876.5167,931.5476
XS Rating Curve= 0 ,0
Exp/Cntr(USF)=0,0
Exp/Cntr=0.5,0.3

Type RM Length L Ch R = 1 ,26157   ,93.2,90.2,86.9
XS GIS Cut Line= 4
2464300.24788395553717.0541438152464481.94246261554393.273967009
2464537.24081264554633.4268014142464575.15968123554761.402982906
#Sta/Elev= 30
       02223.98718.46937 2213.2884.739362164.451   130.32135.498146.86752128.749
  171.032128.723242.13062124.677304.25872123.996324.96812119.844  465.342117.862
  549.482115.173  563.442114.972 610.7682114.937  661.552113.015697.73682115.309
779.85242114.994800.37572113.179829.10852113.241  846.742106.855853.73652105.934
  873.122106.853911.20192109.798923.51592107.035 945.7812109.7491000.523 2107.63
1023.0512118.528 1039.952121.2441044.1222124.2251056.6382138.1061080.1172149.663
#Mann= 8 ,-1 , 0
       0      .1       0  171.03     .12       0  465.34      .1       0
  549.48     .12       0  563.44      .1       0  661.55     .12       0
  846.74    .045       0  873.12      .1       0
#XS Ineff= 2 , 0
                          949.79         2111.88
Permanent Ineff=
       F       F
Bank Sta=846.74,873.12
XS Rating Curve= 0 ,0
Exp/Cntr(USF)=0,0
Exp/Cntr=0.5,0.3

Type RM Length L Ch R = 1 ,26066   ,153.1,146.7,141
XS GIS Cut Line= 4
2464175.43160817553769.1925881262464398.20496114554469.111704189
 2464459.8231226554611.3074614032464540.40071835554786.682228633
#Sta/Elev= 30
       02208.93718.573132202.52456.352632182.028106.72532148.894119.31852137.328
131.91172135.193  139.312129.957148.70252124.805169.69122122.254299.82062120.978
322.41282120.336350.19332116.852386.09742117.174471.9272 2113.43  534.092113.675
   599.52112.289 796.236 2109.67813.83052105.682833.60642104.009845.44092105.734
893.43262106.802954.71812103.868973.13432106.7781012.0262106.0221021.0912110.822
1036.1552121.913 1044.822124.1631051.9052125.2421066.3172140.8211082.4892148.407
#Mann= 7 ,-1 , 0
       0      .1       0  139.31     .12       0  534.09      .1       0
   599.5     .12       0813.8305    .045       0845.4409     .12       0
 1044.82      .1       0
#XS Ineff= 2 , 0
                          977.78         2109.08
Permanent Ineff=
       F       F
Bank Sta=813.8305,845.4409
XS Rating Curve= 0 ,0
Exp/Cntr(USF)=0,0
Exp/Cntr=0.3,0.1

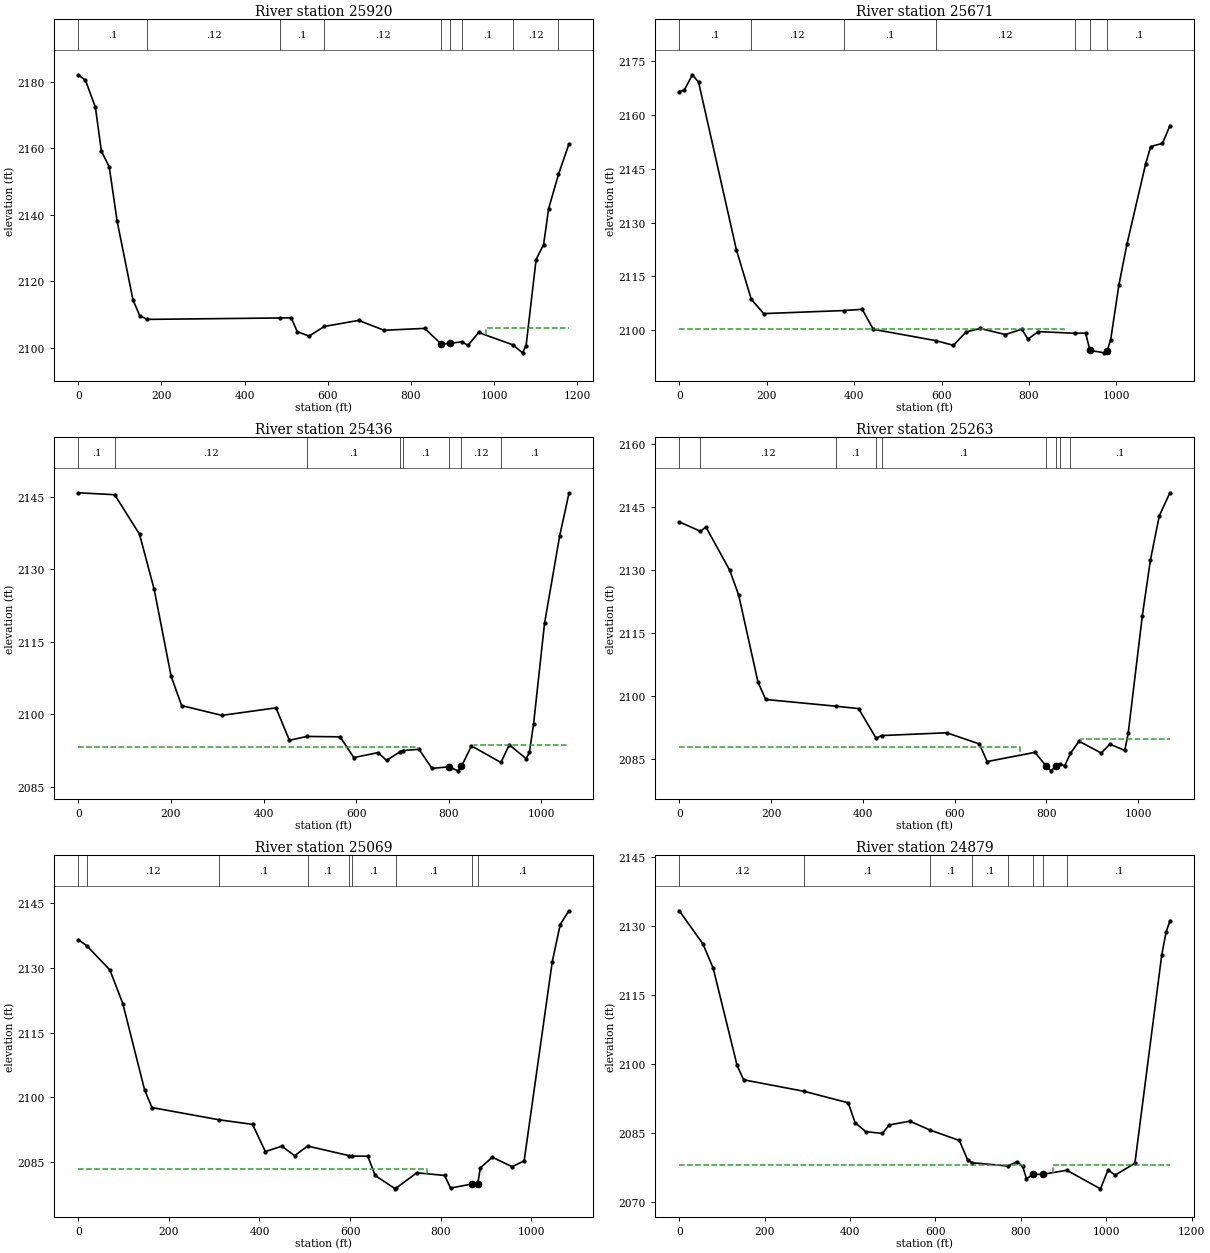
Type RM Length L Ch R = 1 ,25920   ,245.1,248.5,259.2
XS GIS Cut Line= 4
2463829.42193229553908.2284396242464259.16910964554576.548498528
2464466.14293403554808.8015686442464515.12147263554864.099918672
#Sta/Elev= 30
       02182.17217.356032180.50341.210162172.39155.476952159.27174.499352154.415
93.521742138.065131.56652114.433147.60472109.746  165.062108.584  485.122109.013
512.01442109.041526.28132104.906554.81482103.564  591.812106.469673.70482108.276
735.1709 2105.32832.75462105.877 872.713 2101.16  893.17 2101.35  922.252101.856
937.00712100.756962.27092104.643 1045.132100.9051067.9032098.5221076.5042100.657
1100.5522126.5891118.6342131.0951130.6992141.872 1154.412152.233 1179.532161.342
#Mann= 9 ,-1 , 0
       0      .1       0  165.06     .12       0  485.12      .1       0
  591.81     .12       0 872.713    .045       0  893.17     .12       0
  922.25      .1       0 1045.13     .12       0 1154.41      .1       0
#XS Ineff= 2 , 0
                          979.42         2106.13
Permanent Ineff=
       F       F
Bank Sta=872.713,893.17
XS Rating Curve= 0 ,0
Exp/Cntr(USF)=0,0
Exp/Cntr=0.3,0.1

Type RM Length L Ch R = 1 ,25671   ,237.8,235.5,233.6
XS GIS Cut Line= 4
2463703.02570365554025.1449511112464115.39339957554704.524680021
2464233.88986392554892.5390701142464282.86840251554985.756288732
#Sta/Elev= 30
       0 2166.5411.400732166.93230.117462171.232  44.155 2169.19 130.512 2122.51
  164.752108.614193.2449 2104.64  375.772105.488418.48952105.831443.65892100.267
  586.792097.102627.10172095.792656.21972099.535688.24932100.496746.03212098.798
783.46562100.294 797.5322097.519821.17292099.623  904.092099.149929.39282099.205
939.37682094.375972.47392093.697978.69722094.338986.65842097.2641005.5712112.646
1024.1512124.0971066.7452146.3981078.3732151.2331105.2532152.1031122.2772157.032
#Mann= 7 ,-1 , 0
       0      .1       0  164.75     .12       0  375.77      .1       0
  586.79     .12       0  904.09      .1       0939.3768    .045       0
978.6972      .1       0
#XS Ineff= 2 , 0
          879.01 2100.48
Permanent Ineff=
       F       F
Bank Sta=939.3768,978.6972
XS Rating Curve= 0 ,0
Exp/Cntr(USF)=0,0
Exp/Cntr=0.3,0.1

Type RM Length L Ch R = 1 ,25436   ,171.8,172.7,170.7
XS GIS Cut Line= 4
2463582.94928645554123.1020283032463908.41957518554717.164302884
2464015.85636952554892.5390701142464105.91368242555044.214544476
#Sta/Elev= 30
       02145.864    78.62145.464132.29182137.274163.95482125.853200.44282107.928
223.24772101.825309.90652099.802426.95372101.355455.85822094.644  493.462095.437
 565.3222095.368594.91092091.065647.41972092.099665.56792090.473   695.22092.308
  701.342092.521735.69382092.787763.83932088.828799.58932089.155820.13032088.324
 827.3172089.241849.04052093.485  912.552090.054930.65222093.711967.05182090.836
974.1672 2092.15983.19182098.1181006.7312118.8371039.2952136.8761059.4422145.736
#Mann= 8 ,-1 , 0
       0      .1       0    78.6     .12       0  493.46      .1       0
   695.2     .12       0  701.34      .1       0799.5893    .045       0
 827.317     .12       0  912.55      .1       0
#XS Ineff= 2 , 0
          734.16 2093.17  854.32         2093.69
Permanent Ineff=
       F       F
Bank Sta=799.5893,827.317
XS Rating Curve= 0 ,0
Exp/Cntr(USF)=0,0
Exp/Cntr=0.3,0.1

Type RM Length L Ch R = 1 ,25263   ,189.7,193.8,194.1
XS GIS Cut Line= 4
2463559.99554061554155.411955883 2463772.5436294554827.761002939
2463879.98042374554966.7968544372463958.97806664555137.431763094
#Sta/Elev= 30
       02141.417   46.042139.205 58.18512140.185110.14972129.881129.50212123.996
171.45322103.379188.23372099.203  342.042097.595390.64692097.035   428.82089.994
  440.712090.622582.57442091.284653.89142088.625670.67182084.436774.81672086.634
  799.922083.315810.20212082.235  819.672083.315  829.42 2083.87839.58272083.418
  852.142086.386 870.8632089.274919.16332086.474938.26032088.584970.38392087.077
977.93112091.1171008.786 2119.121026.4182132.3721045.7082142.8681068.8892148.346
#Mann= 9 ,-1 , 0
       0      .1       0   46.04     .12       0  342.04      .1       0
   428.8     .12       0  440.71      .1       0  799.92    .045       0
  819.67      .1       0  829.42     .12       0  852.14      .1       0
#XS Ineff= 2 , 0
          742.39 2088.01  875.72         2089.82
Permanent Ineff=
       F       F
Bank Sta=799.92,819.67
XS Rating Curve= 0 ,0
Exp/Cntr(USF)=0,0
Exp/Cntr=0.3,0.1

Type RM Length L Ch R = 1 ,25069   ,174.3,190.5,199
XS GIS Cut Line= 4
2463540.78253363554185.8428448792463638.31048782554885.876827199
2463738.00572989555109.1074779082463794.35521453555228.308310811
#Sta/Elev= 30
       02136.593   18.392135.21369.71491 2129.5798.376942121.725146.44892101.699
162.60352097.597  311.01 2094.75384.72832093.688412.99872087.375449.34642088.626
477.66822086.407  506.092088.656  597.592086.435  603.632086.335639.16222086.292
655.3167 2081.82699.74162078.717  701.172078.856747.33272082.441808.66362081.828
 821.8062078.895868.39312079.828  881.612079.745887.51772083.562913.85272086.063
957.67332083.859984.21992085.1991046.1622131.3811063.8592140.1051083.1252143.301
#Mann= 9 ,-1 , 0
       0      .1       0   18.39     .12       0  311.01      .1       0
  506.09      .1       0  597.59      .1       0  603.63      .1       0
  701.17      .1       0868.3931    .045       0  881.61      .1       0
#XS Ineff= 2 , 0
          768.72 2083.28
Permanent Ineff=
       F       F
Bank Sta=868.3931,881.61
XS Rating Curve= 0 ,0
Exp/Cntr(USF)=0,0
Exp/Cntr=0.5,0.3

Type RM Length L Ch R = 1 ,24879   ,57,54.9,54.9
XS GIS Cut Line= 4
2463529.94609428554207.5157235892463558.04498152554968.394145598
2463450.76423191555190.7578811592463491.72597267555325.346457945
#Sta/Elev= 30
       02133.228 55.41292126.04179.429262120.779135.4674 2099.68150.71472096.561
  293.232094.044395.64472091.569411.65562087.287436.36752085.318475.69922084.921
491.71012086.771539.7428 2087.58  587.832085.637655.82192083.395675.6982  2079.1
  686.03 2078.57  769.15 2077.86790.81642078.747  804.142077.795813.02232075.103
828.65112076.038   852.42076.066   907.42076.939 986.2292072.9061003.9942076.987
 1020.972075.8861066.9632078.472 1129.682123.5681139.8062128.5451148.9712131.064
#Mann= 8 ,-1 , 0
       0     .12       0  293.23      .1       0  587.83      .1       0
  686.03      .1       0  769.15      .1       0828.6511    .045       0
   852.4      .1       0   907.4      .1       0
#XS Ineff= 2 , 0
             805 2078.13     875         2078.13
Permanent Ineff=
       F       F
Bank Sta=828.6511,852.4
XS Rating Curve= 0 ,0
Exp/Cntr(USF)=0,0
Exp/Cntr=0.5,0.3

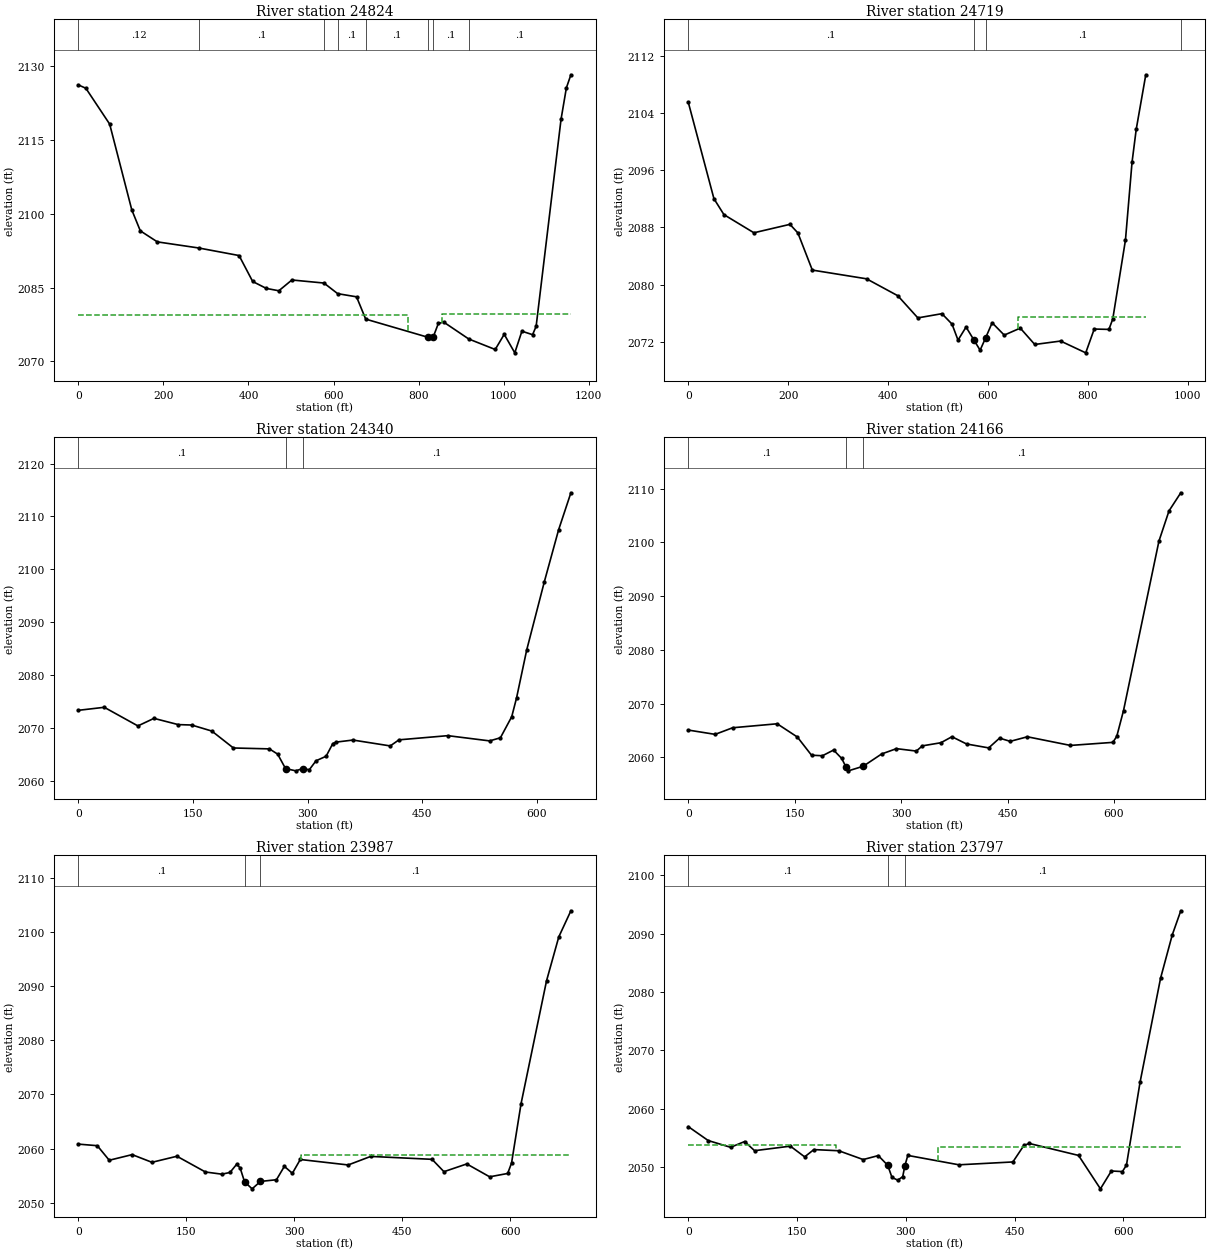
Type RM Length L Ch R = 1 ,24824   ,110.2,104.6,100.3
XS GIS Cut Line= 4
2463505.37988626554221.3300164782463534.63827252554911.827932166
2463405.90137298 555145.89502223 2463464.4181455555337.049812448
#Sta/Elev= 30
       02126.17517.576612125.50473.626872118.219125.67352100.786145.69152096.537
185.72742094.297   283.12093.055377.89972091.521 409.9172086.251441.95712084.844
471.39232084.366 502.1192086.556  577.522085.934  609.772083.777654.14732083.137
  675.662078.608   821.92074.922834.66462075.029846.44542077.719858.95622078.008
  918.042074.568980.20922072.4381001.3612075.5161026.2252071.7581042.9582076.152
1068.0572075.4471076.4232077.1361134.9892119.1861147.5382125.5761158.1622128.237
#Mann= 8 ,-1 , 0
       0     .12       0   283.1      .1       0  577.52      .1       0
  609.77      .1       0  675.66      .1       0   821.9    .045       0
834.6646      .1       0  918.04      .1       0
#XS Ineff= 2 , 0
          775.31 2079.52  854.32         2079.74
Permanent Ineff=
       F       F
Bank Sta=821.9,834.6646
XS Rating Curve= 0 ,0
Exp/Cntr(USF)=0,0
Exp/Cntr=0.5,0.3

Type RM Length L Ch R = 1 ,24719   ,378.8,379.2,367.9
XS GIS Cut Line= 4
2463385.90151811554431.5298332012463378.59354581554880.618986824
2463349.33515955555169.301731236 2463403.9508139555337.049812448
#Sta/Elev= 30
       0 2105.52    51.4 2092.01    71.4 2089.78   131.4 2087.24   203.5 2088.42
   219.4 2087.22   248.3 2082.02   356.8  2080.8   419.4 2078.43   459.5 2075.33
   507.7 2075.92   527.9 2074.46   539.9 2072.22     556 2074.05   571.6 2072.25
   584.1 2070.81     595 2072.51   608.2 2074.65   632.4 2072.92   664.5  2073.9
   693.5 2071.61   745.2 2072.09   795.5 2070.44   812.5 2073.77   841.9 2073.72
   849.6 2075.17     875 2086.21   888.2 2097.12   896.6 2101.74   915.7 2109.35
#Mann= 4 ,-1 , 0
       0      .1       0   571.6    .045       0     595      .1       0
  985.75      .1       0
#XS Ineff= 2 , 0
                          659.69         2075.48
Permanent Ineff=
       F       F
Bank Sta=571.6,595
XS Rating Curve= 0 ,0
Exp/Cntr(USF)=0,0
Exp/Cntr=0.3,0.1

Type RM Length L Ch R = 1 ,24340   ,178.3,173.7,172.7
XS GIS Cut Line= 3
2463042.62113604554928.0289435722463204.64598413555283.481292067
2463352.08894487555489.901437112
#Sta/Elev= 30
       0 2073.35    33.9 2073.92    77.9  2070.4    98.9 2071.83   130.6 2070.65
   148.2 2070.57   174.6 2069.43   202.8 2066.23   249.9 2066.06   260.7 2065.07
     271 2062.34   284.5 2061.91   293.3 2062.34   302.1 2062.12   310.9 2063.81
   324.1 2064.67   332.8 2067.05   337.2 2067.34   359.2 2067.73     408 2066.62
   419.4 2067.77   483.3 2068.56     538 2067.57   552.1 2068.16   566.9 2072.14
   573.2 2075.68   586.5 2084.76   609.6 2097.67   628.2 2107.46   644.3 2114.47
#Mann= 3 ,-1 , 0
       0      .1       0     271    .045       0   293.3      .1       0
Bank Sta=271,293.3
XS Rating Curve= 0 ,0
Exp/Cntr(USF)=0,0
Exp/Cntr=0.3,0.1

Type RM Length L Ch R = 1 ,24166   ,179.7,179.1,178.6
XS GIS Cut Line= 4
2462847.60800473555050.2371725282462934.88630905555163.463704973
2463115.46265194555379.5104009252463276.69152951555595.557096876
#Sta/Elev= 30
       0 2065.07    37.9 2064.27    62.6  2065.5   125.3 2066.24   153.8 2063.77
   173.7 2060.39   189.1 2060.29   204.8 2061.35   216.3 2059.78     222 2058.26
   225.6 2057.48   246.5 2058.33   272.5 2060.62   293.4 2061.61   321.4 2061.16
   329.9 2062.13     356 2062.71   371.6 2063.83   392.2 2062.48   423.4 2061.75
   438.7 2063.57   453.7 2062.97   477.9 2063.82   538.6 2062.21   598.4 2062.78
   603.9 2063.91   613.4 2068.71   663.3 2100.24   677.5 2105.87   694.1 2109.24
#Mann= 3 ,-1 , 0
       0      .1       0     222    .045       0   246.5      .1       0
Bank Sta=222,246.5
XS Rating Curve= 0 ,0
Exp/Cntr(USF)=0,0
Exp/Cntr=0.3,0.1

Type RM Length L Ch R = 1 ,23987   ,187.9,190.2,191.2
XS GIS Cut Line= 3
2462720.19942561555195.846977241 2462949.0781855555435.839018171
2463175.15739198555706.151112872
#Sta/Elev= 30
       0 2060.83    26.3 2060.54    42.9 2057.85    74.7 2058.89   102.2 2057.47
   136.9 2058.59   176.5 2055.68   199.2 2055.28   210.5 2055.59   219.8  2057.1
   224.6 2056.46   230.8 2053.87   241.3 2052.57   252.9 2053.94   275.1 2054.25
   286.1 2056.72   297.2 2055.44   308.2 2057.99   374.7 2056.98     406 2058.56
   491.2 2058.02   507.7 2055.74   539.4 2057.17   571.2 2054.79   596.2 2055.41
   601.6 2057.34   614.8 2068.31   650.2 2091.01   667.2 2099.11     684 2103.93
#Mann= 3 ,-1 , 0
       0      .1       0   230.8    .045       0   252.9      .1       0
#XS Ineff= 2 , 0
                          308.65         2058.74
Permanent Ineff=
       F       F
Bank Sta=230.8,252.9
XS Rating Curve= 0 ,0
Exp/Cntr(USF)=0,0
Exp/Cntr=0.3,0.1

Type RM Length L Ch R = 1 ,23797   ,302.5,302.4,300.5
XS GIS Cut Line= 4
 2462556.3883953555312.8548560292462693.51038687555411.265191381
2462811.46475547555578.3672135592463027.71443123 555794.61688932
#Sta/Elev= 30
       0 2056.91    27.5 2054.52    58.4 2053.36    77.7 2054.35    91.5 2052.78
   140.8 2053.56   160.5 2051.72   173.2 2052.97   207.5 2052.77   241.2 2051.26
     262 2051.94     275 2050.28   280.9  2048.2   288.8 2047.73   295.7 2048.32
   298.6 2050.16   302.7 2051.97   373.2 2050.36   447.6 2050.85   462.8 2053.69
   470.2 2054.02   538.1 2051.97   568.3 2046.24   583.4  2049.3   598.6  2049.2
   604.2 2050.31     623 2064.56   651.2 2082.34   667.3 2089.76   679.1 2093.91
#Mann= 3 ,-1 , 0
       0      .1       0     275    .045       0   298.6      .1       0
#XS Ineff= 2 , 0
          203.39 2053.72  343.87         2053.49
Permanent Ineff=
       F       F
Bank Sta=275,298.6
XS Rating Curve= 0 ,0
Exp/Cntr(USF)=0,0
Exp/Cntr=0.3,0.1