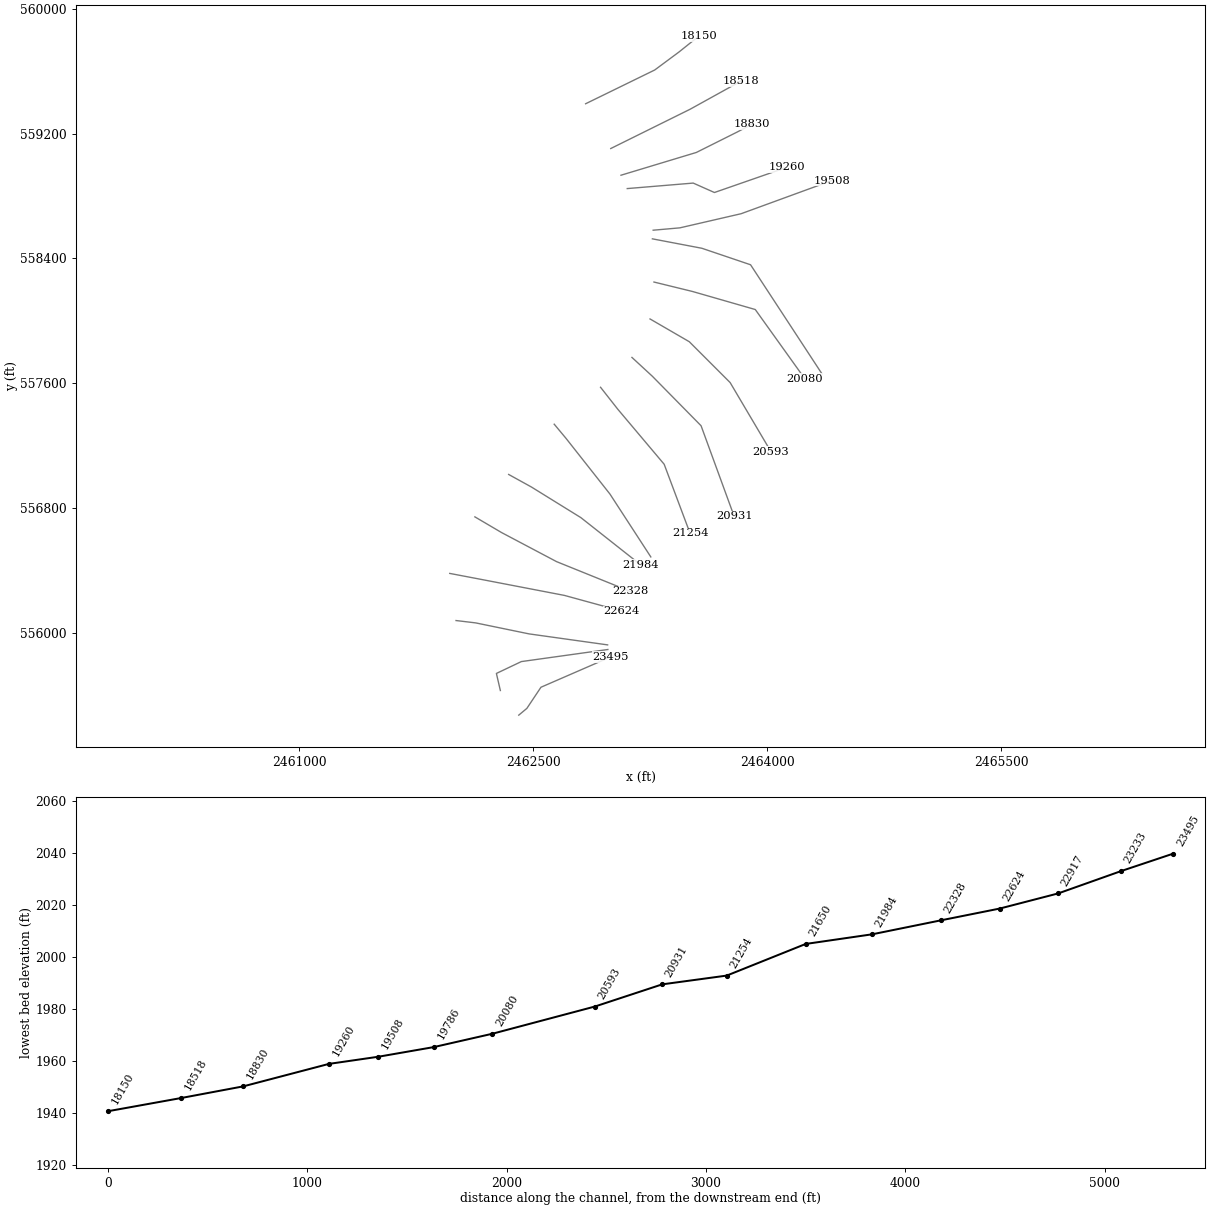
HEC-RAS study LITTLEFK.prj: LITTLEFK

--- LITTLEFK.g01 (geometry) --- (continued)

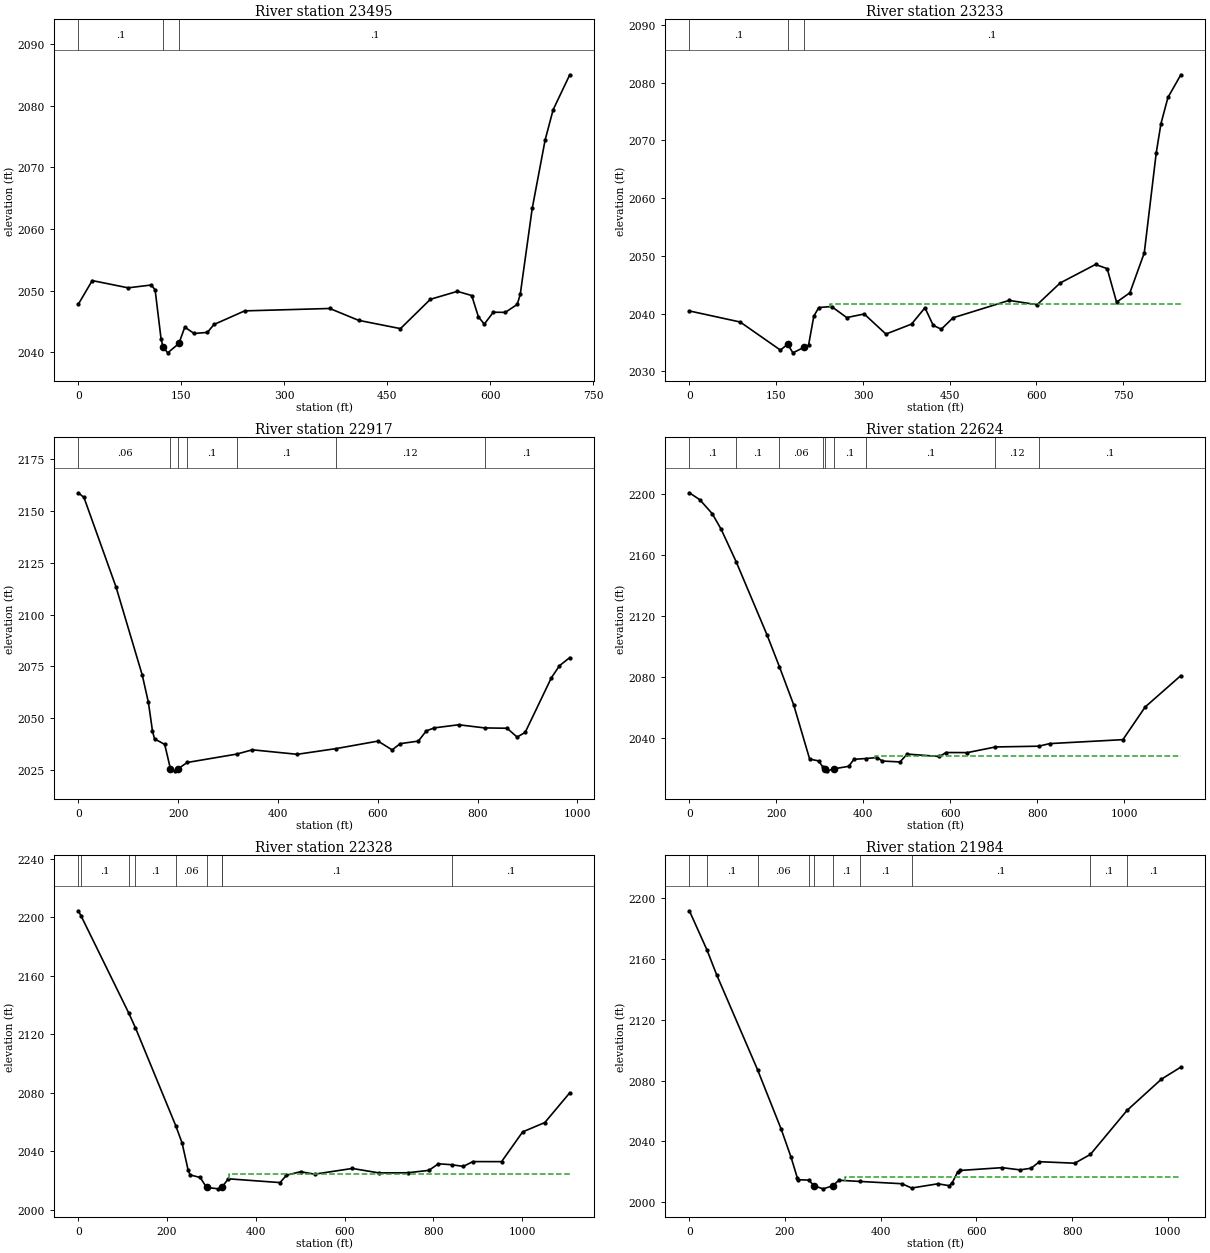
Type RM Length L Ch R = 1 ,23495   ,271.1,261.3,250.7
XS GIS Cut Line= 4
2462405.57824042555471.4655361632462457.64883143555514.942658088
2462547.93700287555650.3749152522462992.92870498555843.849568342
#Sta/Elev= 30
       0 2047.78    20.3 2051.63    72.6 2050.45   106.2 2050.91   111.9 2050.12
   120.5 2042.19   123.4 2040.82   130.3  2039.9   146.5 2041.42   155.1 2044.07
   168.7 2043.04     188 2043.22   197.6  2044.5   242.3 2046.71   366.2  2047.1
   408.1 2045.18   469.2 2043.83   512.8 2048.59   552.1 2049.88     573  2049.2
   582.7 2045.75   591.3 2044.56   604.4 2046.49   621.9 2046.47   639.3 2047.76
   643.7  2049.4   661.1 2063.33     680 2074.49   691.6 2079.36   715.8 2085.03
#Mann= 3 ,-1 , 0
       0      .1       0   123.4    .045       0   146.5      .1       0
Bank Sta=123.4,146.5
XS Rating Curve= 0 ,0
Exp/Cntr(USF)=0,0
Exp/Cntr=0.3,0.1

Type RM Length L Ch R = 1 ,23233   ,324.2,316.5,308.1
XS GIS Cut Line= 4
2462287.58812369555629.3150384582462262.21256066555738.804029101
2462422.17847836555814.8283703792462976.80581722555892.218231615
#Sta/Elev= 30
       0 2040.45    87.8 2038.53   157.3 2033.67   169.9 2034.68   178.9 2033.19
   197.7 2034.12     206 2034.51   215.1 2039.55   223.7 2041.04   245.8 2041.21
     272  2039.3   302.2 2039.92   339.7 2036.44     384 2038.17   407.2    2041
   421.5 2037.94   435.5 2037.29   455.7 2039.26   552.6 2042.27   601.1 2041.53
   640.9 2045.29     702  2048.5   722.2 2047.77   738.4 2041.97   761.4 2043.59
   786.3 2050.51     807 2067.85   815.1 2072.88   827.2 2077.43   849.5 2081.36
#Mann= 3 ,-1 , 0
       0      .1       0   169.9    .045       0   197.7      .1       0
#XS Ineff= 2 , 0
                          243.64         2041.68
Permanent Ineff=
       F       F
Bank Sta=169.9,197.7
XS Rating Curve= 0 ,0
Exp/Cntr(USF)=0,0
Exp/Cntr=0.3,0.1

Type RM Length L Ch R = 1 ,22917   ,292,292.9,292.8
XS GIS Cut Line= 4
2462003.50347778556077.9229380112462129.37182621  556062.8187362
2462471.73373392555992.3324610822462975.20712763555921.846185964
#Sta/Elev= 30
       0 2158.8911.322212156.63375.781362113.235128.17342070.783140.42512057.657
148.5928 2043.88152.67672040.004173.09622037.338  184.652025.515193.51572024.563
  199.782025.516  218.082028.595  317.492032.656348.7037 2034.72438.54942032.552
  516.272035.297600.52492038.934628.79792034.669 644.9542037.687681.30512038.939
697.46112043.909713.61712045.331762.08532046.821  814.292045.297859.02152045.135
879.21662040.881895.3726 2043.13947.87972069.528964.03582075.341984.69742079.276
#Mann= 7 ,-1 , 0
       0     .06       0  184.65    .045       0  199.78     .06       0
  218.08      .1       0  317.49      .1       0  516.27     .12       0
  814.29      .1       0
Bank Sta=184.65,199.78
XS Rating Curve= 0 ,0
Exp/Cntr(USF)=0,0
Exp/Cntr=0.3,0.1

Type RM Length L Ch R = 1 ,22624   ,300.6,296.2,290.6
XS GIS Cut Line= 4
2461963.22560629556380.0069742332462174.68443164556339.729102736
2462698.29676109556239.0344239962463065.83233849556138.339745256
#Sta/Elev= 30
       02200.60823.942292196.067 52.44572186.97972.80528 2176.89   107.42155.583
178.40472107.694  206.762086.959239.76212061.892276.42182026.441296.78822025.239
  306.122021.531   311.12020.018317.15472018.738  331.472020.019366.03422021.685
378.25412026.266  405.482026.802431.20692027.438443.42682025.146484.1597 2024.56
500.45292029.688574.74092028.124590.06532030.716638.94482030.662  703.562034.362
   803.22034.857827.73282036.544996.36622039.1391047.5452060.4991129.5472081.031
#Mann= 9 ,-1 , 0
       0      .1       0   107.4      .1       0  206.76     .06       0
  306.12      .1       0   311.1    .045       0  331.47      .1       0
  405.48      .1       0  703.56     .12       0   803.2      .1       0
#XS Ineff= 2 , 0
                          426.34          2028.6
Permanent Ineff=
       F       F
Bank Sta=311.1,331.47
XS Rating Curve= 0 ,0
Exp/Cntr(USF)=0,0
Exp/Cntr=0.3,0.1

Type RM Length L Ch R = 1 ,22328   ,344.9,343.8,342.2
XS GIS Cut Line= 4
2462124.33709227556742.5078176982462295.51804613556641.813138958
2462647.94942172556455.527983288 2463121.2144118556264.208093681
#Sta/Elev= 30
       02204.433    6.812200.596  113.382134.654  128.812124.357   219.62057.412
233.92182045.544247.54962027.024252.01942023.726274.6414 2021.95  289.142015.173
 315.3612014.185  323.142015.172  324.422015.547 337.9832021.049454.74182018.463
469.19072023.498500.86152025.906532.53232024.214617.50952028.133677.91222025.075
742.62952025.187790.08882026.824811.66122031.308   841.42030.696867.74952029.533
889.32192032.824954.03912032.7921001.4982053.1441051.5212059.5481107.7092079.896
#Mann= 9 ,-1 , 0
       0      .1       0    6.81      .1       0  113.38      .1       0
  128.81      .1       0   219.6     .06       0  289.14    .045       0
  323.14     .06       0  324.42      .1       0   841.4      .1       0
#XS Ineff= 2 , 0
                          340.74         2024.45
Permanent Ineff=
       F       F
Bank Sta=289.14,323.14
XS Rating Curve= 0 ,0
Exp/Cntr(USF)=0,0
Exp/Cntr=0.3,0.1

Type RM Length L Ch R = 1 ,21984   ,339.1,333.6,321.7
XS GIS Cut Line= 4
2462340.83065156557014.3834502972462486.83793574556933.827707305
2462804.02617377556737.4730837612463186.66595298 556435.38904754
#Sta/Elev= 30
       02191.529   36.962165.65257.007382149.476  142.432087.152192.06662047.898
212.40632029.729 225.5312016.085227.80352014.835   249.52014.551260.7344 2010.81
279.55212008.823299.57632010.789 312.4832014.454  357.032013.676444.2066 2012.18
  464.572009.359519.47722012.135543.26572010.886549.27182012.741560.66352019.782
566.35942020.914653.70932022.739691.05852021.292 714.4522022.376731.82892026.656
805.58582025.666  838.322031.455  914.872060.368 986.644 2080.871027.314 2088.81
#Mann= 10 ,-1 , 0
       0      .1       0   36.96      .1       0  142.43     .06       0
   249.5      .1       0260.7344    .045       0299.5763      .1       0
  357.03      .1       0  464.57      .1       0  838.32      .1       0
  914.87      .1       0
#XS Ineff= 2 , 0
                          325.93         2016.61
Permanent Ineff=
       F       F
Bank Sta=260.7344,299.5763
XS Rating Curve= 0 ,0
Exp/Cntr(USF)=0,0
Exp/Cntr=0.3,0.1

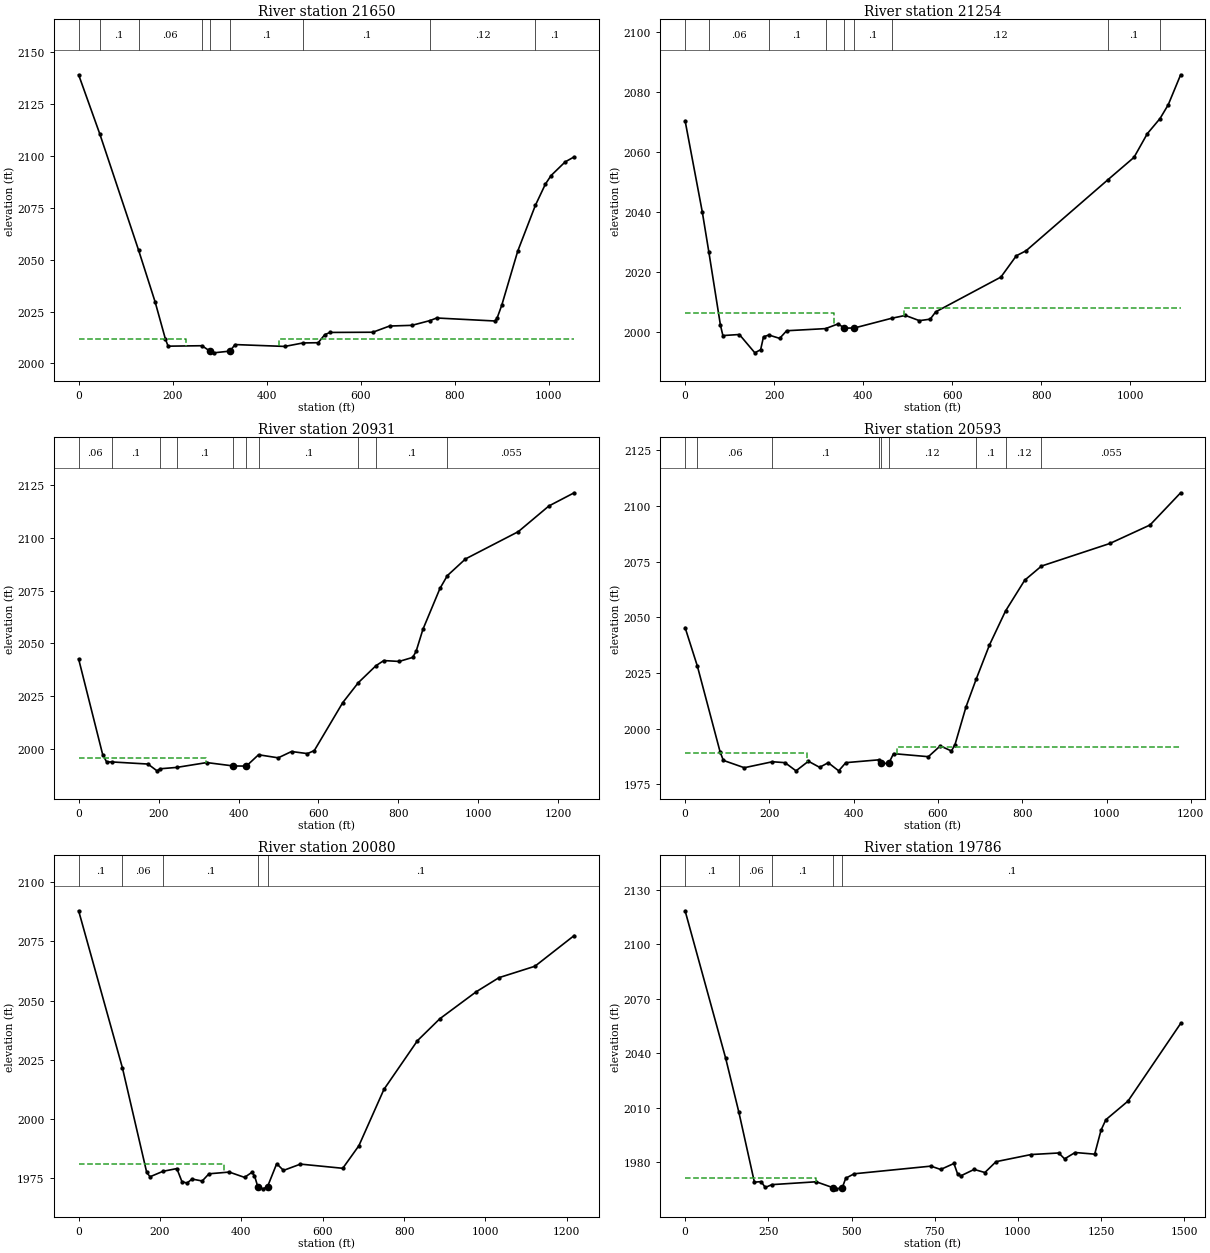
Type RM Length L Ch R = 1 ,21650   ,392.6,395.9,389.8
XS GIS Cut Line= 4
2462632.84521991557336.6064222662462708.36622897  557245.9812114
2462990.31132944556888.5151018722463252.11749416 556485.73638691
#Sta/Elev= 30
       02139.035   45.252110.371   127.52054.544162.65922029.618184.51972011.743
190.21582008.321  262.262008.536  279.052005.942287.05082005.109  321.622005.943
332.62022009.094438.30252008.194  477.122009.874509.35212009.982 523.4422013.892
534.55522014.938625.41532015.033661.05292018.017708.76032018.357  747.252020.658
761.23852021.891885.27782020.445890.04862022.028899.59012027.991933.67882054.135
  971.062076.107992.39572086.3561004.5462090.5091034.4562097.0761053.6312099.489
#Mann= 9 ,-1 , 0
       0      .1       0   45.25      .1       0   127.5     .06       0
  262.26      .1       0  279.05    .045       0  321.62      .1       0
  477.12      .1       0  747.25     .12       0  971.06      .1       0
#XS Ineff= 2 , 0
          228.81 2011.88  426.34         2011.88
Permanent Ineff=
       F       F
Bank Sta=279.05,321.62
XS Rating Curve= 0 ,0
Exp/Cntr(USF)=0,0
Exp/Cntr=0.3,0.1

Type RM Length L Ch R = 1 ,21254   ,322.5,323.4,326.5
XS GIS Cut Line= 4
2462929.89452219557573.2389173062463040.65866881 557432.26636707
2463337.70797109557079.8349914782463503.85419101556636.778405021
#Sta/Elev= 30
       0  2070.338.595112039.924    53.5 2026.42 79.29112002.247 84.89081998.689
121.92411999.042156.7613 1992.93  169.711993.986176.18441998.284  188.221998.871
212.46851997.751228.16242000.294  315.552001.006343.89152002.586357.73752001.162
 380.447 2001.22  464.072004.452494.95892005.405526.34672003.656550.76852004.162
562.96582006.584 709.5612018.187744.26752025.293766.01592026.946  949.872050.618
1008.6012058.0871038.5052065.981 1067.092071.0341085.4972075.6121113.3852085.615
#Mann= 9 ,-1 , 0
       0      .1       0    53.5     .06       0  188.22      .1       0
  315.55      .1       0357.7375    .045       0 380.447      .1       0
  464.07     .12       0  949.87      .1       0 1067.09     .12       0
#XS Ineff= 2 , 0
           333.5 2006.13  492.18          2007.9
Permanent Ineff=
       F       F
Bank Sta=357.7375,380.447
XS Rating Curve= 0 ,0
Exp/Cntr(USF)=0,0
Exp/Cntr=0.3,0.1

Type RM Length L Ch R = 1 ,20931   ,336.9,338.2,337.2
XS GIS Cut Line= 4
2463131.28387967557764.5588069132463262.18696204557643.725192424
2463574.34046613557326.5369543922463785.79929149556747.542551635
#Sta/Elev= 30
       02042.611 60.24351997.20570.033911993.772   83.741993.775173.47991992.781
196.05071989.561  203.681990.535  244.941991.175320.55761993.482386.9668 1991.88
419.55571991.809  449.98 1997.19499.2095 1995.73532.50741998.723 572.4261997.735
 589.5341999.178660.64332021.903  699.592031.371  743.752039.427763.32422041.856
  801.652041.445835.71732043.365844.23422046.259861.26792056.687903.85212076.069
  922.372082.147967.72832090.0581099.7392102.9881176.3912115.1821239.5732121.433
#Mann= 10 ,-1 , 0
       0     .06       0   83.74      .1       0  203.68      .1       0
  244.94      .1       0386.9668    .045       0419.5557      .1       0
  449.98      .1       0  699.59     .12       0  743.75      .1       0
  922.37    .055       0
#XS Ineff= 2 , 0
          317.63 1995.44
Permanent Ineff=
       F       F
Bank Sta=386.9668,419.5557
XS Rating Curve= 0 ,0
Exp/Cntr(USF)=0,0
Exp/Cntr=0.3,0.1

Type RM Length L Ch R = 1 ,20593   ,502.1,513.2,513.4
XS GIS Cut Line= 4
2463247.08276023558011.2607698272463498.81945708557865.253485653
 2463760.6256218557603.4473209282464022.43178653557160.390734471
#Sta/Elev= 30
       02045.338   29.212027.98482.84358 1989.6890.74976 1985.71140.50291982.417
  207.29  1985.1237.08241984.687263.18391981.015292.63261985.321319.19361982.594
339.61071984.662364.44851981.018 381.4191984.693  460.471985.972465.16671984.356
483.24241984.362494.55611988.743577.19851987.368605.4828 1992.21632.04381989.936
640.52911992.823666.55692009.724  690.512022.079722.31082037.565  760.332052.777
805.94172066.635   845.72072.975 1007.832083.1051103.2962091.4181175.8922105.881
#Mann= 9 ,-1 , 0
       0      .1       0   29.21     .06       0  207.29      .1       0
  460.47     .12       0465.1667    .045       0483.2424     .12       0
  690.51      .1       0  760.33     .12       0   845.7    .055       0
#XS Ineff= 2 , 0
          290.32 1989.15   503.7         1991.62
Permanent Ineff=
       F       F
Bank Sta=465.1667,483.2424
XS Rating Curve= 0 ,0
Exp/Cntr(USF)=0,0
Exp/Cntr=0.3,0.1

Type RM Length L Ch R = 1 ,20080   ,295.1,293.9,291.7
XS GIS Cut Line= 4
2463272.25642991558247.8932648672463518.95839282558187.476457622
2463921.73710779558071.6775770712464238.92534582557628.620990613
#Sta/Elev= 30
       02087.881  107.692021.554167.29031977.508175.52671975.656  207.321977.954
 241.4181979.107253.77261973.652266.25631972.966278.74241974.691303.71461973.867
320.36271976.906370.30711977.632407.76541975.388425.62321977.495432.08851976.175
  440.321971.505453.54771970.557  464.361971.508 486.8441981.168503.49211978.332
545.23111980.992649.16311979.225688.81231988.747750.4049 2012.52832.86332033.089
887.83562042.333977.16552053.702 1033.172059.6621121.6142064.4861217.9792077.427
#Mann= 5 ,-1 , 0
       0      .1       0  107.69     .06       0  207.32      .1       0
  440.32    .045       0  464.36      .1       0
#XS Ineff= 2 , 0
           357.2 1980.92
Permanent Ineff=
       F       F
Bank Sta=440.32,464.36
XS Rating Curve= 0 ,0
Exp/Cntr(USF)=0,0
Exp/Cntr=0.3,0.1

Type RM Length L Ch R = 1 ,19786   ,265.6,278.2,274.5
XS GIS Cut Line= 4
2463262.18696204558524.8036314022463579.37520007558464.386824158
2463891.52870416558358.6574114812464349.68949243557658.829394235
#Sta/Elev= 30
       02118.472121.82712037.357  161.672007.499208.23581969.077228.5954  1969.4
240.81111966.172  261.031967.735394.02041969.301  444.631966.024453.14541965.415
  472.211966.024 482.7081971.277508.04731973.702738.66691977.915767.87811976.074
807.75521979.376819.31271973.312827.98081972.531868.43191976.095900.7953  1974.4
 934.2621980.3721039.4431984.2891122.6961985.153 1140.321981.9191171.8151985.416
1230.6821984.5041249.8061997.7321264.149 2003.45 1330.732013.7121488.9272056.434
#Mann= 5 ,-1 , 0
       0      .1       0  161.67     .06       0  261.03      .1       0
  444.63    .045       0  472.21      .1       0
#XS Ineff= 2 , 0
          392.87 1971.22
Permanent Ineff=
       F       F
Bank Sta=444.63,472.21
XS Rating Curve= 0 ,0
Exp/Cntr(USF)=0,0
Exp/Cntr=0.3,0.1

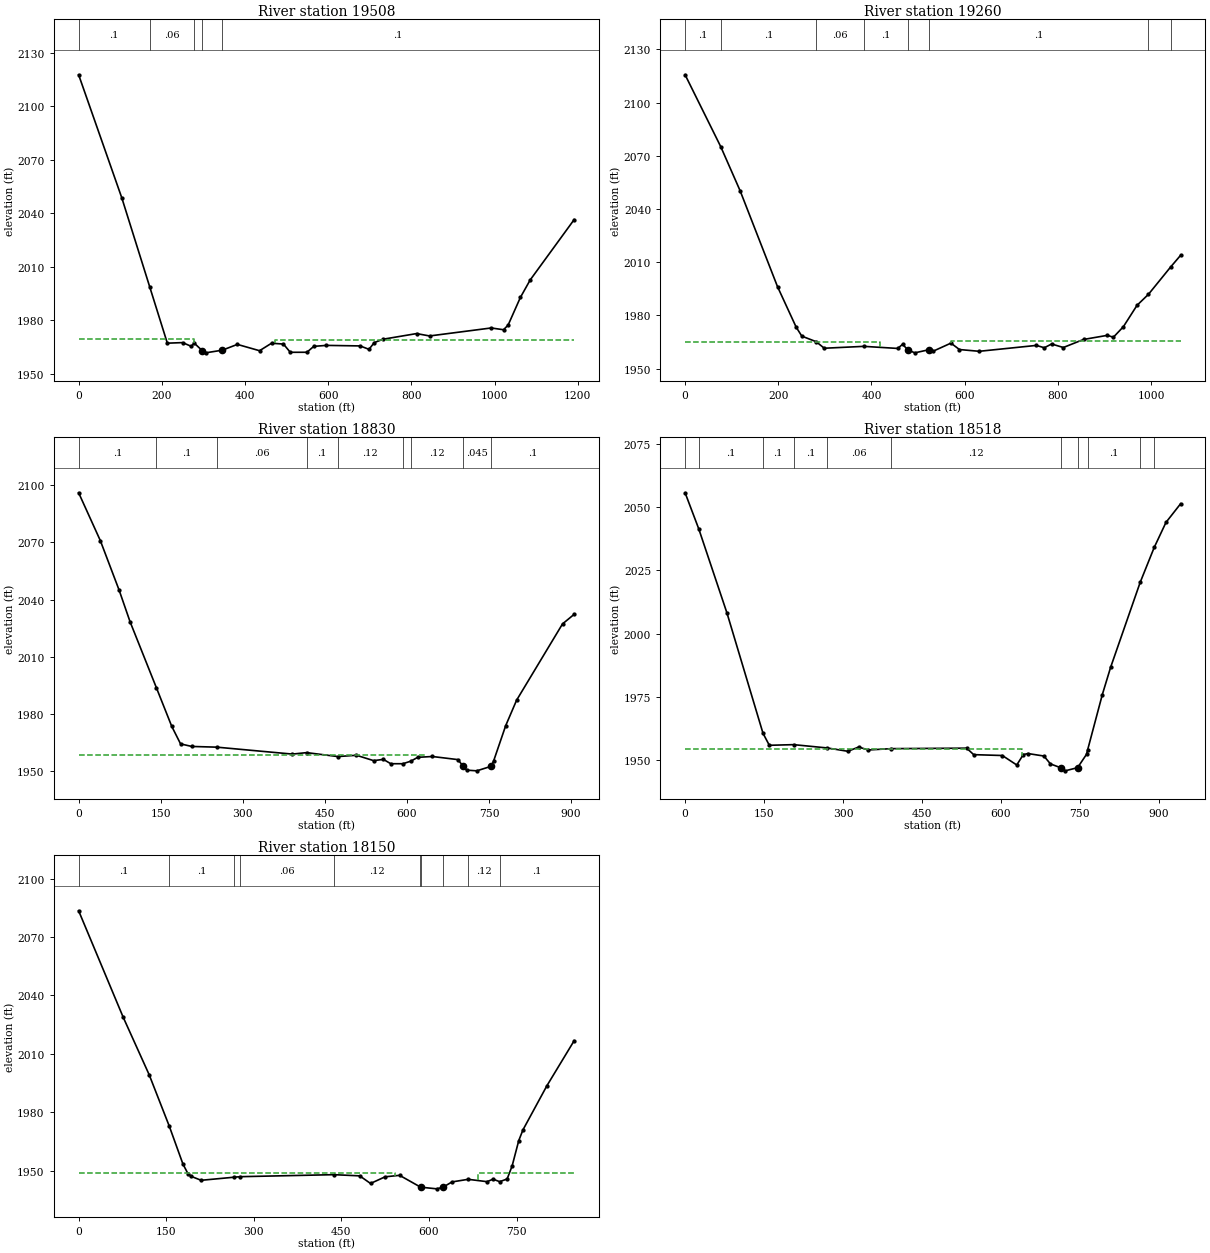
Type RM Length L Ch R = 1 ,19508   ,259,248,222
XS GIS Cut Line= 4
2463267.22169597 558580.185704712463438.40264983558595.289906521
2463831.11189692558685.9151173872464410.10629968558897.373942742
#Sta/Elev= 30
       0 2117.58103.92562048.477  170.761998.785213.2487 1967.12250.19481967.437
270.72051965.337  277.991967.122   296.81963.008305.2154  1961.7345.2404 1963.18
381.55891966.431434.92561962.892463.66151967.078492.39731966.619508.81791962.003
548.70081962.022565.37791965.337 595.7781965.877676.68791965.577  697.98 1963.67
710.75521967.443732.0474 1969.34812.41231972.496843.60461971.165 991.8111975.641
  1021.41974.6561032.4591977.244 1061.951992.7391085.4962002.5471191.2772036.407
#Mann= 5 ,-1 , 0
       0      .1       0  170.76     .06       0  277.99      .1       0
   296.8    .045       0345.2404      .1       0
#XS Ineff= 2 , 0
          276.54 1969.45  472.43         1968.86
Permanent Ineff=
       F       F
Bank Sta=296.8,345.2404
XS Rating Curve= 0 ,0
Exp/Cntr(USF)=0,0
Exp/Cntr=0.3,0.1

Type RM Length L Ch R = 1 ,19260   ,401.6,429.4,453.2
XS GIS Cut Line= 4
2463101.07547605558847.0266033722463523.99312676558882.269740931
2463659.93094306558821.8529336872464123.12646527558982.964419671
#Sta/Elev= 30
       02115.731   76.532075.177118.07742050.345198.35471996.251238.49341973.374
 250.535 1968.36  281.231965.241298.7014 1961.54  383.571962.599 456.3021961.428
466.79051963.755478.30221960.567493.05411958.945 523.6951960.723532.44951959.879
570.5871 1964.42588.82731960.804 631.1781959.813753.99471963.137770.93491961.818
786.69211963.929811.82921961.954855.25781966.496906.4568 1968.82 919.1621967.729
 940.6571973.681969.98271985.749  994.49 1991.95 1041.972007.3091063.5582013.959
#Mann= 8 ,-1 , 0
       0      .1       0   76.53      .1       0  281.23     .06       0
  383.57      .1       0478.3022    .045       0 523.695      .1       0
  994.49     .12       0 1041.97      .1       0
#XS Ineff= 2 , 0
          418.11 1964.91  571.19          1965.9
Permanent Ineff=
       F       F
Bank Sta=478.3022,523.695
XS Rating Curve= 0 ,0
Exp/Cntr(USF)=0,0
Exp/Cntr=0.3,0.1

Type RM Length L Ch R = 1 ,18830   ,308.4,312.4,305.4
XS GIS Cut Line= 4
2463060.79760456558932.6170803012463544.13206251559078.624364474
2463805.93822723559209.5274468372463901.59817204559259.874786207
#Sta/Elev= 30
       02095.99739.641082070.94673.986952045.005 93.9619 2028.45  142.131993.841
170.26021973.564186.30571964.418206.7821 1963.08  252.651962.705390.63711959.072
  416.831959.843  473.691957.782507.82761958.454539.13261955.646557.02111956.302
570.4376 1954.03  592.741954.024   607.51955.406 619.6311957.374646.46391957.813
693.33191956.179  702.85 1952.69709.07381950.674727.67791950.299753.79511952.661
758.26731955.297780.62791974.025800.54191987.343884.40992027.283905.71482032.316
#Mann= 9 ,-1 , 0
       0      .1       0  142.13      .1       0  252.65     .06       0
  416.83      .1       0  473.69     .12       0  592.74      .1       0
   607.5     .12       0  702.85    .045       0753.7951      .1       0
#XS Ineff= 2 , 0
          633.74  1958.6
Permanent Ineff=
       F       F
Bank Sta=702.85,753.7951
XS Rating Curve= 0 ,0
Exp/Cntr(USF)=0,0
Exp/Cntr=0.3,0.1

Type RM Length L Ch R = 1 ,18518   ,366.5,367.3,370.6
XS GIS Cut Line= 4
2462995.34606337 559103.798034162463503.85419101559355.534731011
2463740.48668605559486.4378133732463831.11189692559536.785152743
#Sta/Elev= 30
       02055.578   25.932041.34979.669042008.032     1481960.636160.00871955.881
   206.21956.139  270.071954.832309.35561953.509329.61471955.197348.16571954.042
  392.131954.562534.92721954.753548.31711952.188602.71051951.852 630.1381948.109
642.63971952.232651.46911952.625681.7657 1951.64694.13551948.533  713.321947.045
722.10431945.798  745.661947.047762.70431952.321  764.971954.206792.73951975.922
808.41671986.639  864.572020.176  891.362034.033913.63152043.878941.50622051.263
#Mann= 11 ,-1 , 0
       0      .1       0   25.93      .1       0     148      .1       0
   206.2      .1       0  270.07     .06       0  392.13     .12       0
  713.32    .045       0  745.66     .12       0  764.97      .1       0
  864.57     .12       0  891.36      .1       0
#XS Ineff= 2 , 0
           640.6 1954.61
Permanent Ineff=
       F       F
Bank Sta=713.32,745.66
XS Rating Curve= 0 ,0
Exp/Cntr(USF)=0,0
Exp/Cntr=0.3,0.1

Type RM Length L Ch R = 1 ,18150   ,265,261,256.3
XS GIS Cut Line= 4
2462834.23457739 559390.777868572463277.29116385559607.271427861
 2463433.3679159559723.0703084132463559.23626432559823.764987153
#Sta/Elev= 30
       02083.43976.252042028.834 120.772  1999.3  155.211972.909178.64791953.422
187.55191948.319192.00391947.212 209.8121945.094  266.721946.696  276.831946.951
  437.311947.985481.38351947.374499.91231943.465524.81591946.883549.71941947.643
  585.281941.645  585.861941.566 613.3191940.712  624.161941.567639.37231944.259
   667.11945.596699.47321944.387709.71821945.675  721.071944.389  733.851945.776
742.3876 1952.45753.7709  1965.5760.94321970.984801.92321993.614848.65482016.766
#Mann= 10 ,-1 , 0
       0      .1       0  155.21      .1       0  266.72      .1       0
  276.83     .06       0  437.31     .12       0  585.28      .1       0
  585.86    .045       0  624.16      .1       0   667.1     .12       0
  721.07      .1       0
#XS Ineff= 2 , 0
          541.84 1948.86  683.13         1948.86
Permanent Ineff=
       F       F
Bank Sta=585.86,624.16
XS Rating Curve= 0 ,0
Exp/Cntr(USF)=0,0
Exp/Cntr=0.3,0.1