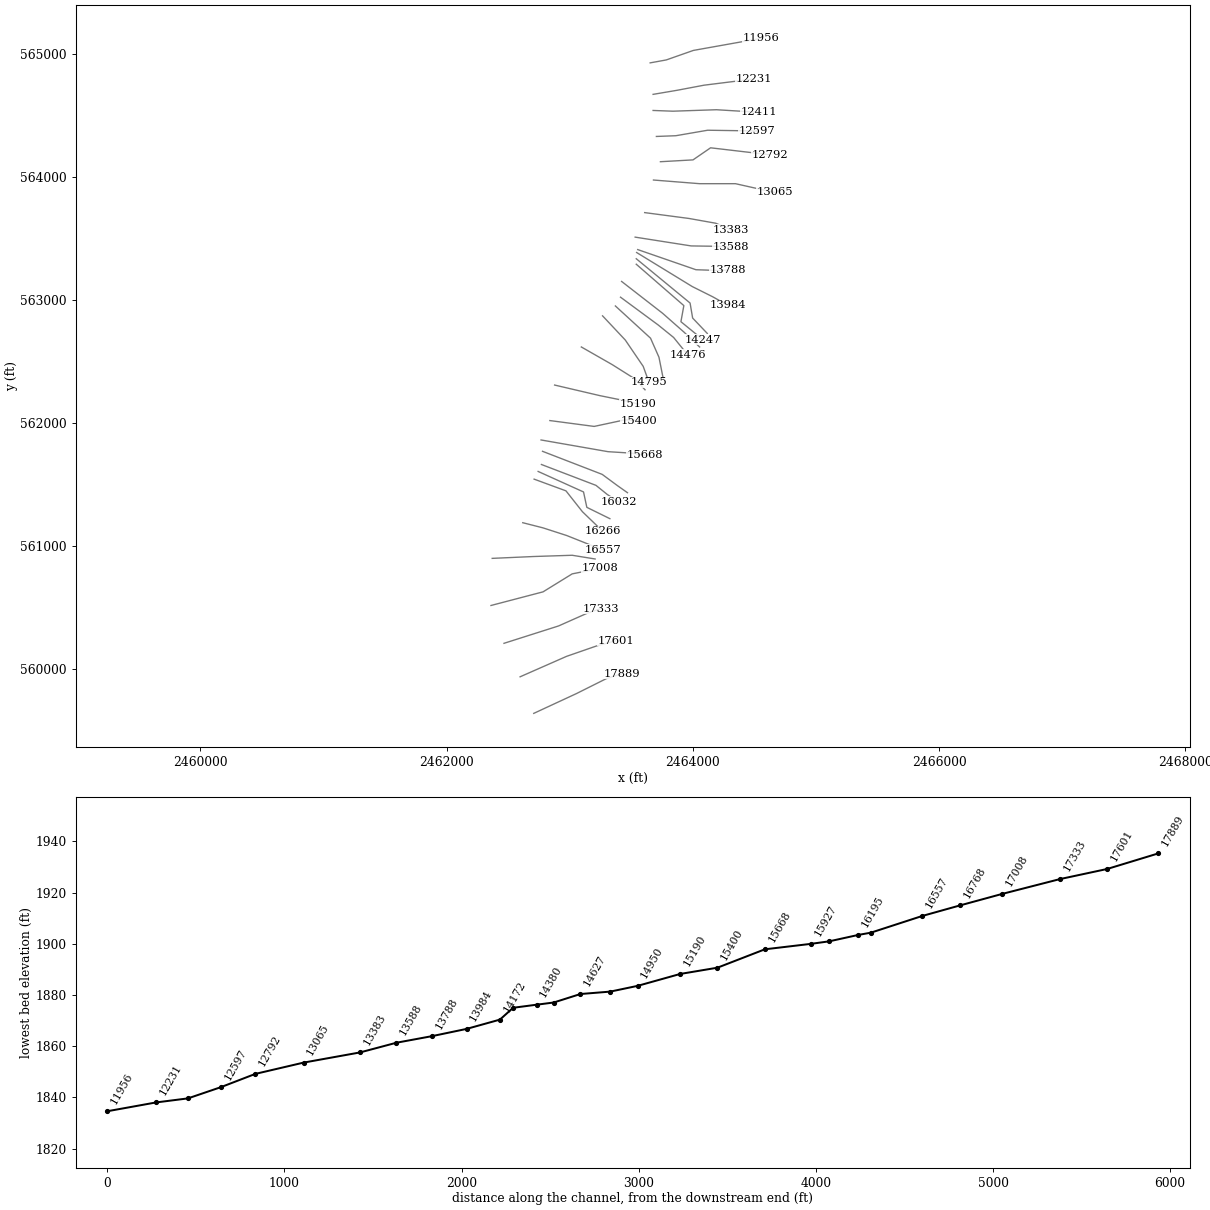
HEC-RAS study LITTLEFK.prj: LITTLEFK

--- LITTLEFK.g01 (geometry) --- (continued)

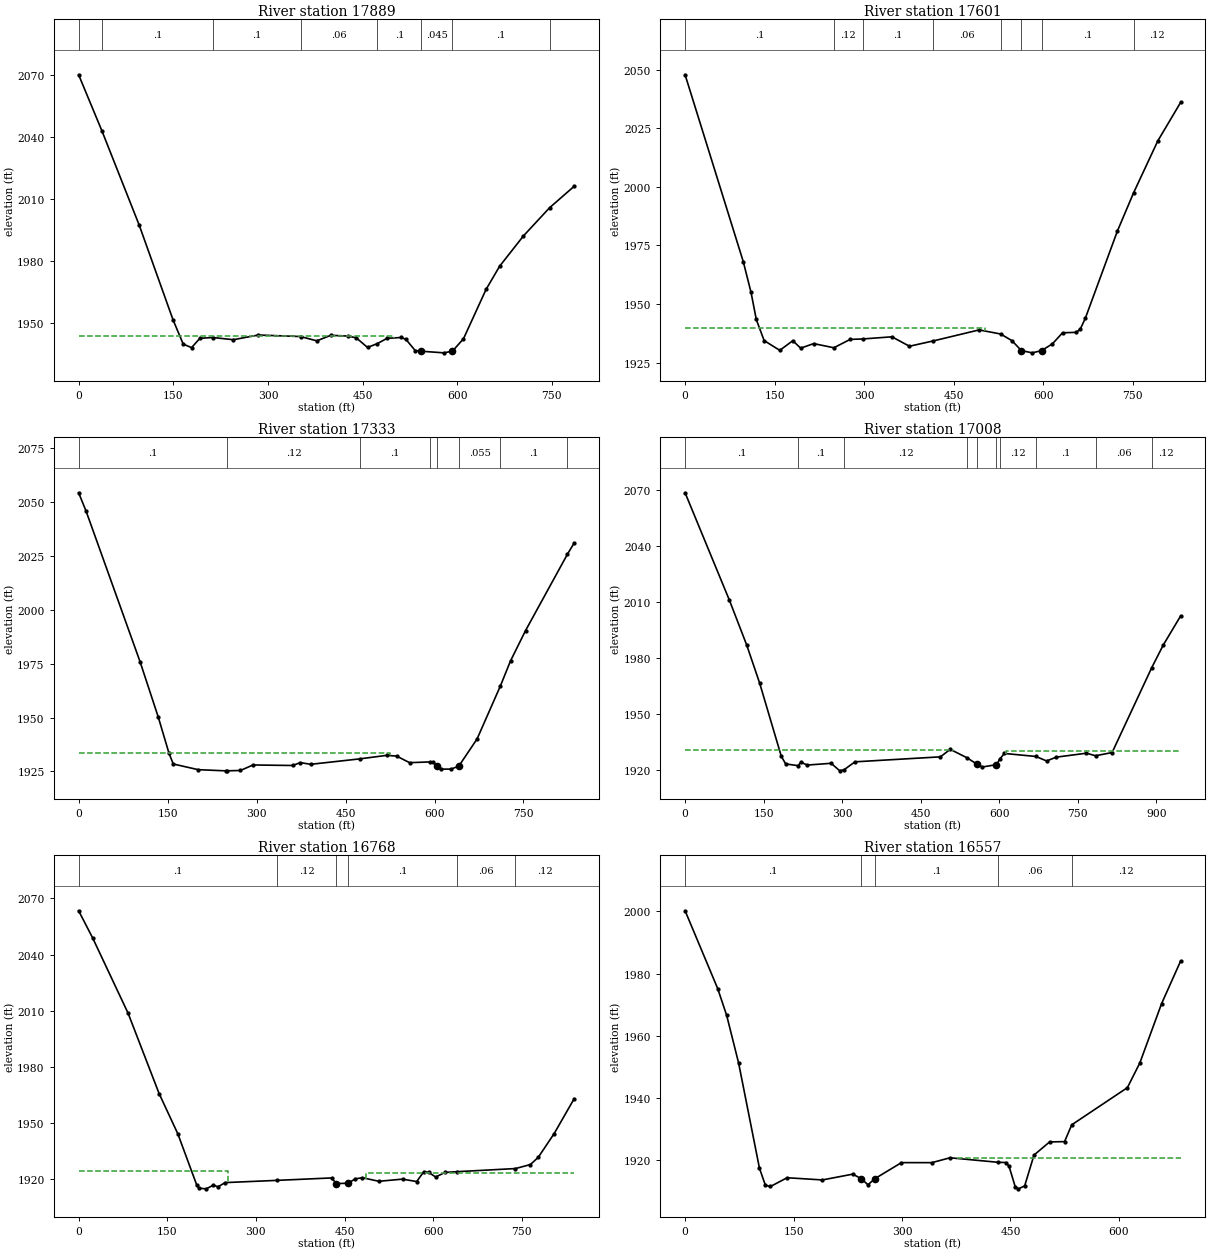
Type RM Length L Ch R = 1 ,17889   ,294,288.6,285.5
XS GIS Cut Line= 4
2462708.36622896559642.5145654212463055.76287062559803.626051405
 2463297.4300996559924.4596658942463423.29844802 559964.73753739
#Sta/Elev= 30
       02070.332   37.082042.96595.968411997.342149.67481951.286165.76361939.537
178.99131937.852 192.2191942.379  212.811942.757245.12971941.688284.81281943.969
  351.731943.218377.40661941.143399.68841943.826426.52111943.462439.93761942.608
457.8261 1937.93   473.51939.816488.62511942.343511.49181942.774518.77671941.811
533.34651936.445  543.111936.098578.57381935.314  592.291936.098609.87871942.153
645.65581966.102  667.111977.352704.90831992.097  746.312005.769785.28572016.187
#Mann= 8 ,-1 , 0
       0      .1       0   37.08      .1       0  212.81      .1       0
  351.73     .06       0   473.5      .1       0  543.11    .045       0
  592.29      .1       0  746.31     .12       0
#XS Ineff= 2 , 0
          499.31 1943.62
Permanent Ineff=
       F       F
Bank Sta=543.11,592.29
XS Rating Curve= 0 ,0
Exp/Cntr(USF)=0,0
Exp/Cntr=0.3,0.1

Type RM Length L Ch R = 1 ,17601   ,265.9,267.5,270
XS GIS Cut Line= 4
2462597.60208235559939.5638677052462975.20712763560105.710087626
2463221.90909054560191.3005645562463372.95110865560231.578436052
#Sta/Elev= 30
       02047.78997.390461968.153110.5007 1954.96119.24091943.458132.35111934.464
158.5716  1930.3 180.4221934.406193.53221931.225215.38261933.174  249.151931.397
 276.425 1934.96   297.41935.154 346.4851936.069 375.7451932.043  415.621934.313
 492.4961939.009  528.461937.268547.53661934.415  563.191930.187581.40781929.233
  597.061930.185615.27891933.079632.21451937.785655.14351937.972661.85171939.335
670.31951943.953724.21111981.257  751.291997.528791.67382019.568829.98882036.005
#Mann= 8 ,-1 , 0
       0      .1       0  249.15     .12       0   297.4      .1       0
  415.62     .06       0  528.46      .1       0  563.19    .045       0
  597.06      .1       0  751.29     .12       0
#XS Ineff= 2 , 0
          502.06 1939.63
Permanent Ineff=
       F       F
Bank Sta=563.19,597.06
XS Rating Curve= 0 ,0
Exp/Cntr(USF)=0,0
Exp/Cntr=0.3,0.1

Type RM Length L Ch R = 1 ,17333   ,322.2,325.3,328.5
XS GIS Cut Line= 4
2462466.69899999560211.4395003042462909.75558645 560352.41205054
2463136.31861361560453.1067292812463252.11749416560493.384600777
#Sta/Elev= 30
       02054.42212.641112045.838103.73021975.815134.37151950.149152.45041933.354
159.55711928.444201.5331 1925.81247.70661925.266  250.681925.283272.89221925.432
293.88021927.992361.04181927.749373.63461929.095391.27931928.298  473.891930.823
519.08811932.447536.06261932.131557.94891929.059  592.541929.413597.34431929.489
603.9398 1927.37610.47611926.069628.18321926.067 641.1171927.515671.7579 1940.07
   711.21964.769728.1495 1976.33753.55991990.451  824.172025.909835.47912031.104
#Mann= 8 ,-1 , 0
       0      .1       0  250.68     .12       0  473.89      .1       0
  592.54    .055       0603.9398    .045       0 641.117    .055       0
   711.2      .1       0  824.17     .12       0
#XS Ineff= 2 , 0
          525.38 1933.69
Permanent Ineff=
       F       F
Bank Sta=603.9398,641.117
XS Rating Curve= 0 ,0
Exp/Cntr(USF)=0,0
Exp/Cntr=0.3,0.1

Type RM Length L Ch R = 1 ,17008   ,247.5,239.4,229.1
XS GIS Cut Line= 4
2462360.96958731560518.5582704622462783.88723802560629.322417076
2463020.51973306 560775.329701252463247.08276023560820.642306683
#Sta/Elev= 30
       02068.33884.533592010.884117.61291986.859142.42241966.392183.77151927.214
192.0413  1923.2  215.561922.264221.26731924.065233.39051922.581278.87451923.526
295.41421919.488  303.861920.113324.35861924.308487.54151926.982506.34211930.982
  538.681926.429558.04381922.929567.44411921.536594.45211922.781  601.421925.977
609.74551928.794  670.051927.177690.37231924.767708.44871926.806766.45421928.927
  783.811927.565815.40471929.281  890.851974.589913.30591986.944946.28412002.406
#Mann= 10 ,-1 , 0
       0      .1       0  215.56      .1       0  303.86     .12       0
  538.68      .1       0558.0438    .045       0594.4521      .1       0
  601.42     .12       0  670.05      .1       0  783.81     .06       0
  890.85     .12       0
#XS Ineff= 2 , 0
          511.66 1930.55  613.17         1930.22
Permanent Ineff=
       F       F
Bank Sta=558.0438,594.4521
XS Rating Curve= 0 ,0
Exp/Cntr(USF)=0,0
Exp/Cntr=0.3,0.1

Type RM Length L Ch R = 1 ,16768   ,215.1,211.6,204.7
XS GIS Cut Line= 4
2462371.03905518560901.1980496752462708.36622896560916.302251486
2463020.51973306 560926.371719362463206.80488873560896.163315738
#Sta/Elev= 30
       02063.40423.729742048.90583.789862008.661136.24391965.795 167.8741944.355
199.90611917.002203.91011915.295215.92211914.969227.93411916.921235.94221916.053
247.95421918.298  336.221919.498 428.0911920.792436.0952 1917.79456.10551917.957
468.11181920.268 480.1181920.922508.13261918.997548.15341920.153572.16591918.852
584.17211924.114592.17631923.801604.18261921.281620.19091923.734  639.811924.116
  739.311925.796764.54031927.928777.85521931.758804.88841944.501838.69961963.093
#Mann= 6 ,-1 , 0
       0      .1       0  336.22     .12       0436.0952    .045       0
456.1055      .1       0  639.81     .06       0  739.31     .12       0
#XS Ineff= 2 , 0
           252.4 1924.24  486.97         1923.25
Permanent Ineff=
       F       F
Bank Sta=436.0952,456.1055
XS Rating Curve= 0 ,0
Exp/Cntr(USF)=0,0
Exp/Cntr=0.3,0.1

Type RM Length L Ch R = 1 ,16557   ,299.6,290.4,282.6
XS GIS Cut Line= 4
2462619.06998647561190.764881424 2462782.5827888 561149.14344083
2462975.82519156561086.7112799382463267.17527573560970.765838281
#Sta/Elev= 30
       02000.16745.067781975.19857.450441966.61773.960651951.334102.85351917.497
111.1086 1911.99118.07191911.631141.10251914.444189.91531913.734231.95111915.599
243.71881914.113 252.9691912.171   262.11914.086299.20831919.292341.24411919.287
366.46561920.852  433.051919.396443.82861919.329448.13361918.069456.74391911.435
 461.0491910.877469.65921911.828482.57451921.722   504.11925.938524.81271926.042
  534.78 1931.44611.72771943.368628.94811951.303659.08391970.382685.37761984.035
#Mann= 5 ,-1 , 0
       0      .1       0243.7188    .045       0   262.1      .1       0
  433.05     .06       0  534.78     .12       0
#XS Ineff= 2 , 0
                          375.45         1920.81
Permanent Ineff=
       F       F
Bank Sta=243.7188,262.1
XS Rating Curve= 0 ,0
Exp/Cntr(USF)=0,0
Exp/Cntr=0.3,0.1

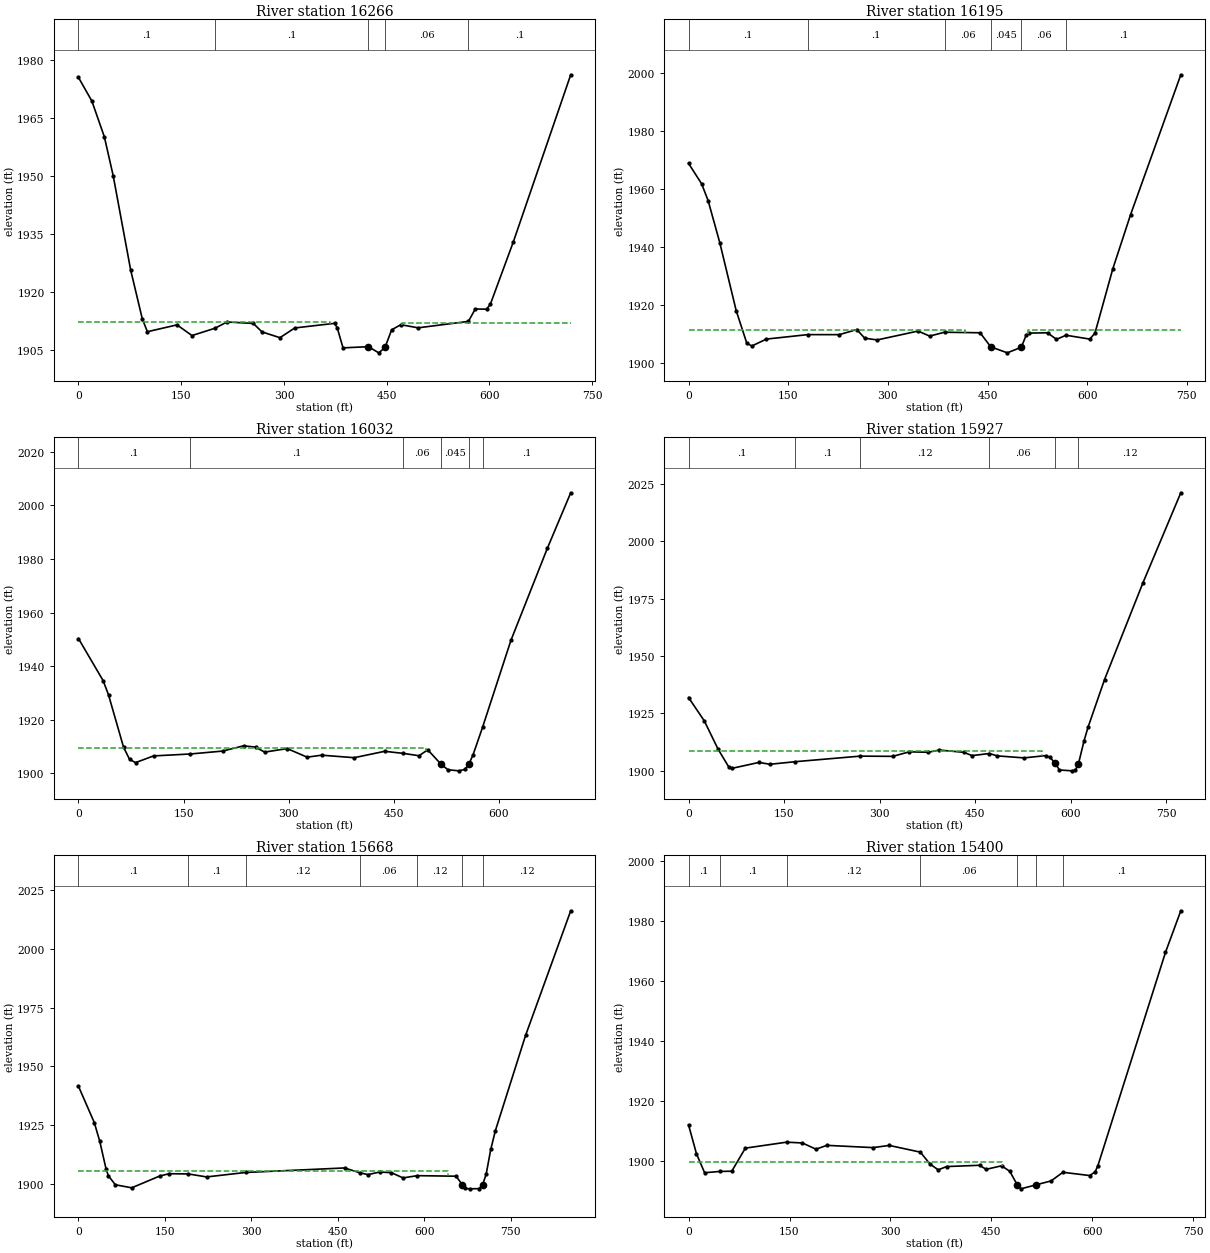
Type RM Length L Ch R = 1 ,16266   ,87,71.5,62.6
XS GIS Cut Line= 4
2462711.23174778561544.5471264782462969.87927148561449.412405119
2463103.66247339561279.9536826982463267.17527573561122.386800447
#Sta/Elev= 30
       01975.57619.606531969.44537.839391960.17850.625381950.20576.197361925.766
93.245351913.079100.62031909.808143.84551911.578165.69931908.812  199.271910.707
216.84331912.322255.20121911.951267.9872 1909.75294.09031908.261315.71781910.781
373.81571911.971377.67811910.846386.22191905.631423.24511905.938438.36891904.344
  447.481905.733 457.172  1910.3470.64541911.619495.77291910.814  569.191912.475
579.29111915.694 595.7621915.625 601.3171916.944634.64671932.967718.56851976.258
#Mann= 5 ,-1 , 0
       0      .1       0  199.27      .1       0423.2451    .045       0
  447.48     .06       0  569.19      .1       0
#XS Ineff= 2 , 0
          366.53  1912.4  472.98          1912.1
Permanent Ineff=
       F       F
Bank Sta=423.2451,447.48
XS Rating Curve= 0 ,0
Exp/Cntr(USF)=0,0
Exp/Cntr=0.5,0.3

Type RM Length L Ch R = 1 ,16195   ,143.3,163.1,179.1
XS GIS Cut Line= 4
2462743.93430825 561606.979287372463112.58135352561440.493524992
 2463139.3379939561315.6292032082463326.63447658561223.467441891
#Sta/Elev= 30
       01968.88919.651781961.84329.40318 1956.0746.97401 1941.5471.732581918.005
87.681191906.78795.25294 1905.82117.19791908.209  179.53 1909.75226.92281909.739
253.14431911.492265.23841908.507283.97971907.913345.4256 1910.97362.98161909.239
  385.261910.573438.86291910.388454.83411905.538479.77091903.456  500.86 1905.39
508.40661909.655512.4974 1910.27540.45151910.375553.82561908.101  568.111909.539
604.01281908.199  611.781910.293638.52821932.423665.27641951.143740.93961999.493
#Mann= 6 ,-1 , 0
       0      .1       0  179.53      .1       0  385.26     .06       0
454.8341    .045       0  500.86     .06       0  568.11      .1       0
#XS Ineff= 2 , 0
          415.91 1911.44  511.39         1911.25
Permanent Ineff=
       F       F
Bank Sta=454.8341,500.86
XS Rating Curve= 0 ,0
Exp/Cntr(USF)=0,0
Exp/Cntr=0.5,0.3

Type RM Length L Ch R = 1 ,16032   ,103.5,104.5,105.7
XS GIS Cut Line= 4
2462770.69094863561663.4655281772463213.66199496561494.006805756
2463305.82375628561419.682804695 2463397.9855176561360.223603845
#Sta/Elev= 30
       01950.32335.19371 1934.6242.884911929.30764.298411909.80672.863811905.278
81.42921 1904.03107.12541906.535  159.291907.252205.6275 1908.34235.60641910.313
252.73721909.813265.58531907.957297.86431909.268 326.2671906.068346.9566 1906.81
393.43781905.875436.89331908.255  463.591907.476485.94671906.604498.35741908.811
517.08871903.517527.0559 1901.39542.47191900.969551.22411901.479556.91331903.386
563.02661906.966  576.541917.202 617.0621949.664669.14451984.087702.35262004.711
#Mann= 6 ,-1 , 0
       0      .1       0  159.29      .1       0  463.59     .06       0
517.0887    .045       0556.9133     .06       0  576.54      .1       0
#XS Ineff= 2 , 0
          496.02 1909.52
Permanent Ineff=
       F       F
Bank Sta=517.0887,556.9133
XS Rating Curve= 0 ,0
Exp/Cntr(USF)=0,0
Exp/Cntr=0.5,0.3

Type RM Length L Ch R = 1 ,15927   ,246.4,259.3,272.5
XS GIS Cut Line= 4
2462779.60982876561770.4920897062463264.20231568 561583.19560703
2463389.06663747561491.0338457142463469.33655861561434.547604907
#Sta/Elev= 30
       01931.92724.803111921.70946.244981909.47363.398481901.53567.686851901.025
110.57061903.639127.72411902.833  167.911903.967  269.421906.381320.70091906.282
346.4312 1908.25376.44981908.063393.60331909.036432.03491908.047445.0638 1906.61
  472.431907.524484.6149 1906.49526.7773 1905.61560.4557  1906.6 567.4331905.887
575.9115 1903.18582.34771900.344 602.2341899.969607.37541900.299612.17721903.049
621.07681913.149627.09191918.866653.14111939.769713.35031981.868772.8743 2021.17
#Mann= 6 ,-1 , 0
       0      .1       0  167.91      .1       0  269.42     .12       0
  472.43     .06       0575.9115    .045       0612.1772     .12       0
#XS Ineff= 2 , 0
          555.28 1908.63
Permanent Ineff=
       F       F
Bank Sta=575.9115,612.1772
XS Rating Curve= 0 ,0
Exp/Cntr(USF)=0,0
Exp/Cntr=0.3,0.1

Type RM Length L Ch R = 1 ,15668   ,261.9,267.7,276
XS GIS Cut Line= 4
2462767.71798859561862.6538510222463311.76967636561767.519129663
2463502.03911908561755.6272894932463612.03864065561737.789529239
#Sta/Elev= 30
       01941.50327.437151926.06736.973921918.05447.740621906.48751.801311903.458
63.983391899.57992.408251898.281141.13661903.313157.37931904.282   190.81904.182
222.35041902.915  290.121904.812461.93141906.735  488.77 1904.65502.53831903.897
522.84181905.005543.14531904.716563.30361902.502  588.271903.457655.48321903.222
  665.96 1899.66671.51431897.994  679.531897.844695.5612 1897.94  701.52 1899.66
707.5846 1904.02715.60021914.635723.61581922.594776.08071963.187 854.3842016.194
#Mann= 7 ,-1 , 0
       0      .1       0   190.8      .1       0  290.12     .12       0
  488.77     .06       0  588.27     .12       0  665.96    .045       0
  701.52     .12       0
#XS Ineff= 2 , 0
           640.6 1905.31
Permanent Ineff=
       F       F
Bank Sta=665.96,701.52
XS Rating Curve= 0 ,0
Exp/Cntr(USF)=0,0
Exp/Cntr=0.3,0.1

Type RM Length L Ch R = 1 ,15400   ,222.4,210.5,203.4
XS GIS Cut Line= 4
2462839.06902961562020.2207332732463198.79719475561972.653372594
2463448.52583832562026.1666533582463561.49831993562020.220733273
#Sta/Elev= 30
       01912.00411.777651902.347 23.88211896.034   46.271896.46664.230291896.551
84.404381904.248  145.631906.238169.13561905.974189.3097 1903.89205.44891905.175
274.04091904.425298.24981905.149  344.351902.913358.77211898.938370.98781896.994
383.26021898.094432.34991898.526442.1847 1897.17465.0763 1898.35477.34871896.508
  488.271892.018493.7119 1890.66  516.751892.016538.71081893.311  556.211896.185
595.98211895.096604.16371896.313608.25451898.443708.60141969.592731.38621983.484
#Mann= 7 ,-1 , 0
       0      .1       0   46.27      .1       0  145.63     .12       0
  344.35     .06       0  488.27    .045       0  516.75     .06       0
  556.21      .1       0
#XS Ineff= 2 , 0
          466.39 1899.48
Permanent Ineff=
       F       F
Bank Sta=488.27,516.75
XS Rating Curve= 0 ,0
Exp/Cntr(USF)=0,0
Exp/Cntr=0.3,0.1

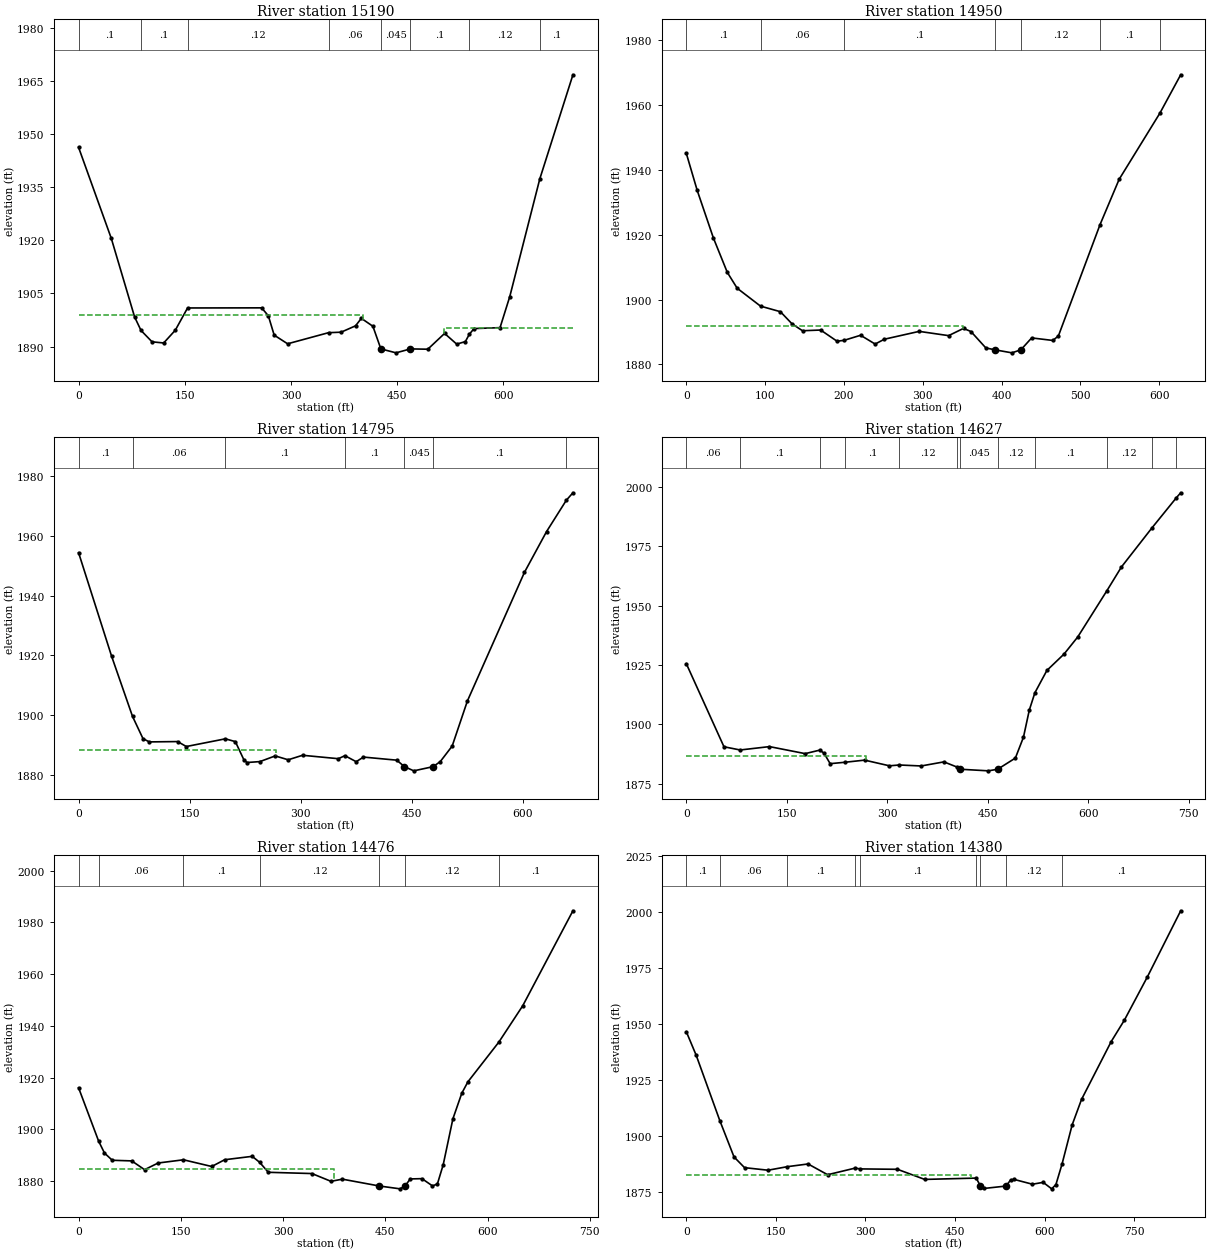
Type RM Length L Ch R = 1 ,15190   ,252.1,239.5,233.5
XS GIS Cut Line= 4
2462877.71751016562308.5978573932463246.36455543562222.382016161
2463466.36359857562177.7876155242463558.52535989562154.003935185
#Sta/Elev= 30
       01946.24746.242541920.52579.106021898.363    88.21894.535103.75361891.328
120.18541890.997136.61711894.599  153.941900.886258.63261900.918 268.0711898.656
276.2869 1893.21 295.2551890.768  353.051893.905370.76941894.043391.22681895.844
399.38951897.953415.71491895.717  426.971889.323448.36571888.213468.77241889.327
493.26051889.237516.97571893.693 534.0741890.678546.31811891.389  551.871893.437
558.56211895.067595.29431895.327609.0425  1904.1  651.441937.336 698.2491966.743
#Mann= 8 ,-1 , 0
       0      .1       0    88.2      .1       0  153.94     .12       0
  353.05     .06       0  426.97    .045       0468.7724      .1       0
  551.87     .12       0  651.44      .1       0
#XS Ineff= 2 , 0
          402.33 1898.82  515.64         1895.13
Permanent Ineff=
       F       F
Bank Sta=426.97,468.7724
XS Rating Curve= 0 ,0
Exp/Cntr(USF)=0,0
Exp/Cntr=0.3,0.1

Type RM Length L Ch R = 1 ,14950   ,163.7,155,145.2
XS GIS Cut Line= 4
2463094.74359326 562617.785701812463344.47223683562475.083619771
2463528.79575946562359.1381781152463612.03864065562269.949376841
#Sta/Elev= 30
       01945.06113.822681933.639 34.37181918.97251.962181908.39464.499731903.499
   94.131897.978 119.3921896.256134.05061892.535147.42581890.387170.46081890.604
191.26661887.155  200.19 1887.43221.13791888.991239.59291886.283251.31981887.774
295.49971890.191332.84031888.877351.74261891.111361.19371890.145380.09591885.088
  391.581884.508413.17481883.573  424.531884.507438.23581888.175 465.1561887.393
472.16611888.784  525.071923.145549.2766 1937.09  600.891957.451627.38321969.324
#Mann= 7 ,-1 , 0
       0      .1       0   94.13     .06       0  200.19      .1       0
  391.58    .045       0  424.53     .12       0  525.07      .1       0
  600.89     .12       0
#XS Ineff= 2 , 0
          350.48 1891.81
Permanent Ineff=
       F       F
Bank Sta=391.58,424.53
XS Rating Curve= 0 ,0
Exp/Cntr(USF)=0,0
Exp/Cntr=0.3,0.1

Type RM Length L Ch R = 1 ,14795   ,181.1,168.4,165.7
XS GIS Cut Line= 4
2463267.17527573 562870.487305422463451.49879836562674.271942617
2463597.17384044562460.2188195592463644.74120112 562329.40857769
#Sta/Elev= 30
       01954.43444.68705 1919.66   72.821899.56887.004381892.08495.623591891.018
133.74191891.129145.42621889.469  198.141892.049211.64571891.114 222.9651885.115
227.21681884.109244.74331884.415 265.412 1886.32282.97961885.023302.33341886.536
350.71781885.388  359.491886.406374.75061884.385384.5869 1885.93429.45291884.898
   439.91882.729452.4855 1881.32   478.71882.728488.26911884.424504.30881889.617
524.9016 1904.76601.90311947.862631.69681961.498  658.461972.027667.32421974.512
#Mann= 7 ,-1 , 0
       0      .1       0   72.82     .06       0  198.14      .1       0
  359.49      .1       0   439.9    .045       0   478.7      .1       0
  658.46     .12       0
#XS Ineff= 2 , 0
          265.98  1888.3
Permanent Ineff=
       F       F
Bank Sta=439.9,478.7
XS Rating Curve= 0 ,0
Exp/Cntr(USF)=0,0
Exp/Cntr=0.3,0.1

Type RM Length L Ch R = 1 ,14627   ,132.1,151.1,160.9
XS GIS Cut Line= 4
2463371.22887721562950.7572265662463656.63304129562689.136742829
2463725.01112227562534.5428206212463760.68664278562356.165218072
#Sta/Elev= 30
       01925.54256.184941890.527   80.351889.174124.13131890.595177.38931887.637
  199.181889.107 205.5421887.837214.72651883.399  237.631884.019266.18291884.895
 303.2151882.499  318.011882.846350.61931882.431384.57431884.157  404.511881.931
  409.211881.051450.85931880.378  464.821881.049491.27751885.763 503.3451894.554
512.09261906.014  520.391913.295538.33541922.718564.01471929.646584.4108 1936.84
  627.981956.363649.67821966.374  694.831982.701  731.851995.619738.12141997.644
#Mann= 12 ,-1 , 0
       0     .06       0   80.35      .1       0  199.18      .1       0
  237.63      .1       0  318.01     .12       0  404.51      .1       0
  409.21    .045       0  464.82     .12       0  520.39      .1       0
  627.98     .12       0  694.83      .1       0  731.85     .12       0
#XS Ineff= 2 , 0
          268.86 1886.64
Permanent Ineff=
       F       F
Bank Sta=409.21,464.82
XS Rating Curve= 0 ,0
Exp/Cntr(USF)=0,0
Exp/Cntr=0.3,0.1

Type RM Length L Ch R = 1 ,14476   ,96.6,96.4,93.2
XS GIS Cut Line= 4
2463412.85031781563022.1082675862463719.06520218562796.163304358
2463843.92952397562695.0826629142463959.87496562562552.380580875
#Sta/Elev= 30
       01916.097   29.411895.49337.980771890.88549.42246 1888.0978.026691887.847
96.804161884.455116.68831887.032  153.841888.276 195.3041885.686214.26741888.297
254.68971889.609  265.52 1887.31278.25631883.444342.2713 1882.96370.21061879.956
386.91571880.791  441.281878.147 471.5751877.055  478.821878.147486.4576 1880.88
503.6518 1880.99519.09091878.188526.27441878.936534.80651886.364549.02531904.108
 562.0631913.984571.03831918.397  616.491933.763 651.392 1947.75725.06781984.462
#Mann= 7 ,-1 , 0
       0      .1       0   29.41     .06       0  153.84      .1       0
  265.52     .12       0  441.28    .045       0  478.82     .12       0
  616.49      .1       0
#XS Ineff= 2 , 0
          375.31  1884.8
Permanent Ineff=
       F       F
Bank Sta=441.28,478.82
XS Rating Curve= 0 ,0
Exp/Cntr(USF)=0,0
Exp/Cntr=0.3,0.1

Type RM Length L Ch R = 1 ,14380   ,149.7,132.6,116.6
XS GIS Cut Line= 4
2463421.76919794563149.9455494122463754.74072269562891.298025717
 2463930.1453652562736.7041035092464055.00968698 562617.78570181
#Sta/Elev= 30
       01946.342 16.43071935.899      561906.71479.840221890.45297.470871885.661
136.85341884.521  169.151886.101203.83611887.313236.62651882.506   282.31885.442
  291.381885.102353.50351884.928399.11411880.414  485.461881.004   492.51877.452
498.43691876.375535.27951877.443543.23381880.223549.28341880.382579.53141878.267
597.58291879.093611.79871876.203618.91031878.112  629.171887.288 646.0771904.748
661.78581916.126711.50011941.974733.5308 1951.53 772.2621970.958827.86552000.381
#Mann= 9 ,-1 , 0
       0      .1       0      56     .06       0  169.15      .1       0
   282.3     .12       0  291.38      .1       0  485.46     .12       0
   492.5    .045       0535.2795     .12       0  629.17      .1       0
#XS Ineff= 2 , 0
          475.99 1882.44
Permanent Ineff=
       F       F
Bank Sta=492.5,535.2795
XS Rating Curve= 0 ,0
Exp/Cntr(USF)=0,0
Exp/Cntr=0.5,0.3

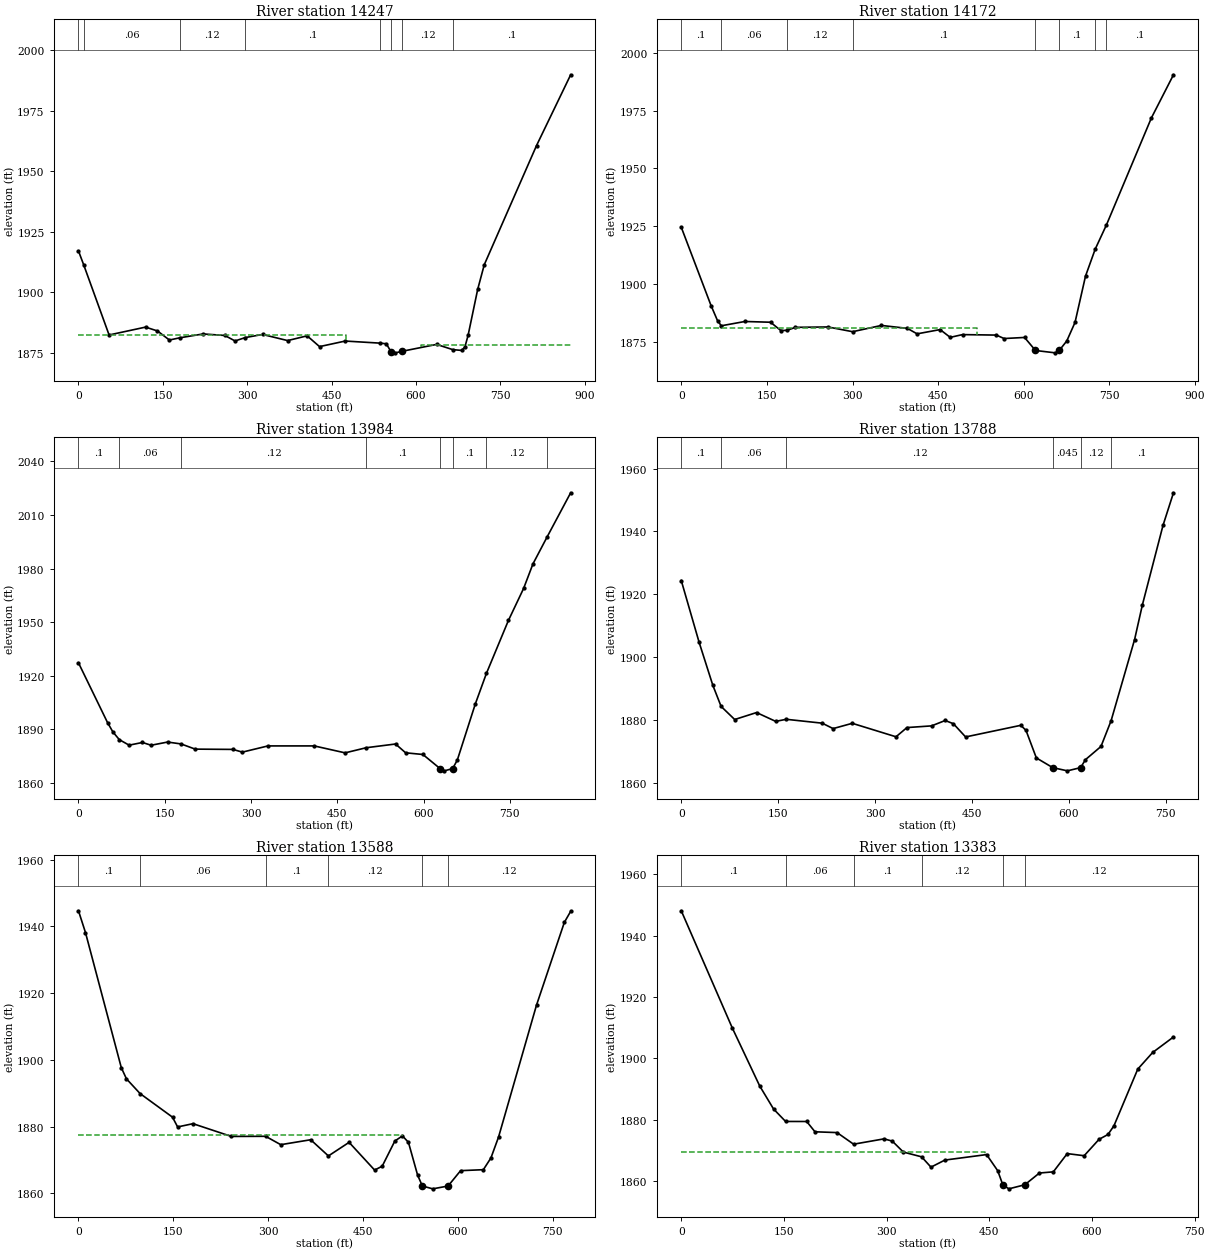
Type RM Length L Ch R = 1 ,14247   ,68.8,74.4,81.6
XS GIS Cut Line= 4
2463540.68759963563289.6746714082463927.17240516562953.730186609
2463903.38872482 562822.919944742464081.76632736562677.244902659
#Sta/Elev= 30
       01917.108     9.51911.22754.467761882.379 119.3241885.629140.52361884.039
161.72321880.292  179.721881.188221.75281882.802260.32731882.174278.45961879.905
  296.571881.306327.39691882.594372.0258 1880.06406.66091882.029428.7327 1877.57
474.41761879.871  537.081878.997547.49371878.745555.62481875.546 563.756    1875
575.95281875.664636.93641878.482  665.811876.317681.55751876.004687.24311877.417
692.92871882.237709.98551901.234721.67311911.393814.63241960.629875.34171989.864
#Mann= 8 ,-1 , 0
       0      .1       0     9.5     .06       0  179.72     .12       0
  296.57      .1       0  537.08     .12       0555.6248    .045       0
575.9528     .12       0  665.81      .1       0
#XS Ineff= 2 , 0
          475.99 1882.21     610         1878.39
Permanent Ineff=
       F       F
Bank Sta=555.6248,575.9528
XS Rating Curve= 0 ,0
Exp/Cntr(USF)=0,0
Exp/Cntr=0.5,0.3

Type RM Length L Ch R = 1 ,14172   ,174.1,188.1,217.7
XS GIS Cut Line= 4
2463540.68759963563334.2690720452463977.71272588562974.540906906
2463998.52344617562852.6495451652464117.44184787562727.785223381
#Sta/Elev= 30
       01924.61852.170631890.79563.537461884.251   70.141882.065111.46161883.915
156.37231883.593 174.3641880.009  185.111880.089199.9394 1881.39257.07671881.549
  300.081879.507350.5498 1882.21396.01711880.945413.06741878.577453.3942 1880.42
471.07361877.063492.6351 1878.25551.82941878.042565.48411876.557 601.2871877.019
  620.391871.396654.95311870.376  662.031871.396675.24241875.506689.68991883.515
708.06621903.518  725.031915.155  744.761925.646823.41121971.814862.12151990.463
#Mann= 8 ,-1 , 0
       0      .1       0   70.14     .06       0  185.11     .12       0
  300.08      .1       0  620.39    .045       0  662.03      .1       0
  725.03     .12       0  744.76      .1       0
#XS Ineff= 2 , 0
          517.15 1880.92
Permanent Ineff=
       F       F
Bank Sta=620.39,662.03
XS Rating Curve= 0 ,0
Exp/Cntr(USF)=0,0
Exp/Cntr=0.5,0.3

Type RM Length L Ch R = 1 ,13984   ,189.3,196.2,204.1
XS GIS Cut Line= 4
2463543.66055968563384.8093927672463995.55048613563108.324108818
2464162.03624851563025.0812276292464283.92761025562956.703146652
#Sta/Elev= 30
       01927.233 50.50911893.77559.88772 1888.51   71.031884.21388.023571881.126
111.28231882.629126.30391881.073154.92161882.865  178.341881.812202.94641878.906
268.38371878.745284.97451877.228329.4787  1880.7 409.8811880.699463.53081876.815
  500.261879.689 551.2231881.777568.74471876.848598.8035  1875.9  628.641868.006
636.19351866.747  650.421868.005658.55421872.743689.85921904.176  709.261921.372
747.41071950.939773.85421968.888790.09471982.618   814.91997.837855.66032022.439
#Mann= 8 ,-1 , 0
       0      .1       0   71.03     .06       0  178.34     .12       0
  500.26      .1       0  628.64    .045       0  650.42      .1       0
  709.26     .12       0   814.9      .1       0
Bank Sta=628.64,650.42
XS Rating Curve= 0 ,0
Exp/Cntr(USF)=0,0
Exp/Cntr=0.3,0.1

Type RM Length L Ch R = 1 ,13788   ,198,200,199.9
XS GIS Cut Line= 4
 2463552.5794398563408.5930731072464025.28008656563245.080270771
2464197.71176902563239.1343506862464286.90057029563242.107310729
#Sta/Elev= 30
       01924.389 27.68681904.72848.849561891.104   61.661884.39182.709951880.219
116.57041882.434146.19821879.626  162.471880.287218.15161879.056235.08181877.335
264.70961879.012332.43041874.728349.3606 1877.66387.45361878.195408.61631879.908
 421.3141878.875440.16041874.679525.66241878.376533.66721876.763549.67661868.011
  575.071864.925597.70521863.906  618.191864.924625.7218 1867.46649.73611871.655
  665.371879.816701.76591905.636713.77251916.606745.79031941.937761.95481952.286
#Mann= 6 ,-1 , 0
       0      .1       0   61.66     .06       0  162.47     .12       0
  575.07    .045       0  618.19     .12       0  665.37      .1       0
Bank Sta=575.07,618.19
XS Rating Curve= 0 ,0
Exp/Cntr(USF)=0,0
Exp/Cntr=0.3,0.1

Type RM Length L Ch R = 1 ,13588   ,206.8,204.9,200.1
XS GIS Cut Line= 4
2463531.76871951563509.673714551  2463986.631606563438.322673532
2464185.81992885563435.3497134892464304.73833055563429.403793404
#Sta/Elev= 30
       01944.66111.110541938.12967.795321897.63975.89314 1894.31   97.47 1889.89
148.7736 1882.82156.8714 1879.89181.16491880.867241.89861877.045   296.11877.085
320.03081874.576367.41491876.055  395.421871.204428.14861875.274468.53941866.964
480.54071868.134500.54291875.674512.54431877.206 522.0331875.289536.54691865.454
  544.071862.189560.54961861.344  584.731862.188604.55451866.791640.55851867.082
652.55991870.607664.56681876.842724.64181916.384768.69671941.193778.70251944.491
#Mann= 6 ,-1 , 0
       0      .1       0   97.47     .06       0   296.1      .1       0
  395.42     .12       0  544.07    .045       0  584.73     .12       0
#XS Ineff= 2 , 0
          511.39 1877.34
Permanent Ineff=
       F       F
Bank Sta=544.07,584.73
XS Rating Curve= 0 ,0
Exp/Cntr(USF)=0,0
Exp/Cntr=0.3,0.1

Type RM Length L Ch R = 1 ,13383   ,314.3,318.6,321.8
XS GIS Cut Line= 4
2463609.06568061563708.8620373972463968.79384575563661.294676717
2464185.81992885563622.6461961652464310.68425063  563569.1329154
#Sta/Elev= 30
       01948.07374.524231909.947114.66891891.019 134.8431883.547  152.431879.498
183.26081879.484195.36531876.133227.64381875.871  251.791872.093296.2357 1873.83
308.34021873.099324.47951869.531  351.151867.982364.84141864.622 385.1561866.926
   446.11868.714462.35171863.463  469.791858.884478.60351857.563  501.941858.886
523.29571862.715543.61041863.093 563.9251869.033588.65841868.342610.41771873.679
623.47331875.255632.17711878.078666.99211896.538688.75141901.946719.14841906.991
#Mann= 6 ,-1 , 0
       0      .1       0  152.43     .06       0  251.79      .1       0
  351.15     .12       0  469.79    .045       0  501.94     .12       0
#XS Ineff= 2 , 0
          443.35 1869.45
Permanent Ineff=
       F       F
Bank Sta=469.79,501.94
XS Rating Curve= 0 ,0
Exp/Cntr(USF)=0,0
Exp/Cntr=0.3,0.1

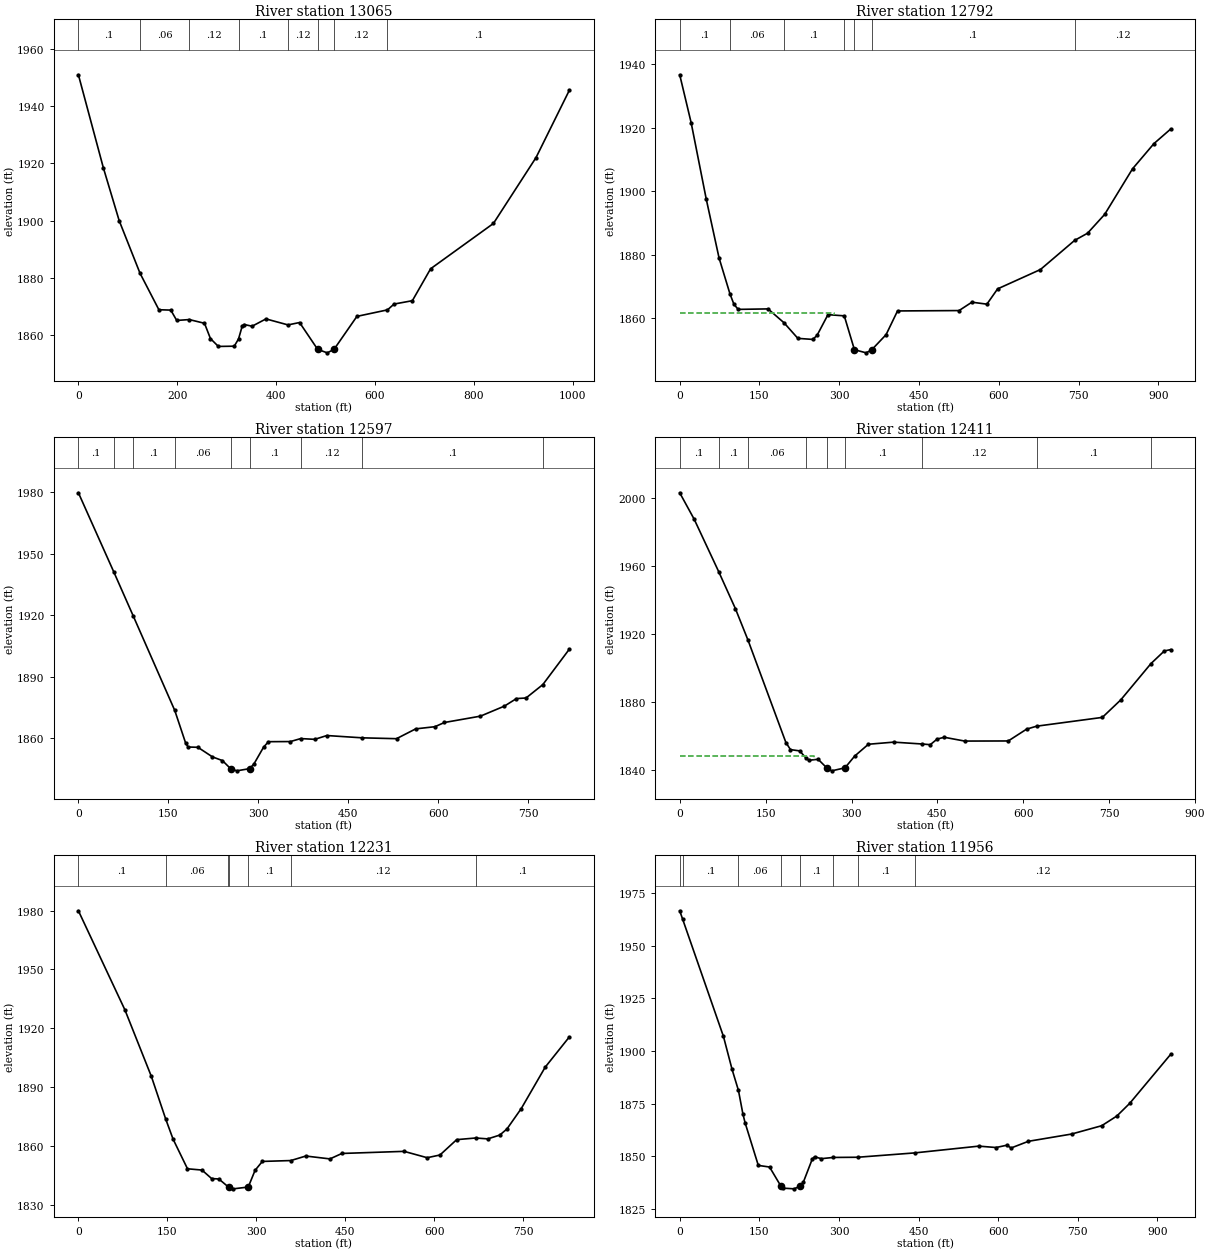
Type RM Length L Ch R = 1 ,13065   ,260.7,272.8,286.3
XS GIS Cut Line= 4
2463680.41672163563973.4554811772464055.00968698563943.725880752
2464346.35977114563943.7258807522464664.46649569563872.374839732
#Sta/Elev= 30
       01951.10750.486571918.482 82.5872 1899.91   124.71881.491162.83881868.706
186.91421868.575 198.9521864.947  224.341865.256255.12811863.954267.16581858.589
283.21611855.834315.31671855.918  323.991858.458 331.3671862.908335.37961863.524
351.42991862.923379.50621865.484  424.111863.382447.50621864.219  484.071854.812
503.50621853.587  517.251854.812563.50621866.374  625.331868.656638.67121870.692
675.71451871.876 712.6091883.068  839.691898.961925.96561922.088993.13151945.609
#Mann= 8 ,-1 , 0
       0      .1       0   124.7     .06       0  224.34     .12       0
  323.99      .1       0  424.11     .12       0  484.07    .045       0
  517.25     .12       0  625.33      .1       0
#XS Ineff= 2 , 0
          381.34 1864.13
Permanent Ineff=
       F       F
Bank Sta=484.07,517.25
XS Rating Curve= 0 ,0
Exp/Cntr(USF)=0,0
Exp/Cntr=0.3,0.1

Type RM Length L Ch R = 1 ,12792   ,204.6,194.7,186.7
XS GIS Cut Line= 4
2463736.90296244  564122.10348332464001.49640622564136.968283512
2464144.19848826564235.0759649142464625.81801514564178.589724107
#Sta/Elev= 30
       01936.74621.459561921.68949.920671897.57873.958511879.082   94.53 1867.73
102.00271864.447110.01531862.858166.10361863.011  196.231858.629222.19191853.731
 250.2361853.398258.24871854.665278.79721861.196  309.491860.821  328.571850.154
350.71021849.172  361.211850.152388.10491854.897409.61511862.367525.32371862.485
549.48831865.124577.68021864.502597.81731869.313678.36561875.406  742.731884.593
766.96881886.844799.18811892.777851.57571907.131891.81871915.068923.10471919.629
#Mann= 7 ,-1 , 0
       0      .1       0   94.53     .06       0  196.23      .1       0
  309.49     .12       0  328.57    .045       0  361.21      .1       0
  742.73     .12       0
#XS Ineff= 2 , 0
          289.44 1861.77
Permanent Ineff=
       F       F
Bank Sta=328.57,361.21
XS Rating Curve= 0 ,0
Exp/Cntr(USF)=0,0
Exp/Cntr=0.3,0.1

Type RM Length L Ch R = 1 ,12597   ,188.5,185.8,182.8
XS GIS Cut Line= 4
2463704.20040197 564327.237726232463861.76728422564333.183646315
2464120.41480792564377.7780469522464518.79145361564371.832126867
#Sta/Elev= 30
       01979.731   59.281940.919   91.211919.758  160.691873.471178.9663 1857.43
183.02531855.617199.26141855.478223.61551850.785240.16361848.995  253.761845.062
264.20571843.985  285.461845.063292.61881847.283308.85491855.562316.97291858.218
353.50411858.278  370.761859.734394.09421859.363414.38931861.219  473.331860.099
530.4853 1859.68562.48881864.475594.49241865.527610.4942 1867.59670.50091870.688
710.50531875.596730.50761879.265746.50931879.547  774.481886.083818.56381903.329
#Mann= 9 ,-1 , 0
       0      .1       0   59.28      .1       0   91.21      .1       0
  160.69     .06       0  253.76    .045       0  285.46      .1       0
  370.76     .12       0  473.33      .1       0  774.48     .12       0
Bank Sta=253.76,285.46
XS Rating Curve= 0 ,0
Exp/Cntr(USF)=0,0
Exp/Cntr=0.3,0.1

Type RM Length L Ch R = 1 ,12411   ,178,180.3,184.3
XS GIS Cut Line= 4
2463677.44376159564538.3178892462463837.98360388564532.371969161
2464191.76584894564544.2638093312464533.65625382564523.453089033
#Sta/Elev= 30
       02002.96925.318631987.395   68.231956.51697.197451934.937  119.22 1916.43
185.42531856.233193.42991852.076209.43891851.323  219.971847.374225.44791845.787
241.65971846.398  256.721841.376265.47051839.602  288.651841.376305.49311848.262
329.50671855.224373.53151856.465  422.421855.393437.56771854.975449.57441858.281
461.97741859.323497.60151857.094573.72031857.156605.77951864.104  623.331865.841
738.02391871.002770.08311881.248  822.961902.633846.22381910.022857.1552 1910.83
#Mann= 9 ,-1 , 0
       0      .1       0   68.23      .1       0  119.22     .06       0
  219.97      .1       0  256.72    .045       0  288.65      .1       0
  422.42     .12       0  623.33      .1       0  822.96     .12       0
#XS Ineff= 2 , 0
          234.57 1848.41
Permanent Ineff=
       F       F
Bank Sta=256.72,288.65
XS Rating Curve= 0 ,0
Exp/Cntr(USF)=0,0
Exp/Cntr=0.3,0.1

Type RM Length L Ch R = 1 ,12231   ,272,274.9,278.5
XS GIS Cut Line= 4
2463677.44376159564669.1281311142463870.68616435564701.830691582
2464090.68520749564743.4521321762464495.00777327564793.992452898
#Sta/Elev= 30
       01979.94678.400381929.362 123.0261895.372  147.111873.681159.53791863.417
183.8791 1848.25208.26281847.601224.54661843.264236.75951843.041  252.411839.073
  253.161838.932261.18521838.015   286.31838.934297.82381847.483310.03671852.004
  358.051852.454383.31391854.761 423.9831853.296444.13871856.073 548.9481857.147
 587.8541853.906 609.4151855.281637.63291863.127  669.79 1863.97690.03751863.511
710.19321865.455722.28661868.545746.47331878.998786.78461900.108827.36071915.496
#Mann= 7 ,-1 , 0
       0      .1       0  147.11     .06       0  252.41      .1       0
  253.16    .045       0   286.3      .1       0  358.05     .12       0
  669.79      .1       0
Bank Sta=253.16,286.3
XS Rating Curve= 0 ,0
Exp/Cntr(USF)=0,0
Exp/Cntr=0.3,0.1

Type RM Length L Ch R = 1 ,11956   ,227.5,225.3,221.4
XS GIS Cut Line= 4
2463653.66008125564924.8026947672463784.47032312564948.586375107
2464004.46936626565025.8833362112464554.46697412565123.991017613
#Sta/Elev= 30
       0 1966.52    5.321962.67782.414311906.89598.676621891.234  110.69 1881.26
119.00451870.188123.07011866.022 148.0851845.702169.28361844.927  190.451835.945
194.72181834.909215.92041834.581  226.681835.946232.87921837.709249.83811848.767
254.07781849.796266.79691848.894  289.141849.476  335.231849.568  442.621851.628
563.48031854.846595.98541854.188616.30111855.281624.42741853.971656.93251857.134
738.19531860.573795.07921864.533823.52121869.116   847.91875.155924.81731898.345
#Mann= 8 ,-1 , 0
       0      .1       0    5.32      .1       0  110.69     .06       0
  190.45    .045       0  226.68      .1       0  289.14     .12       0
  335.23      .1       0  442.62     .12       0
Bank Sta=190.45,226.68
XS Rating Curve= 0 ,0
Exp/Cntr(USF)=0,0
Exp/Cntr=0.3,0.1