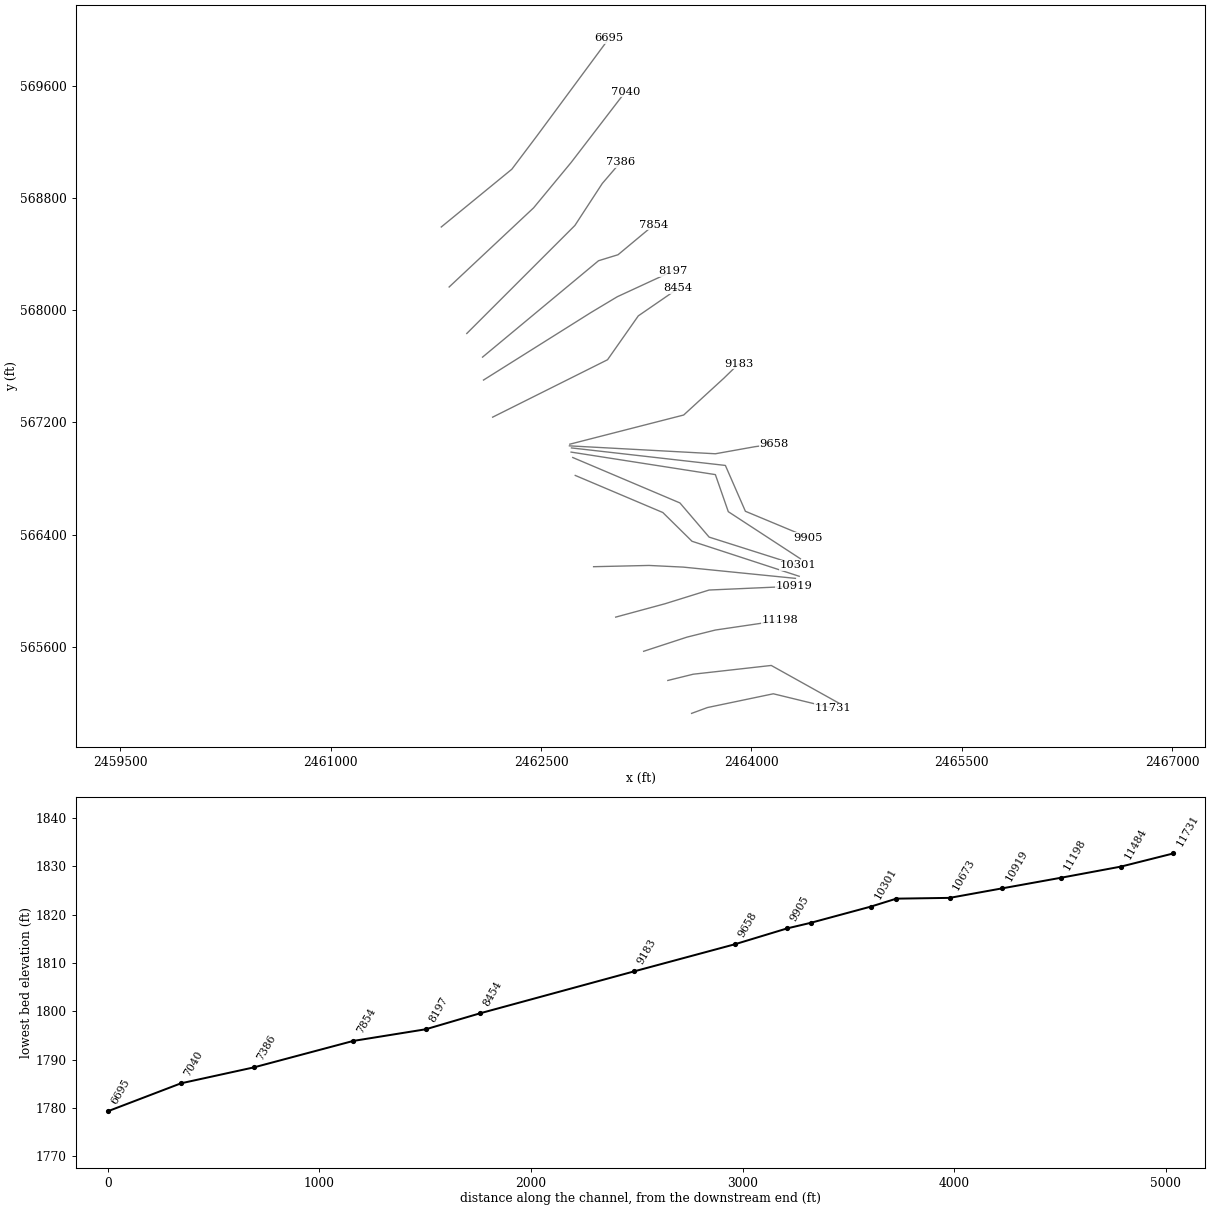
HEC-RAS study LITTLEFK.prj: LITTLEFK

--- LITTLEFK.g01 (geometry) --- (continued)

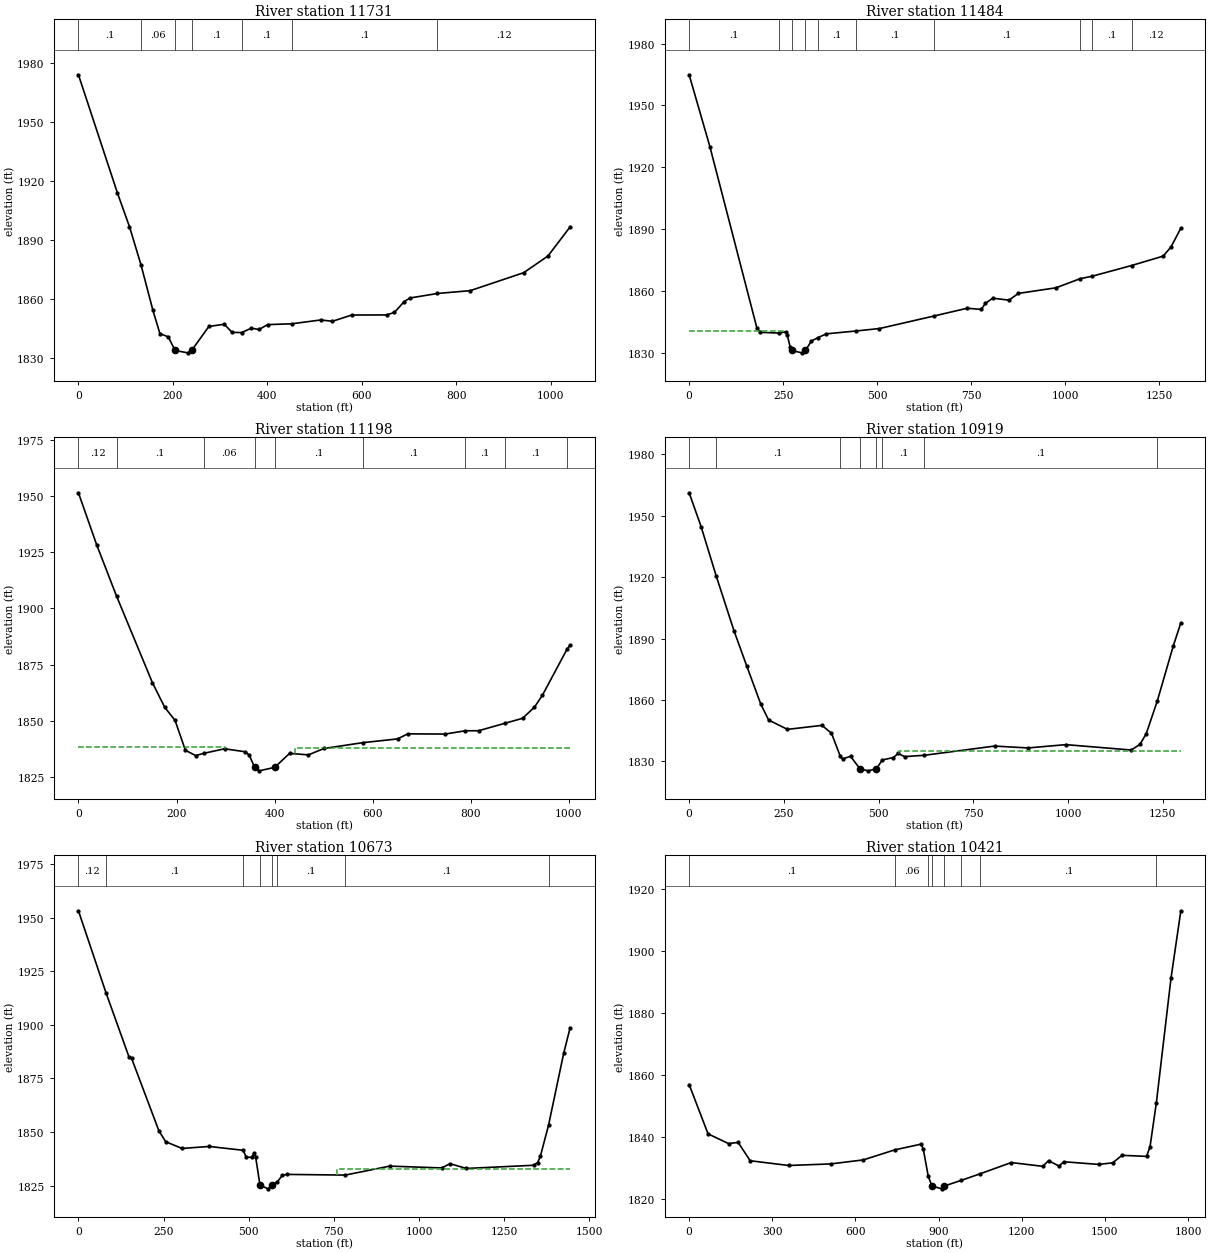
Type RM Length L Ch R = 1 ,11731   ,250.6,246.8,246.1
XS GIS Cut Line= 4
 2463573.3901601565123.9910176132463686.36264172565165.612458207
2464156.09032843565263.7201396092464584.19657454565159.666538122
#Sta/Elev= 30
       01973.90982.437741913.944108.01471896.782  132.471877.327157.56321854.369
172.50381842.423190.25371840.796  204.411833.913231.11681832.677  239.721833.916
276.0663 1846.06308.75681847.209325.10211843.085  345.251842.974365.96521845.185
382.31051844.538400.55561847.017  451.641847.427513.07251849.383537.59041848.688
578.45361851.884652.38891851.927668.85471853.207689.43711858.671701.78641860.533
  759.951862.828829.39651864.261942.49621873.382993.90831881.853 1040.831896.654
#Mann= 7 ,-1 , 0
       0      .1       0  132.47     .06       0  204.41    .045       0
  239.72      .1       0  345.25      .1       0  451.64      .1       0
  759.95     .12       0
Bank Sta=204.41,239.72
XS Rating Curve= 0 ,0
Exp/Cntr(USF)=0,0
Exp/Cntr=0.3,0.1

Type RM Length L Ch R = 1 ,11484   ,280.9,285.9,286.6
XS GIS Cut Line= 4
2463403.93143768565358.8548609682463585.28200027565403.449261605
2464141.22552821565465.8814224972464631.76393522565192.369098589
#Sta/Elev= 30
       01964.86255.254021929.934180.02131842.149188.22531839.921  238.461839.553
256.65271840.131260.67781838.805268.72811832.841  273.091831.096 299.753 1829.96
  309.411831.096325.08431835.656  341.591837.267364.89061839.176  444.711840.578
506.21161841.753  650.961847.815739.66991851.602776.97311851.023787.73051853.907
807.46781856.464850.89651855.515875.53761858.791975.91071861.519 1040.061865.946
 1071.21 1867.09 1176.861872.3321260.8651876.8771281.7041881.3371307.8291890.432
#Mann= 10 ,-1 , 0
       0      .1       0  238.46     .06       0  273.09    .045       0
  309.41     .06       0  341.59      .1       0  444.71      .1       0
  650.96      .1       0 1040.06     .12       0 1071.21      .1       0
 1176.86     .12       0
#XS Ineff= 2 , 0
          255.42 1840.66
Permanent Ineff=
       F       F
Bank Sta=273.09,309.41
XS Rating Curve= 0 ,0
Exp/Cntr(USF)=0,0
Exp/Cntr=0.3,0.1

Type RM Length L Ch R = 1 ,11198   ,277.1,278.5,279.7
XS GIS Cut Line= 4
2463231.49975522 565566.962063942463540.68759963565668.042705385
2463742.84888252565718.5830261062464206.63064915565786.961107083
#Sta/Elev= 30
       01951.57337.080971928.437   77.771905.477150.70591866.994175.95591855.925
196.99761850.116218.03921836.813239.08091834.419  254.991835.405297.99761837.464
339.78141836.135348.02761834.719  359.281829.187368.6431 1827.63  400.091829.187
430.48971835.396 468.974 1834.75500.58251837.594  579.861840.187650.82341841.869
671.27911844.111747.86111844.025  788.241845.477815.75151845.504  869.921848.846
905.54751851.049 929.8071856.021946.12921861.391  996.631882.044 1002.471883.565
#Mann= 9 ,-1 , 0
       0     .12       0   77.77      .1       0  254.99     .06       0
  359.28    .045       0  400.09      .1       0  579.86      .1       0
  788.24      .1       0  869.92      .1       0  996.63      .1       0
#XS Ineff= 2 , 0
          299.59 1838.08  441.15         1837.82
Permanent Ineff=
       F       F
Bank Sta=359.28,400.09
XS Rating Curve= 0 ,0
Exp/Cntr(USF)=0,0
Exp/Cntr=0.3,0.1

Type RM Length L Ch R = 1 ,10919   ,254.3,246.7,238
XS GIS Cut Line= 4
2463032.31143237565810.7447874232463383.12071738565905.879508782
2463698.25448188566003.9871901842464301.76537051566030.743830566
#Sta/Elev= 30
       01961.16831.532831944.651   71.291920.651118.56681893.688151.72261876.764
189.02291858.012209.74531850.226 259.4791845.669350.65741847.636375.65471843.779
  399.041832.475404.98021831.235 425.9271832.526  450.911826.412472.0099 1825.43
  493.951826.413  510.021830.729539.03971831.937551.60781833.903568.36521832.378
     6211833.033806.1332 1837.52894.21971836.609994.31791838.2181166.487 1835.59
1189.5761838.2891206.3351843.554 1235.881859.751 1277.561886.3311297.6361897.643
#Mann= 8 ,-1 , 0
       0     .12       0   71.29      .1       0  399.04     .06       0
  450.91    .045       0  493.95     .06       0  510.02      .1       0
     621      .1       0 1235.88     .12       0
#XS Ineff= 2 , 0
                          553.09         1835.35
Permanent Ineff=
       F       F
Bank Sta=450.91,493.95
XS Rating Curve= 0 ,0
Exp/Cntr(USF)=0,0
Exp/Cntr=0.3,0.1

Type RM Length L Ch R = 1 ,10673   ,270.6,251.7,234.5
XS GIS Cut Line= 4
2462874.74455012566170.4729525622463270.14823577566179.391832689
2463513.93095925566167.4999925192464313.65721068566087.230071373
#Sta/Elev= 30
       01953.187   80.761915.002148.03811885.159156.04021884.354236.06051850.593
256.06561845.456304.07781842.318383.85971843.242  483.861841.451492.21591838.258
 508.2351838.188516.24441840.238520.2492  1838.3  532.81  1825.3556.29211823.474
     5691825.303   583.81826.773598.93211829.822612.35861830.208  783.05 1829.89
913.76171834.0751066.526 1833.221090.6461835.2081138.8871832.9831335.8721834.464
1347.9321835.7361355.9731838.645 1380.051853.2241424.3141886.6211443.3211898.634
#Mann= 8 ,-1 , 0
       0     .12       0   80.76      .1       0  483.86     .06       0
  532.81    .045       0     569     .06       0   583.8      .1       0
  783.05      .1       0 1380.05     .12       0
#XS Ineff= 2 , 0
                           759.4         1832.92
Permanent Ineff=
       F       F
Bank Sta=532.81,569
XS Rating Curve= 0 ,0
Exp/Cntr(USF)=0,0
Exp/Cntr=0.5,0.3

Type RM Length L Ch R = 1 ,10421   ,123.3,120.1,118.3
XS GIS Cut Line= 4
2462743.93430825566821.5512018632463368.25591717566556.957758083
2463576.36312014566351.8235151532464340.41385106566102.094871585
#Sta/Elev= 30
       01856.97968.218771841.059142.07361837.931176.82881838.302220.27291832.386
359.29371830.851511.34781831.364628.64671832.656   741.11835.879836.8652 1837.74
844.4524 1836.31  862.91  1827.3   876.21824.211911.85151823.314  920.311824.212
  982.191826.058 1051.21 1828.211162.1661831.8021275.7891830.577 1296.831832.413
1334.7041830.6611351.5371832.0551477.7841831.2021528.2831831.7111561.9491834.135
1650.3221833.7921662.9471836.883 1685.86 1851.141738.6951891.3461774.1161913.078
#Mann= 8 ,-1 , 0
       0      .1       0   741.1     .06       0  862.91      .1       0
   876.2    .045       0  920.31      .1       0  982.19      .1       0
 1051.21      .1       0 1685.86     .12       0
#XS Ineff= 2 , 0
             856 1824.79     940         1824.79
Permanent Ineff=
       F       F
Bank Sta=876.2,920.31
XS Rating Curve= 0 ,0
Exp/Cntr(USF)=0,0
Exp/Cntr=0.5,0.3

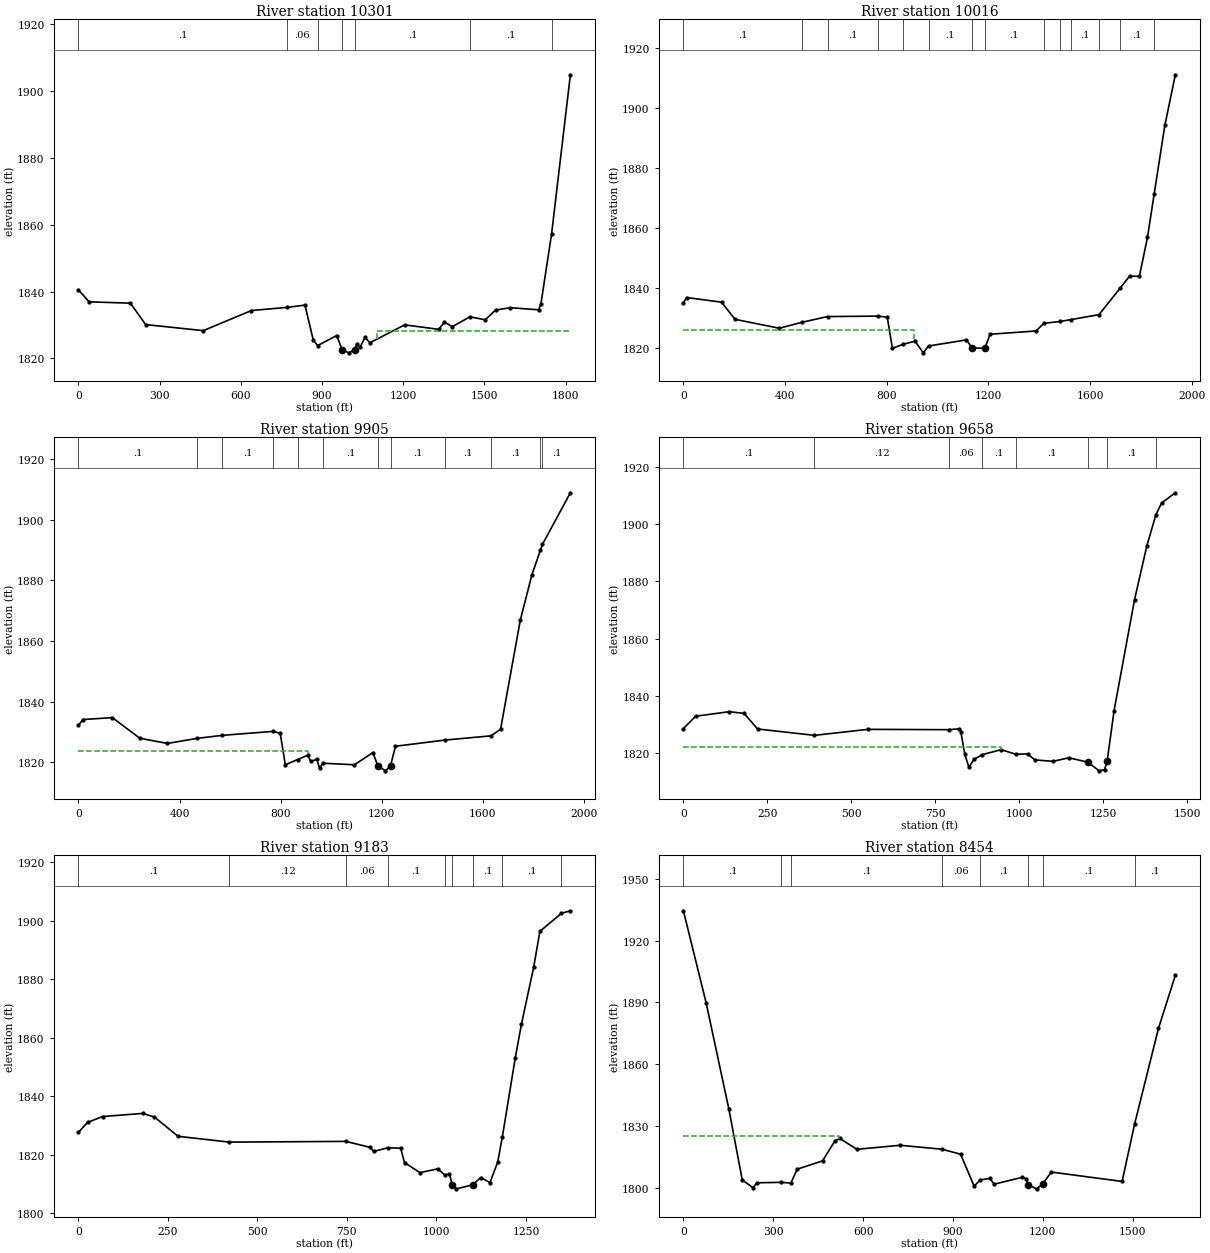
Type RM Length L Ch R = 1 ,10301   ,294.9,284.4,272.4
XS GIS Cut Line= 4
  2462726.096548566949.3884836892463490.14727891 566625.33583906
2463698.25448189566381.5531155772464334.46793097 566179.39183269
#Sta/Elev= 30
       01840.46739.808461836.939191.87971836.548248.36341830.128461.26321828.319
639.40391834.345  770.221835.273837.01141835.964867.81561825.519  884.12 1823.85
954.08891826.843  974.561822.638999.48461821.674 1021.061822.6371027.8571824.173
1040.3191823.3051058.8021826.2921077.2841824.6961205.5351830.0471331.4481828.716
1352.4331830.8711381.8131829.522 1447.121832.4581503.5281831.5671541.3021834.488
1595.8641835.1821700.7911834.5631709.1851836.375 1748.321857.1441818.0191904.923
#Mann= 7 ,-1 , 0
       0      .1       0  770.22     .06       0  884.12      .1       0
  974.56    .045       0 1021.06      .1       0 1447.12      .1       0
 1748.32     .12       0
#XS Ineff= 2 , 0
          954.73 1826.09 1102.88          1828.3
Permanent Ineff=
       F       F
Bank Sta=974.56,1021.06
XS Rating Curve= 0 ,0
Exp/Cntr(USF)=0,0
Exp/Cntr=0.5,0.3

Type RM Length L Ch R = 1 ,10016   ,108.1,111.7,112.6
XS GIS Cut Line= 4
2462714.20470783566988.0369642422463742.84888252566827.497121948
2463835.01064384566562.9036781682464349.33273119566226.959193369
#Sta/Elev= 30
       01835.05612.692141836.795150.33851835.234 202.9681829.517377.05011826.531
  468.061828.556  567.381830.427  766.021830.583802.13451830.216822.37661819.833
  865.331821.186911.4419  1822.2943.82921818.312  964.651820.6091113.7451822.625
1135.7351819.955 1186.311819.8631206.9311824.5191387.8521825.628 1417.771828.165
 1482.131828.791 1526.441829.439  1635.11831.074 1718.911839.9641755.7331843.968
1793.9551843.8491826.0061856.861 1852.441871.4551894.2861894.2711935.5991911.217
#Mann= 14 ,-1 , 0
       0      .1       0  468.06     .12       0  567.38      .1       0
  766.02     .06       0  865.33      .1       0  964.65      .1       0
1135.735    .045       0 1186.31      .1       0 1417.77      .1       0
 1482.13      .1       0 1526.44      .1       0  1635.1      .1       0
 1718.91      .1       0 1852.44      .1       0
#XS Ineff= 2 , 0
          908.09  1825.9    1236         1823.97
Permanent Ineff=
       F       F
Bank Sta=1135.735,1186.31
XS Rating Curve= 0 ,0
Exp/Cntr(USF)=0,0
Exp/Cntr=0.5,0.3

Type RM Length L Ch R = 1 ,9905    ,201.8,246.9,284.5
XS GIS Cut Line= 4
2462717.17766787567017.7665646662463814.19992354566892.902242883
2463956.90200558566565.8766382112464405.81897199566378.580155535
#Sta/Elev= 30
       01832.217 17.68081834.088134.13421834.729243.12711827.906351.82451826.204
  470.41 1827.88  569.831828.876  768.691830.171798.69131829.587818.82041819.156
  868.121820.899907.3886 1822.31919.46611820.267 943.6211820.948  954.421818.068
  967.551819.6791092.5771819.1561165.4771823.1951184.8561818.8281215.4061817.157
1235.4871818.8821254.9291825.274 1449.51  1827.3 1632.591828.7061670.9481830.863
1748.9631866.8611794.8911881.839  1828.9 1890.08 1836.811891.9271947.3321908.943
#Mann= 12 ,-1 , 0
       0      .1       0  470.41     .12       0  569.83      .1       0
  768.69     .06       0  868.12      .1       0  967.55      .1       0
1184.856    .045       01235.487      .1       0 1449.51      .1       0
 1632.59      .1       0  1828.9      .1       0 1836.81      .1       0
#XS Ineff= 2 , 0
          908.09 1823.69 1456.79         1814.39
Permanent Ineff=
       F       F
Bank Sta=1184.856,1235.487
XS Rating Curve= 0 ,0
Exp/Cntr(USF)=0,0
Exp/Cntr=0.5,0.3

Type RM Length L Ch R = 1 ,9658    ,452.7,475.2,490.7
XS GIS Cut Line= 4
2462702.31286766567032.6313648792463742.84888252566976.145124072
2464025.28008656567026.6854447942464159.06328847567044.523205049
#Sta/Elev= 30
       01828.58836.260441832.913136.63311834.503180.69781833.905220.75671828.476
  389.82 1826.25549.23971828.343  789.351828.225821.64011828.544825.64611827.509
837.66371819.586849.68141815.125864.57861817.831  889.23 1819.53945.82281821.247
  989.121819.6631024.1631819.7921046.0261817.6871099.4931817.1921147.6151818.432
1204.5041816.8541237.0121813.8751253.2671814.281 1261.051817.2031281.7111834.911
 1342.571873.5611378.8881892.205  1406.21903.2111423.2781907.3081463.953 1910.84
#Mann= 8 ,-1 , 0
       0      .1       0  389.82     .12       0  789.35     .06       0
  889.23      .1       0  989.12      .1       01204.504    .045       0
 1261.05      .1       0  1406.2     .12       0
#XS Ineff= 2 , 0
          945.95 1822.14
Permanent Ineff=
       F       F
Bank Sta=1204.504,1261.05
XS Rating Curve= 0 ,0
Exp/Cntr(USF)=0,0
Exp/Cntr=0.3,0.1

Type RM Length L Ch R = 1 ,9183    ,720.9,728.4,735.2
XS GIS Cut Line= 4
 2462705.2858277567044.5232050492463516.90391929567252.630408021
2463802.30808337567514.250891759 2463909.3346449567618.304493245
#Sta/Elev= 30
       01827.62925.63728 1831.0367.576811833.025179.07061834.092212.10581832.885
278.1762 1826.26  421.841824.266  746.961824.518814.99811822.467824.81061821.072
  863.711822.319900.06041822.199 910.9131817.274954.32321813.809 1003.16 1815.12
 1024.021812.9981036.1231813.4271044.6161809.653 1055.941808.276 1101.68 1809.66
1123.8871812.1411149.6691810.4041171.3741817.474 1184.341826.1111220.211 1853.04
1237.4391864.5471271.868 1884.221289.0831896.414 1349.341902.5941374.3151903.459
#Mann= 9 ,-1 , 0
       0      .1       0  421.84     .12       0  746.96     .06       0
  863.71      .1       0 1024.02      .1       01044.616    .045       0
 1101.68      .1       0 1184.34      .1       0 1349.34     .05       0
Bank Sta=1044.616,1101.68
XS Rating Curve= 0 ,0
Exp/Cntr(USF)=0,0
Exp/Cntr=0.3,0.1

Type RM Length L Ch R = 1 ,8454    ,267.1,257,242.2
XS GIS Cut Line= 4
2462154.95808029567237.3418920392462974.04900236567646.986189419
 2463193.4534535567960.0388818922463477.07384155568155.362356682
#Sta/Elev= 30
       01934.474  75.7921889.922 151.822 1838.28 196.5451803.875 232.3241800.163
 245.7411802.531  327.211802.753  358.761802.375 379.9121809.116 464.8861813.175
 505.1381822.725 522.1311824.044 579.3731818.769 724.2831820.738  863.871818.788
 925.4681816.413 970.8121800.892  990.971803.941 1023.161804.6391037.8141801.864
1130.6211805.1531145.2751804.4141151.7381801.4341179.4671799.5941199.0051801.859
1228.313 1807.741464.7981803.187 1506.571831.0551586.2181877.446 1642.471903.162
#Mann= 8 ,-1 , 0
       0      .1       0  327.21      .1       0  358.76      .1       0
  863.87     .06       0  990.97      .1       01151.738    .045       0
1199.005      .1       0 1506.57      .1       0
#XS Ineff= 2 , 0
          520.99 1825.46
Permanent Ineff=
       F       F
Bank Sta=1151.738,1199.005
XS Rating Curve= 0 ,0
Exp/Cntr(USF)=0,0
Exp/Cntr=0.3,0.1

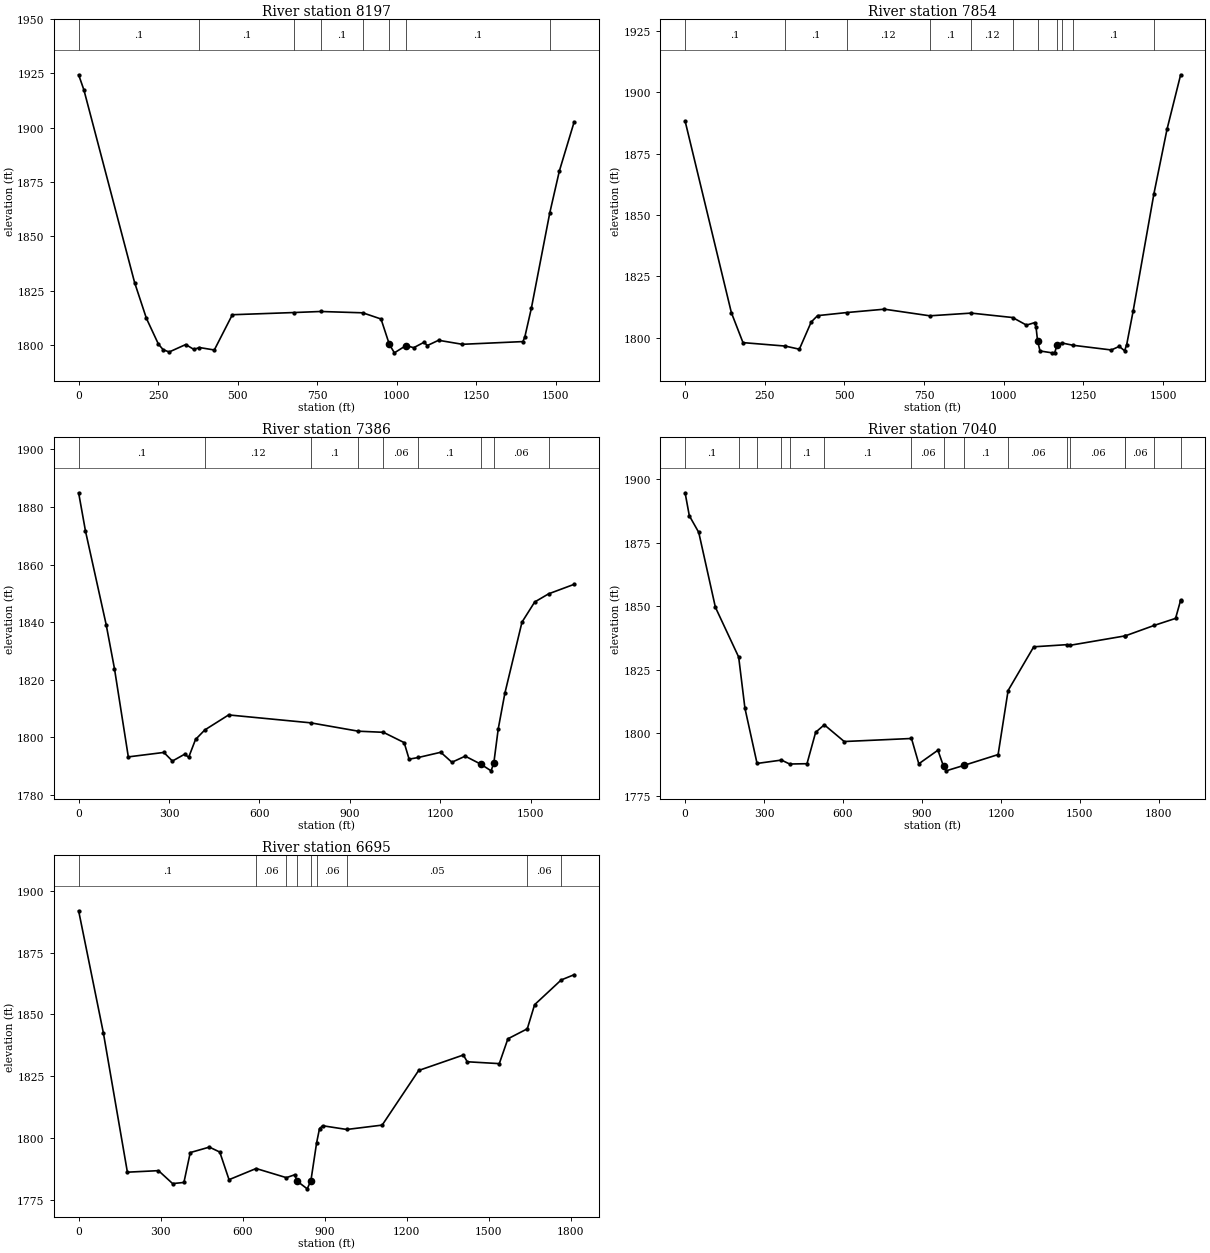
Type RM Length L Ch R = 1 ,8197    ,347,343,337.7
XS GIS Cut Line= 4
2462089.81273021567502.0637686372462856.31978468567984.119858236
2463043.61626736568096.4977478412463436.93888097 568278.44290244
#Sta/Elev= 30
       01924.392  16.5811917.406 175.9371828.654 213.0421812.156 250.7531800.294
 265.7171797.724 284.6181796.687 336.5961800.112 362.2051797.854   379.31798.741
 426.3761797.597  483.081813.846  676.661814.854  760.631815.336  892.981814.725
 950.3011811.873 976.3331800.228 992.2831796.2851028.8111799.6411052.9251798.654
1085.5791801.1621095.8671799.6461131.0861802.0721205.8321800.2191396.2021801.469
1402.2851803.6611422.6451816.758 1480.761860.873 1510.791880.101 1557.28  1902.7
#Mann= 8 ,-1 , 0
       0      .1       0   379.3      .1       0  676.66     .12       0
  760.63      .1       0  892.98     .06       0 976.333    .045       0
1028.811      .1       0 1480.76      .1       0
Bank Sta=976.333,1028.811
XS Rating Curve= 0 ,0
Exp/Cntr(USF)=0,0
Exp/Cntr=0.3,0.1

Type RM Length L Ch R = 1 ,7854    ,449.2,468.6,483
XS GIS Cut Line= 4
2462083.05287763567665.7158376872462909.83306544 568353.36149551
2463048.96759543568396.172120122 2463305.8313431 568610.22524318
#Sta/Elev= 30
       01888.309 145.2751810.219181.69381798.029   314.31796.624358.58541795.347
395.92631806.451415.81491809.022  507.721810.285625.49041811.648   768.11808.952
   897.91810.054 1027.961808.2511071.3541805.164 1097.251806.1731101.4351804.389
1106.1271798.883 1113.991794.6281151.6561793.8681160.026    17941168.3961797.236
  1182.71797.884 1217.111796.9571337.7391795.034 1362.651796.4951379.4611794.692
 1386.021797.2261406.387 1811.01 1471.531858.7271512.6071884.9731555.3041907.137
#Mann= 11 ,-1 , 0
       0      .1       0   314.3      .1       0  507.72     .12       0
   768.1      .1       0   897.9     .12       0 1027.96     .06       0
1106.127    .045       01168.396     .06       0  1182.7      .1       0
 1217.11      .1       0 1471.53      .1       0
Bank Sta=1106.127,1168.396
XS Rating Curve= 0 ,0
Exp/Cntr(USF)=0,0
Exp/Cntr=0.3,0.1

Type RM Length L Ch R = 1 ,7386    ,340.8,345.6,313.2
XS GIS Cut Line= 4
2461970.67498803567834.2826720952462741.26623104568604.873915104
2462936.58970583568904.5482873852463065.02157966569054.385473525
#Sta/Elev= 30
       01884.89622.726481871.618 91.36981839.156 118.8931823.906164.90891793.249
282.94181794.794 311.2261791.802351.58511794.159365.3467 1793.12387.97411799.286
  418.861802.601497.90231807.807  769.921805.069  928.341802.161 1011.551801.778
1080.5581798.1981096.9631792.457 1127.491793.0351202.005 1794.851238.9981791.383
1283.174  1793.51334.2291790.7591369.1171788.4061378.1821791.1931392.8331803.002
 1414.81 1815.351471.6491840.0141513.795    1847 1560.191849.8381644.8371853.134
#Mann= 9 ,-1 , 0
       0      .1       0  418.86     .12       0  769.92      .1       0
  928.34     .12       0 1011.55     .06       0 1127.49      .1       0
1334.229    .045       01378.182     .06       0 1560.19     .12       0
Bank Sta=1334.229,1378.182
XS Rating Curve= 0 ,0
Exp/Cntr(USF)=0,0
Exp/Cntr=0.3,0.1

Type RM Length L Ch R = 1 ,7040    ,328.4,345.3,321
XS GIS Cut Line= 4
2461844.91877823568166.0650128352462446.94318683  568730.6301249
2462714.50959065569054.385473525 2463102.4808762569560.085976749
#Sta/Elev= 30
       01894.72216.025721885.67551.856851879.105115.07171849.594   203.51829.966
227.33491809.781  273.421788.011  366.17 1789.34  397.211787.784463.13351787.911
496.03561800.301  528.831803.246604.64181796.653  860.171797.853887.93771787.879
 960.587 1793.23 981.9921786.832991.72251785.0971059.1831787.2441189.198 1791.51
  1227.21816.7571324.5831833.997 1449.881834.841 1463.261834.603 1672.18 1838.31
 1672.851838.326 1783.341842.471 1863.44  1845.2 1882.441852.2511882.7211852.422
#Mann= 16 ,-1 , 0
       0      .1       0   203.5      .1       0  273.42      .1       0
  366.17      .1       0  397.21      .1       0  528.83      .1       0
  860.17     .06       0 981.992    .045       01059.183      .1       0
  1227.2     .06       0 1449.88     .05       0 1463.26     .06       0
 1672.18     .05       0 1672.85     .06       0 1783.34    .055       0
 1882.44      .1       0
Bank Sta=981.992,1059.183
XS Rating Curve= 0 ,0
Exp/Cntr(USF)=0,0
Exp/Cntr=0.3,0.1

Type RM Length L Ch R = 1 ,6695    ,489.1,480.1,462.3
XS GIS Cut Line= 4
2461788.72983343568594.1712589512462291.75467261569006.223520837
2462471.02416318569244.3576202392462984.75165852569940.030270177
#Sta/Elev= 30
       01891.97490.50681 1842.51178.4086 1786.07292.16391786.688343.87081781.446
385.23641781.908408.40231794.011478.30891796.225516.41231794.228550.30361783.031
  649.371787.554  760.11 1783.85791.27121785.051798.53611782.516 836.332 1779.32
849.95151782.687  870.721797.965881.39271803.753892.79771804.886  981.161803.374
1110.5841805.1411244.1211827.2731407.5691833.545 1421.871830.8061539.1411830.048
1570.6041840.103 1641.571844.1521668.3331853.922  1765.61863.9431813.1151866.078
#Mann= 9 ,-1 , 0
       0      .1       0  649.37     .06       0  760.11      .1       0
798.5361    .045       0849.9515      .1       0  870.72     .06       0
  981.16     .05       0 1641.57     .06       0  1765.6      .1       0
Bank Sta=798.5361,849.9515
XS Rating Curve= 0 ,0
Exp/Cntr(USF)=0,0
Exp/Cntr=0.3,0.1