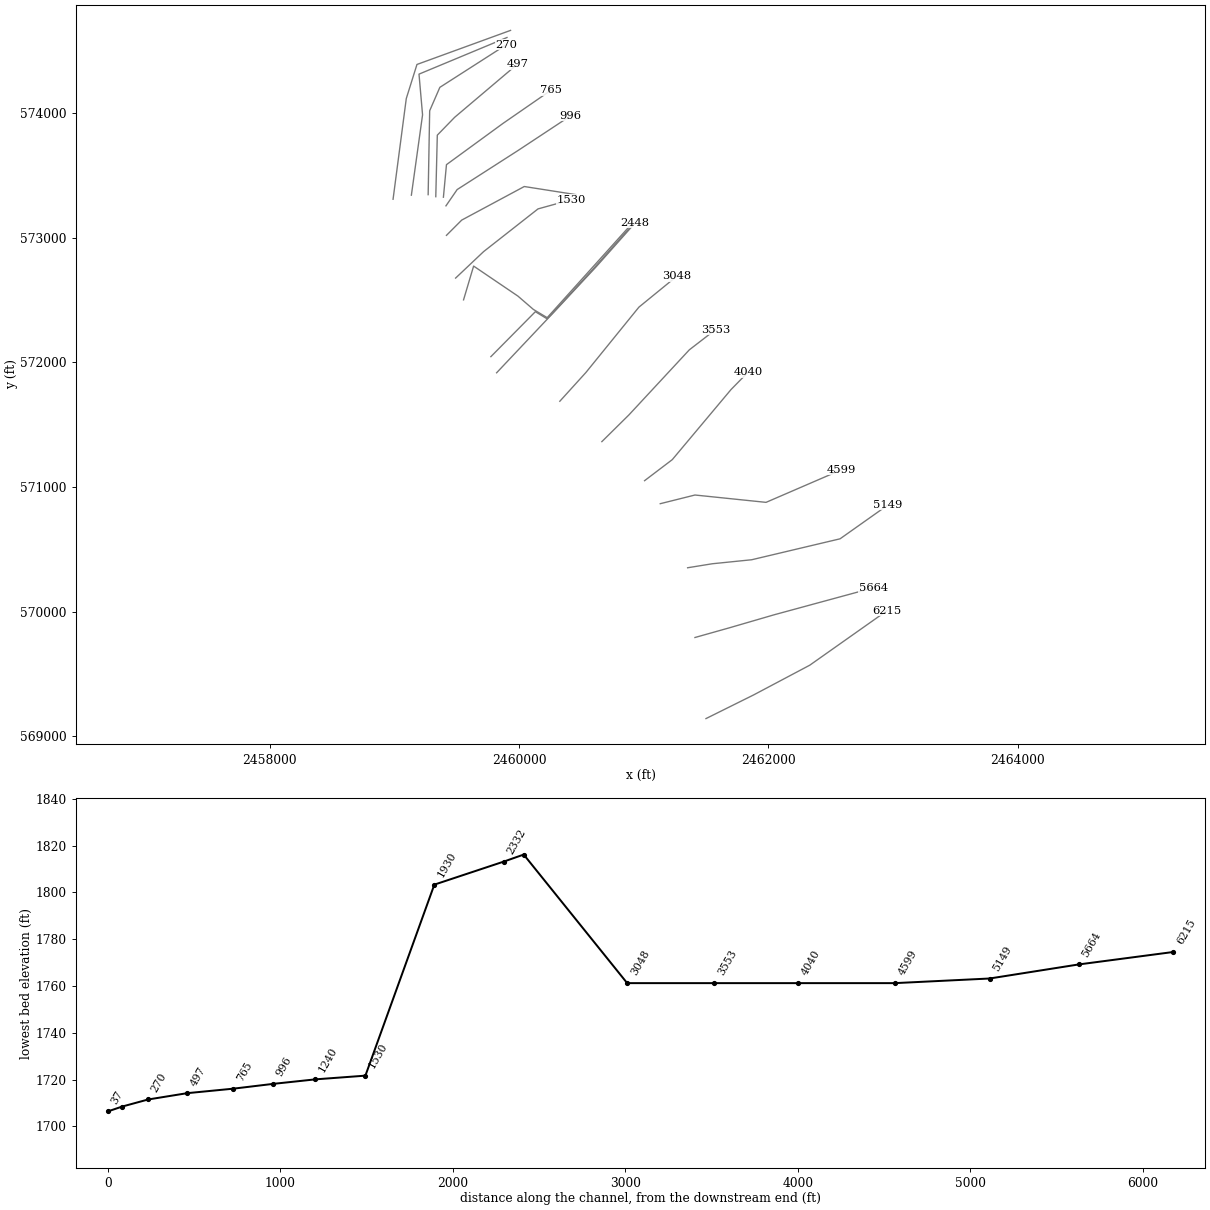
HEC-RAS study LITTLEFK.prj: LITTLEFK

--- LITTLEFK.g01 (geometry) --- (continued)

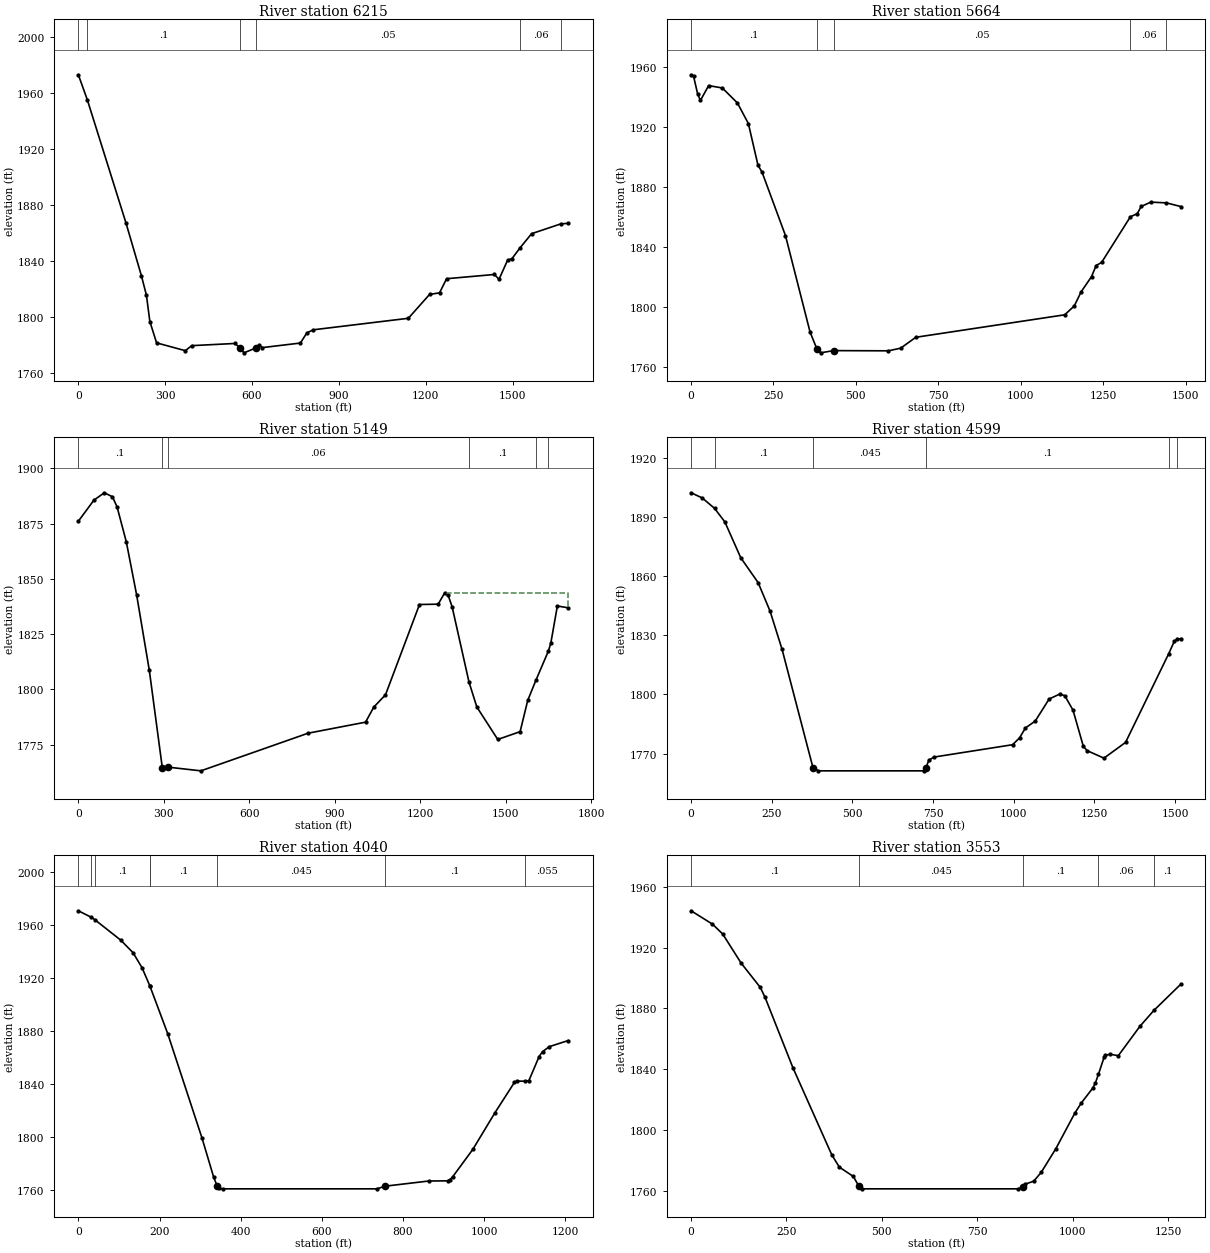
Type RM Length L Ch R = 1 ,6215    ,553.5,550.3,540.7
XS GIS Cut Line= 4
 2461499.7581173569142.6823867872461882.37807477569332.654533501
2462331.88963319569570.7886329022462949.96802602570006.921871133
#Sta/Elev= 30
       01973.249    31.21955.241164.10721867.672 217.6981829.759235.15331815.806
247.09021796.917270.30981781.667369.5385 1776.09 391.8681779.687540.76651781.242
559.30911778.023572.45291774.549612.5718 1777.99 624.4081780.045635.82571778.295
767.09791781.548 789.7311788.881812.36421791.0291140.0911799.2371213.5251816.313
1247.7941817.4041272.2721827.5171437.4231830.5481453.4081827.0971482.781 1840.69
1498.0251841.828 1526.581849.7321566.006  1859.7 1666.881866.7011692.3391867.095
#Mann= 6 ,-1 , 0
       0      .1       0    31.2      .1       0559.3091    .045       0
612.5718     .05       0 1526.58     .06       0 1666.88      .1       0
Bank Sta=559.3091,612.5718
XS Rating Curve= 0 ,0
Exp/Cntr(USF)=0,0
Exp/Cntr=0.3,0.1

Type RM Length L Ch R = 1 ,5664    ,517.5,515.5,512.6
XS GIS Cut Line= 4
2461411.46120404569792.8687480752461687.05459998569870.463005184
 2462045.5935811569974.8139026742462842.94146449 570191.54268977
#Sta/Elev= 30
       0 1954.827.5670341953.771 20.03361941.93128.344641937.67153.277771947.595
94.832981946.007140.54371936.005173.78791922.273202.87651894.504215.34311889.795
286.30861847.503360.97361783.052381.80351771.747392.88911769.203432.13051770.693
 598.4341770.547635.92771772.321681.64321779.5861133.4621794.5921162.4781800.497
1183.2041809.9111214.7951820.084  1228.81827.4831245.3811829.565 1332.851860.089
1353.1541862.025 1365.591866.9271394.6061869.808 1441.921869.3161486.0021866.853
#Mann= 5 ,-1 , 0
       0      .1       0381.8035    .045       0432.1305     .05       0
 1332.85     .06       0 1441.92      .1       0
Bank Sta=381.8035,432.1305
XS Rating Curve= 0 ,0
Exp/Cntr(USF)=0,0
Exp/Cntr=0.3,0.1

Type RM Length L Ch R = 1 ,5149    ,568.3,549.9,532.6
XS GIS Cut Line= 5
 2461352.5965952570352.0825320642461550.59573403570384.190500523
2461866.32409054570416.2984689812462574.91920096570584.220311592
2462960.44075533 570856.82837603
#Sta/Elev= 30
       01876.058  54.8561885.631  91.3261888.922 119.6921887.116 135.901 1882.52
 168.3191866.713 204.7561842.534 248.9831808.627 294.4231764.697 313.313 1764.89
 429.9121763.199  806.131780.2211007.558 1785.211036.334 1792.021077.4421797.567
1196.6541838.3971262.3021838.558 1285.261843.719 1296.741842.7741311.0881837.422
 1370.391803.3331397.8181792.0771471.3031777.3861549.6871780.9111576.4111795.063
 1604.911804.086 1648.761817.3241657.4651820.9891680.3331837.741 1718.331836.907
#Mann= 6 ,-1 , 0
       0      .1       0 294.423    .045       0 313.313     .06       0
 1370.39      .1       0 1604.91     .06       0 1648.76    .055       0
#XS Ineff= 2 , 0
                         1293.83         1843.69
Permanent Ineff=
       F       F
Bank Sta=294.423,313.313
XS Rating Curve= 0 ,0
Exp/Cntr(USF)=0,0
Exp/Cntr=0.3,0.1

Type RM Length L Ch R = 1 ,4599    ,439.6,559.4,800.5
XS GIS Cut Line= 4
2461133.19214406570865.8100274032461411.46120404570935.377292397
2461981.37764418570876.5126835562462585.66493584 571137.56068397
#Sta/Elev= 30
       01902.215  34.5861899.601   73.031894.271 104.6781887.438 153.9021869.282
 207.7561856.664 244.8641842.148 281.9721822.825 377.7441762.815 394.6881761.219
 720.4111761.219 728.4541762.885 736.4971766.576 753.1611768.208 996.3471774.467
1018.1331777.9621036.0711782.9371066.4991786.4551109.6361797.6361142.5691800.165
1158.2861799.292 1183.711791.9391215.5961773.6781227.2831771.4621279.4951767.655
1346.4371775.632 1480.031820.5551497.4341826.886 1506.361827.9911518.0441828.248
#Mann= 6 ,-1 , 0
       0      .1       0   73.03      .1       0 377.744    .045       0
 728.454      .1       0 1480.03     .06       0 1506.36    .055       0
Bank Sta=377.744,728.454
XS Rating Curve= 0 ,0
Exp/Cntr(USF)=0,0
Exp/Cntr=0.3,0.1

Type RM Length L Ch R = 1 ,4040    ,505.9,486.9,487.8
XS GIS Cut Line= 4
2461007.43593427 571050.430846042461229.51604944571218.997680448
2461700.43292017571780.8871284752461836.89178612571920.021658463
#Sta/Elev= 30
       01970.769   32.131965.806   40.971963.954104.58981948.594134.72041939.188
156.85151927.886  176.171914.187  176.491913.902220.09051878.249304.76471799.406
333.55361769.849342.07171763.292347.75051761.552355.44941761.219 735.3131761.219
756.6209 1763.25863.20281767.115909.94741767.235915.39321768.167922.13121770.248
971.94941790.9841026.6681818.7151074.3921841.433 1080.051842.419 1100.181842.333
1109.9941842.7711135.2071860.938 1143.611864.5991160.418 1868.391206.8241872.963
#Mann= 8 ,-1 , 0
       0      .1       0   32.13      .1       0   40.97      .1       0
  176.17      .1       0  176.49      .1       0342.0717    .045       0
756.6209      .1       0 1100.18    .055       0
Bank Sta=342.0717,756.6209
XS Rating Curve= 0 ,0
Exp/Cntr(USF)=0,0
Exp/Cntr=0.3,0.1

Type RM Length L Ch R = 1 ,3553    ,507.9,504.7,527.8
XS GIS Cut Line= 4
2460664.95093737571363.4835385132460881.67972447 571577.53666157
2461365.97491539572099.2911490242461577.35237441572262.506655356
#Sta/Elev= 30
       01944.22456.079781935.41382.875531928.934130.95971909.854181.31081893.805
193.67111887.345266.72681840.996368.59521783.644 388.4081775.535 425.2031769.351
439.35491763.089448.35911761.219857.67661761.219868.59171762.517875.23461764.314
897.87761766.242917.66931772.149955.91281787.6931005.8651811.1811022.5191817.737
1052.8411827.6131059.5311830.996 1067.33 1836.541082.3451847.8911085.1971849.062
1098.3241849.8251119.417 1848.831176.4521868.293 1212.641878.638 1283.551895.985
#Mann= 5 ,-1 , 0
       0      .1       0439.3549    .045       0868.5917      .1       0
 1067.33     .06       0 1212.64      .1       0
Bank Sta=439.3549,868.5917
XS Rating Curve= 0 ,0
Exp/Cntr(USF)=0,0
Exp/Cntr=0.3,0.1

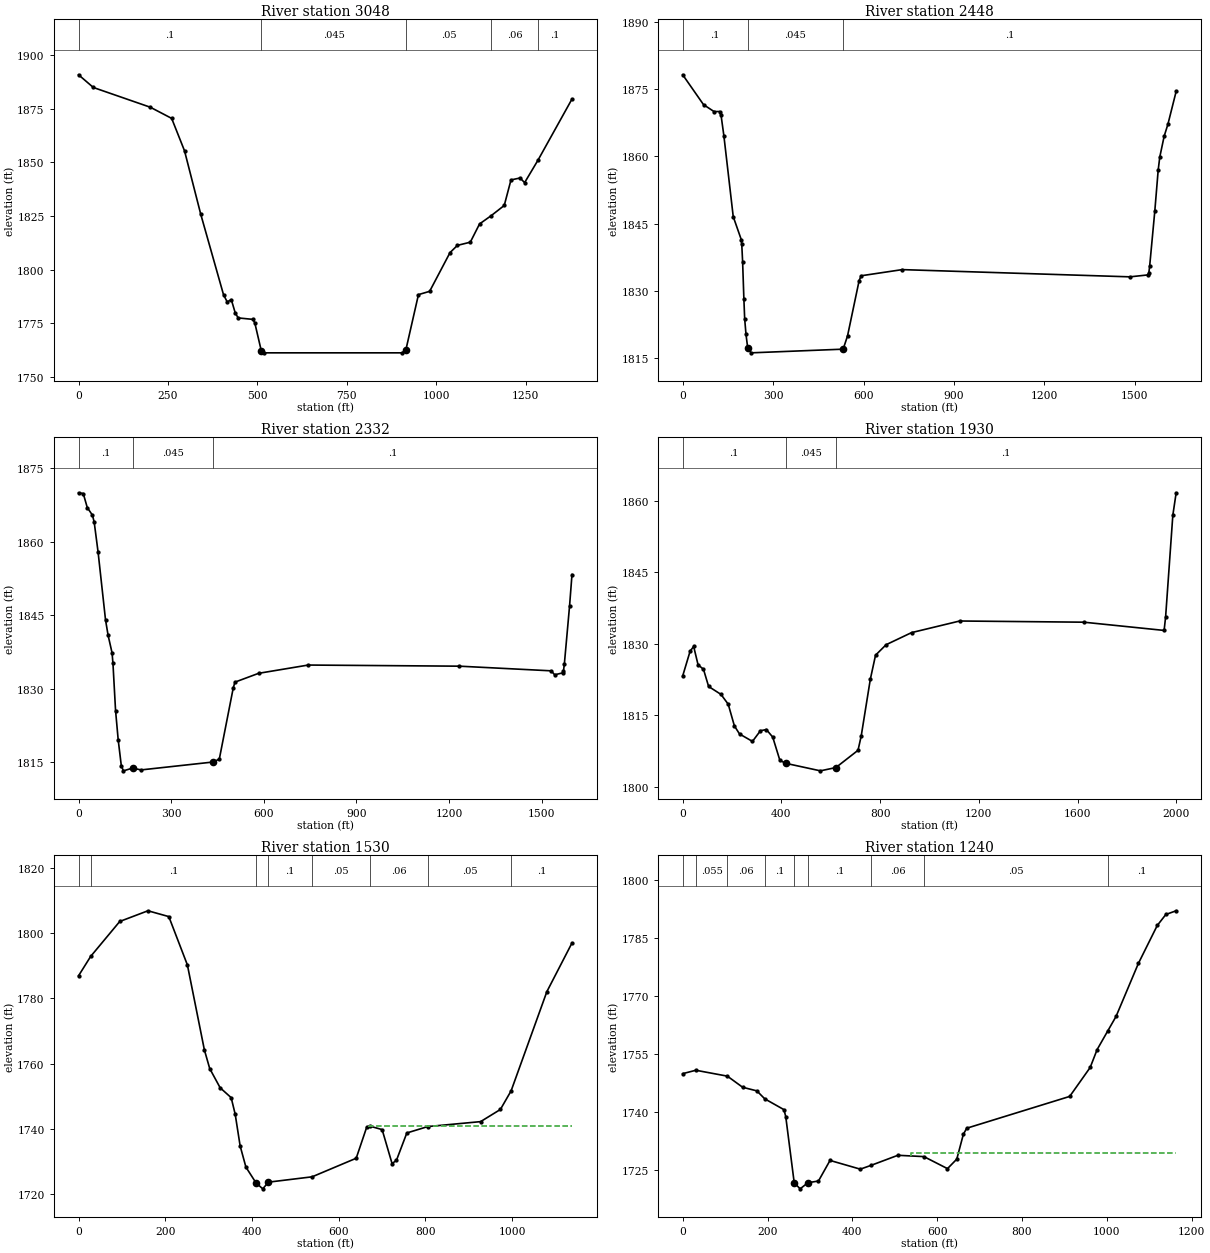
Type RM Length L Ch R = 1 ,3048    ,729.2,599.9,926.3
XS GIS Cut Line= 4
2460327.81726856571687.2388871382460536.51906354571917.345994425
2460961.94964562572441.7761459172461266.97534598572690.612901472
#Sta/Elev= 30
       01890.871 41.47141884.941200.84071875.729260.38091870.541296.33251855.426
 341.7721825.797 405.3551788.336415.70951784.943427.08451786.063438.45941779.646
446.56031777.498487.76561776.818492.91631775.116511.01371762.128518.66961761.219
904.66721761.219915.27091762.661950.33411788.362981.61541789.8951038.5931807.948
1059.2421811.3221095.3341812.8121121.1881821.325 1153.43 1825.141190.1991829.931
1209.0521841.8391234.4941842.753 1247.151840.575 1284.591851.0691379.595 1879.55
#Mann= 5 ,-1 , 0
       0      .1       0511.0137    .045       0915.2709     .05       0
 1153.43     .06       0 1284.59      .1       0
Bank Sta=511.0137,915.2709
XS Rating Curve= 0 ,0
Exp/Cntr(USF)=0,0
Exp/Cntr=0.5,0.3

Type RM Length L Ch R = 1 ,2448    ,120.5,115.7,113.1
XS GIS Cut Line= 4
2459821.06110962571915.5370936092460306.84762508 572429.89928644
2460617.60811658572763.8775158142460931.94056775573117.501523386
#Sta/Elev= 30
       0 1878.19    69.1 1871.53     104 1869.99   122.3    1870   127.3 1869.13
   136.5 1864.64   167.6 1846.57   194.6 1841.38   195.9 1840.41   198.7 1836.56
     203  1828.1   205.6 1823.76     210  1820.3   215.61817.314     227 1816.21
   532.21817.029   546.7 1819.97   585.2 1832.31     592 1833.39   728.1 1834.76
  1483.7 1833.15  1543.2 1833.58  1546.1 1834.02  1548.9 1835.53  1565.9 1847.77
  1577.2 1856.96  1582.5 1859.87    1597  1864.5  1609.3 1867.13  1636.8 1874.49
#Mann= 3 , 0 , 0
       0      .1       0   215.6    .045       0   532.2      .1       0
Bank Sta=215.6,532.2
XS Rating Curve= 0 ,0
Exp/Cntr(USF)=0,0
Exp/Cntr=0.3,0.1

Type RM Length L Ch R = 1 ,2332    ,644.8,402.3,240.9
XS GIS Cut Line= 6
2459774.99013915572044.8742087122460131.73246752572405.522474982
2460224.47801626572348.927328261 2460265.7440812572389.376243402
2460595.25497448572747.9368681542460885.57294214573074.684696612
#Sta/Elev= 30
       0    1870    15.3 1869.85    28.3 1866.98    45.2 1865.41    50.8 1863.97
    63.4 1857.85    87.4 1844.04    95.8 1840.87   108.6  1837.3   111.5 1835.13
   119.9 1825.52   128.4 1819.56   138.6  1814.2   145.4  1813.2   174.81813.755
   202.7 1813.39   436.61815.008   455.9 1815.61   500.9 1830.11   506.5 1831.32
   583.1 1833.12   743.7 1834.81    1233 1834.58  1530.5 1833.63  1541.8 1832.82
  1567.3 1833.21  1570.2 1833.59    1573 1834.95    1590 1846.91  1597.8 1853.29
#Mann= 3 , 0 , 0
       0      .1       0   174.8    .045       0   436.6      .1       0
Bank Sta=174.8,436.6
XS Rating Curve= 0 ,0
Exp/Cntr(USF)=0,0
Exp/Cntr=0.3,0.1

Type RM Length L Ch R = 1 ,1930    ,277.4,399.7,573.4
XS GIS Cut Line= 6
2459555.81940476572500.3094983052459636.54212139572771.121192832
2459991.98247046572530.2550222192460115.67050402572423.492719569
2460226.47423885572357.4145457312460892.08887969573096.291290005
#Sta/Elev= 30
       0 1823.28    29.9 1828.45    44.4 1829.47    62.2 1825.62    84.2 1824.67
     105 1821.06   155.1  1819.4   184.4 1817.34   209.4 1812.79   230.2 1811.09
   282.6 1809.53     315 1811.77   338.8 1812.02   364.7 1810.44   393.7 1805.56
   417.11804.931   557.9 1803.35   620.61804.039   710.3 1807.66   723.2 1810.65
   760.1 1822.56   781.3 1827.63   824.1 1829.83   927.2 1832.37  1122.3 1834.81
    1625 1834.56  1950.5 1832.83  1956.6 1835.69  1985.8 1857.01  1999.3 1861.73
#Mann= 3 , 0 , 0
       0      .1       0   417.1    .045       0   620.6      .1       0
Bank Sta=417.1,620.6
XS Rating Curve= 0 ,0
Exp/Cntr(USF)=0,0
Exp/Cntr=0.3,0.1

Type RM Length L Ch R = 1 ,1530    ,293.1,290.3,285.8
XS GIS Cut Line= 4
  2459492.226679572674.9467478322459716.52407589572887.009741259
2460152.88446621573229.573038334  2460417.963208573302.979459136
#Sta/Elev= 30
       01786.933   28.021792.882 95.11671803.589160.19611806.865208.29821805.082
 251.1791790.263290.35491764.233302.67931758.508326.75431752.617 352.181 1749.59
361.45131744.522372.84671734.812386.21531728.295  409.481723.473425.08191721.646
438.03751723.692  538.93 1725.33640.63961731.023664.75931740.498  672.361740.856
700.46561739.802723.41151729.377733.58221730.418757.44291738.767   805.81740.731
927.62461742.244973.28051745.969  998.041751.6751080.5471782.0841138.4911796.994
#Mann= 8 ,-1 , 0
       0      .1       0   28.02      .1       0  409.48    .045       0
438.0375      .1       0  538.93     .05       0  672.36     .06       0
   805.8     .05       0  998.04      .1       0
#XS Ineff= 2 , 0
                          669.96         1741.03
Permanent Ineff=
       F       F
Bank Sta=409.48,438.0375
XS Rating Curve= 0 ,0
Exp/Cntr(USF)=0,0
Exp/Cntr=0.3,0.1

Type RM Length L Ch R = 1 ,1240    ,241.6,243.8,244.3
XS GIS Cut Line= 4
 2459418.8202582573017.5100449072459541.16429287573139.854079577
2460042.77483501 573409.010955852460458.74455289573343.760804026
#Sta/Elev= 30
       01749.918   30.96  1750.8  105.321749.272 141.3151746.389174.81451745.455
  193.47 1743.39238.66281740.589242.9066 1738.81  262.891721.639276.87571720.059
  295.111721.639320.07751722.089347.31441727.423418.68011725.161   443.61726.127
507.30781728.758  568.661728.414 624.2221725.299 646.1581727.762661.65881734.206
669.61671735.774912.30621744.015960.60211751.518977.08881756.175 1001.681760.917
1021.6271764.7491074.2631778.4881118.8011788.3381139.0451791.1851163.3381792.142
#Mann= 9 ,-1 , 0
       0     .05       0   30.96    .055       0  105.32     .06       0
  193.47      .1       0  262.89    .045       0  295.11      .1       0
   443.6     .06       0  568.66     .05       0 1001.68      .1       0
#XS Ineff= 2 , 0
                          538.27          1729.3
Permanent Ineff=
       F       F
Bank Sta=262.89,295.11
XS Rating Curve= 0 ,0
Exp/Cntr(USF)=0,0
Exp/Cntr=0.3,0.1

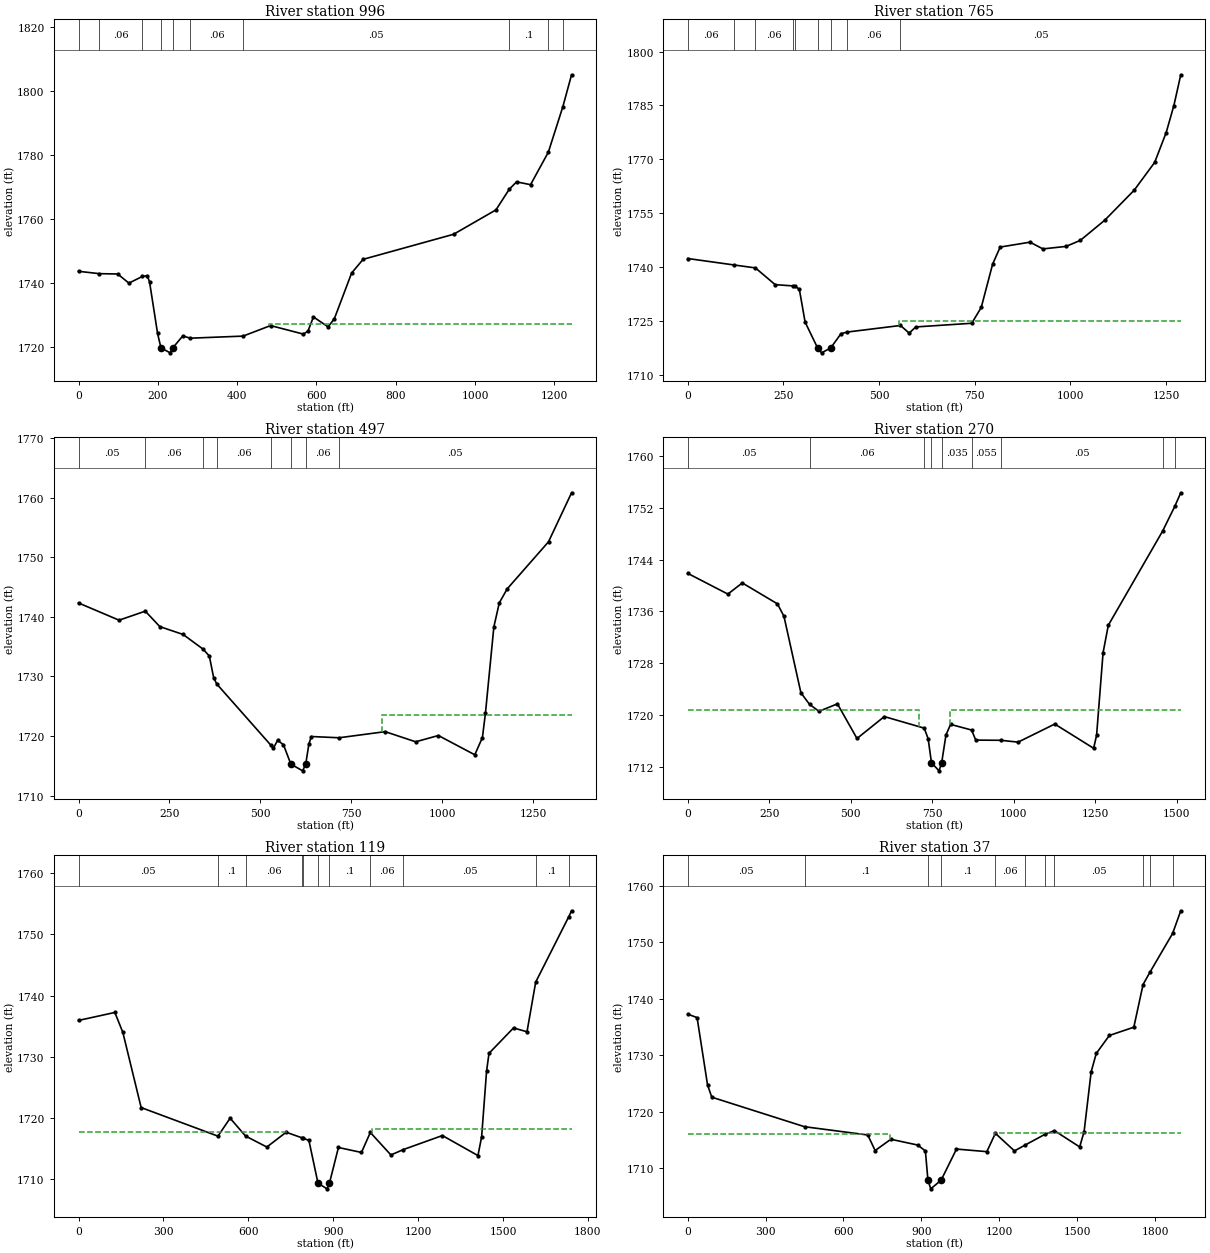
Type RM Length L Ch R = 1 ,996     ,228.2,230.6,232
XS GIS Cut Line= 4
2459414.74212371573254.0418452682459504.46108246573384.542148916
2459993.83722114573698.5585045682460413.88507351573975.871649819
#Sta/Elev= 30
       01743.602   52.131742.86798.852721742.757127.09491739.906  161.051742.006
173.29911742.232179.08921740.318199.35431724.188  207.85 1719.68231.19951718.134
  237.691719.679263.04481723.448  281.471722.709   414.9 1723.36484.26071726.649
 567.0221723.982578.60211724.933592.30631729.344  629.341726.247645.18761728.831
688.61291743.062717.56311747.338945.70251755.1661052.5241762.786 1086.111769.236
1104.491 1771.541139.7361770.656 1184.56  1780.8 1221.13 1794.991243.1571804.984
#Mann= 10 ,-1 , 0
       0     .05       0   52.13     .06       0  161.05      .1       0
  207.85    .045       0  237.69      .1       0  281.47     .06       0
   414.9     .05       0 1086.11      .1       0 1184.56     .05       0
 1221.13      .1       0
#XS Ineff= 2 , 0
                          480.11         1727.23
Permanent Ineff=
       F       F
Bank Sta=207.85,237.69
XS Rating Curve= 0 ,0
Exp/Cntr(USF)=0,0
Exp/Cntr=0.3,0.1

Type RM Length L Ch R = 1 ,765     ,265.2,268.5,275.7
XS GIS Cut Line= 4
2459394.35145126573323.370131581 2459418.8202582573584.370738876
2459871.49318647573914.6996324842460254.83782844574179.778374268
#Sta/Elev= 30
       01742.359  120.551740.567  176.981739.741228.51841735.081  275.681734.725
  279.871734.651291.76261733.807306.8361 1724.65  339.551717.432349.77721716.089
  373.591717.431400.70171721.424  416.951721.881  555.981723.706578.96561721.588
595.97341723.302742.37431724.323767.13311728.723796.84381740.766816.65091745.547
 894.5671746.907928.35871745.033988.8836 1745.73 1026.26 1747.421090.1151753.041
1166.9051761.386  1220.41769.1231250.5171777.4411270.6421784.9681288.5971793.525
#Mann= 9 ,-1 , 0
       0     .06       0  120.55     .05       0  176.98     .06       0
  275.68    .055       0  279.87     .05       0  339.55    .045       0
  373.59     .05       0  416.95     .06       0  555.98     .05       0
#XS Ineff= 2 , 0
                          551.17         1725.09
Permanent Ineff=
       F       F
Bank Sta=339.55,373.59
XS Rating Curve= 0 ,0
Exp/Cntr(USF)=0,0
Exp/Cntr=0.3,0.1

Type RM Length L Ch R = 1 ,497     ,218.3,226.4,229.6
XS GIS Cut Line= 4
2459333.17943393 573327.448266072459345.41383739573820.902539237
2459484.07041002573963.6372463522459989.75908665574391.841367695
#Sta/Elev= 30
       01742.349111.47691739.456  183.551740.973223.51131738.375287.53091737.057
  342.221734.603359.55311733.445371.55681729.777  380.241728.722  529.431718.413
535.70091717.946547.18231719.288563.29751718.542  583.651715.286616.06991714.154
  624.551715.285633.29191718.693640.21841719.917  716.221719.709842.86481720.736
926.72741719.031989.13581720.0861089.2111716.8521110.177 1719.741118.5461723.855
1141.6251738.3221156.5861742.3671178.3151744.7191291.8621752.6231355.2311760.855
#Mann= 8 ,-1 , 0
       0     .05       0  183.55     .06       0  342.22     .05       0
  380.24     .06       0  529.43     .05       0  583.65    .045       0
  624.55     .06       0  716.22     .05       0
#XS Ineff= 2 , 0
                          835.39         1723.51
Permanent Ineff=
       F       F
Bank Sta=583.65,624.55
XS Rating Curve= 0 ,0
Exp/Cntr(USF)=0,0
Exp/Cntr=0.5,0.3

Type RM Length L Ch R = 1 ,270     ,139.3,151.6,163.1
XS GIS Cut Line= 4
2459272.00741659573343.7608040262459284.24182006574016.652994709
2459365.80450984574204.247181202 2459900.0401279574546.810478277
#Sta/Elev= 30
       01741.875123.1504 1738.68167.46441740.394275.17551737.174295.17881735.262
347.18741723.475  373.791721.684402.61521720.624 459.2061721.769519.21591716.436
603.0054 1719.81  725.341718.029737.4063  1716.4  747.661712.696770.84611711.452
  778.911712.693 792.1261716.992806.29521718.607  870.631717.738883.43051716.188
  960.491716.1571013.3361715.8751125.7671718.6611244.9541714.9261254.0631716.933
1273.9061729.6461290.0311733.883 1456.221748.354 1494.051752.2121512.1931754.284
#Mann= 9 ,-1 , 0
       0     .05       0  373.79     .06       0  725.34     .06       0
  747.66    .045       0  778.91    .035       0  870.63    .055       0
  960.49     .05       0 1456.22      .1       0 1494.05     .05       0
#XS Ineff= 2 , 0
          708.92 1720.79  805.49         1720.79
Permanent Ineff=
       F       F
Bank Sta=747.66,778.91
XS Rating Curve= 0 ,0
Exp/Cntr(USF)=0,0
Exp/Cntr=0.5,0.3

Type RM Length L Ch R = 1 ,119     ,92.5,82.3,75.9
XS GIS Cut Line= 4
2459137.42897846573339.6826695372459227.14793721573984.027918797
2459198.60099579574310.2786779162459904.11826239574603.904361123
#Sta/Elev= 30
       01735.944128.4354 1737.25156.7056 1733.98 221.3231721.694  492.611717.019
535.75731719.955  590.15 1717.04665.48131715.239733.74111717.657  789.231716.751
  794.211716.654814.04681716.337  846.24 1709.32878.29131708.401  886.641709.319
918.44411715.163999.87781714.351 1031.161717.622 1103.861713.942 1148.031714.829
1285.8291717.1181411.474 1713.841424.4721716.9331441.8021727.6061450.4671730.564
1537.1191734.7171584.778 1734.09 1615.491742.214 1732.361752.9121742.2391753.879
#Mann= 11 ,-1 , 0
       0     .05       0  492.61      .1       0  590.15     .06       0
  789.23    .055       0  794.21      .1       0  846.24    .045       0
  886.64      .1       0 1031.16     .06       0 1148.03     .05       0
 1615.49      .1       0 1732.36     .05       0
#XS Ineff= 2 , 0
           735.8 1717.71 1037.04         1718.16
Permanent Ineff=
       F       F
Bank Sta=846.24,886.64
XS Rating Curve= 0 ,0
Exp/Cntr(USF)=0,0
Exp/Cntr=0.5,0.3

Type RM Length L Ch R = 1 ,37      ,37,37,37
XS GIS Cut Line= 4
2458990.61613685573307.0575936252459096.64763357574114.528222444
2459182.28845783574387.7632332062459932.66520381574660.998243968
#Sta/Elev= 30
       01737.248 36.14091736.64376.484291724.72192.684041722.557  449.921717.334
693.73821715.867721.97851713.111782.49361715.111886.04451714.087915.54921713.047
  925.39 1707.88 936.3471706.338  976.32 1707.881035.4011713.3791152.3141712.917
 1185.121716.1581258.7371713.048 1298.911714.065 1375.891715.976 1412.711716.633
1509.8961713.7551526.9231716.4421554.1311727.041 1573.751730.2911624.2751733.479
1718.4851734.941 1754.091742.489 1780.321744.651 1867.891751.529 1899.321755.543
#Mann= 11 ,-1 , 0
       0     .05       0  449.92      .1       0  925.39    .045       0
  976.32      .1       0 1185.12     .06       0 1298.91     .05       0
 1375.89      .1       0 1412.71     .05       0 1754.09      .1       0
 1780.32      .1       0 1867.89      .1       0
#XS Ineff= 2 , 0
          779.15 1716.05  1179.7         1716.27
Permanent Ineff=
       F       F
Bank Sta=925.39,976.32
XS Rating Curve= 0 ,0
Exp/Cntr(USF)=0,0
Exp/Cntr=0.3,0.1
Stream Node=LITTLEFK        ,Main            , 0 , 0 ,Upstream end
Stream Node=LITTLEFK        ,Main            , 0 , 1 ,Downstream end
LCMann Table=0

Chan Stop Cuts=-1
Use User Specified Reach Order=0
Composite Channel Slope=5